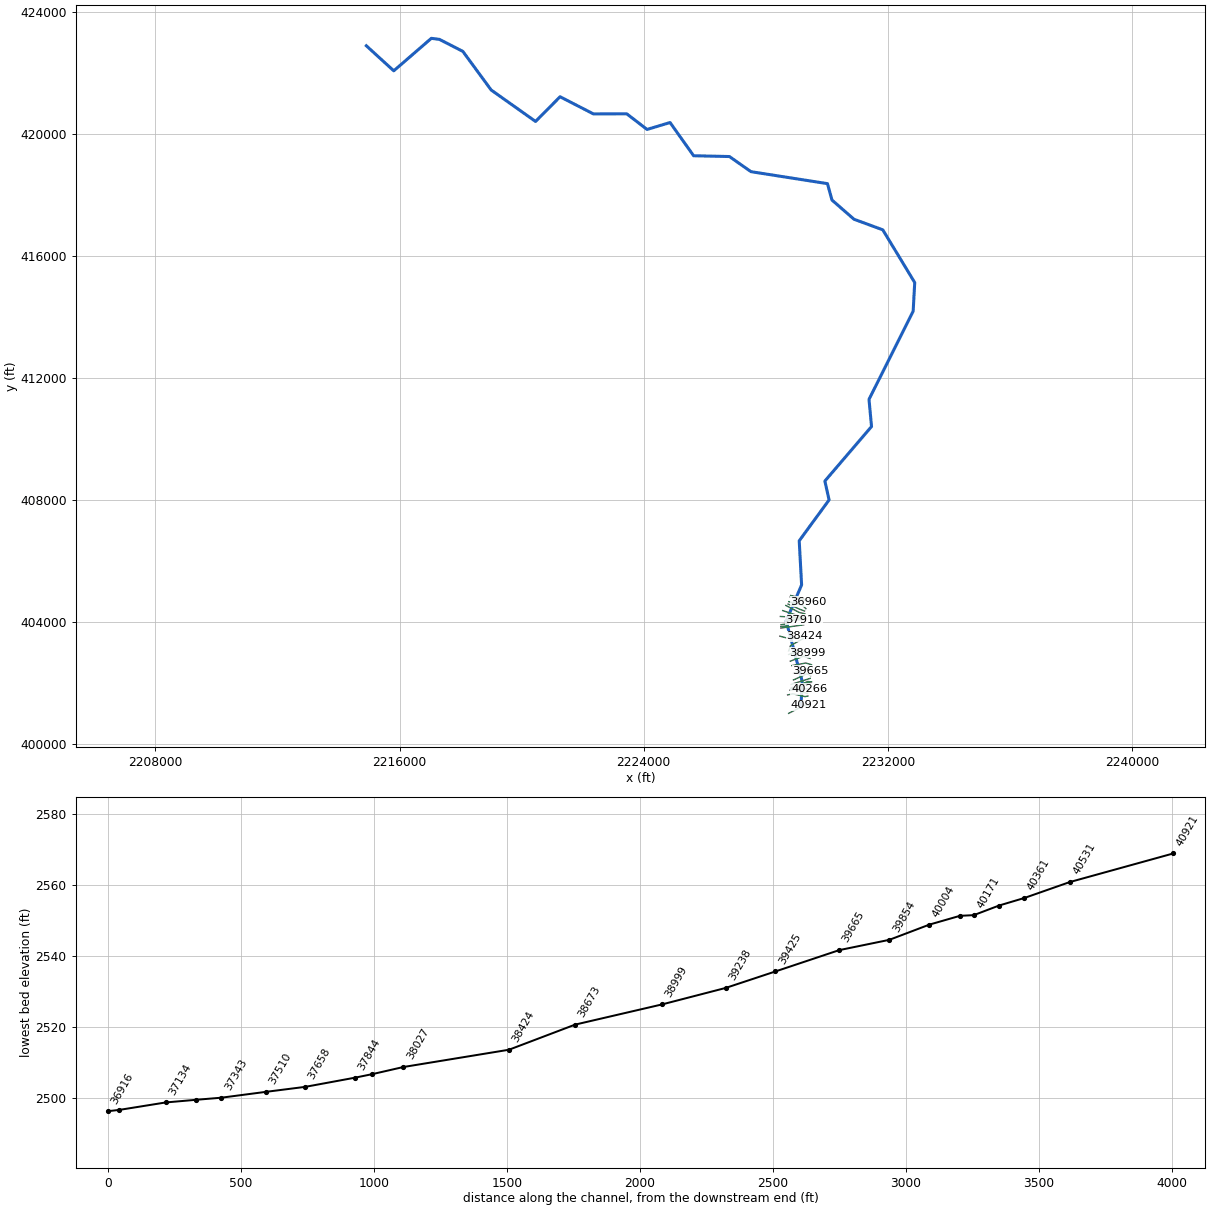
--- BEAVERCK.prj (project) ---

Proj Title=BEAVERCK
Current Plan=p01
Default Exp/Contr=0,0
English Units
Geom File=g01
Flow File=f01
Plan File=p01
Background Map Layer=Inundation Boundary (01pct Value_0)
BEGIN DESCRIPTION:
----------MODEL BY WOOD PLC 2021----------
Stream Name: Beaver Creek
Flood Zone: Approximate
Pocahontas County, WV
HEC-RAS Version: RAS 6.1
Vertical Datum: NAVD88
Projection: NAD 1983 StatePlane West Virginia S FIPS 4702 (US Feet)
Terrain: 1-meter LIDAR (FEMA Region III 3DEP collected 2016-2018)
Land Use: 2019 NLCD
Hydrologic Method:
WV SIR2010-5033 regression equations
END DESCRIPTION:
DSS File=dss
DSS Export Rating Curves= 0
DSS Export Rating Curve Sorted= 0
DSS Export Volume Flow Curves= 0
DXF OffsetX= 0
DXF OffsetY= 0
DXF ScaleX= 0
DXF ScaleY= 0

--- BEAVERCK.p01 (plan) ---

Plan Title=Floodplain
Program Version=6.10
Short Identifier=Floodplain
Geom File=g01
Flow File=f01
Subcritical Flow
K Sum by GR= 0
Std Step Tol= 0.01
Critical Tol= 0.01
Num of Std Step Trials= 20
Max Error Tol= 0.3
Flow Tol Ratio= 0.001
Split Flow NTrial= 30
Split Flow Tol= 0.02
Split Flow Ratio= 0.02
Log Output Level= 0
Friction Slope Method= 1
Unsteady Friction Slope Method= 2
Unsteady Bridges Friction Slope Method= 1
Parabolic Critical Depth
Global Vel Dist= 0 , 0 , 0
Global Log Level= 0
CheckData=True
Encroach Param=-1 ,0,0, 0
Computation Interval=0.1SEC
Output Interval=1SEC
Instantaneous Interval=Max Profile
Mapping Interval=1HOUR
Computation Time Step Use Courant=        0
Computation Time Step Use Time Series=    0
Computation Time Step Count To Double=0
Computation Time Step Max Doubling=0
Computation Time Step Max Halving=0
Computation Time Step Residence Courant=0
Run HTab= 0
Run UNet= 0
Run Sediment= 0
Run PostProcess= 0
Run WQNet= 0
Run RASMapper= 0
UNET Theta= 0
UNET Theta Warmup= 0
UNET ZTol= 0
UNET ZSATol= 0
UNET MxIter= 0
UNET Max Iter WO Improvement= 0
UNET MaxInSteps= 0
UNET DtIC= 0
UNET DtMin= 0
UNET MaxCRTS= 0
UNET WFStab= 0
UNET SFStab= 0
UNET WFX= 1
UNET SFX= 1
UNET Gravity=32.174
UNET 1D Methodology=Finite Difference
UNET DSS MLevel= 1
UNET Pardiso=0
UNET DZMax Abort= 0
UNET Use Existing IB Tables= 0
UNET Froude Reduction=False
UNET Froude Limit= 0
UNET Froude Power= 0
UNET D1 Cores= 0
UNET WindReference=Eulerian
UNET WindDragFormulation=Hsu (1988)
UNET D2 Coriolis=0
UNET D2 Cores= 0
UNET D2 Theta= 1
UNET D2 Theta Warmup= 1
UNET D2 Z Tol= 0.01
UNET D2 Volume Tol= 0.01
UNET D2 Max Iterations= 20
UNET D2 Equation= 0
UNET D2 RampUpFraction=0.1
UNET D2 TimeSlices= 1
UNET D2 Turbulence Formulation=Non-Conservative (original)
UNET D2 Smagorinsky Mixing=0
UNET D2 BCVolumeCheck=0
UNET D2 Cores=0
UNET D2 SolverType=PARDISO (Direct)
UNET D2 Minimum Iterations= 2147483647
UNET D2 Maximum Iterations= 2147483647
UNET D2 Restart Number= 10
UNET D2 Relaxation Coeff=1.3
UNET D2 SOR Precondition Iterations= 10
UNET D2 ILUT Maximum Fill= 8
UNET D2 ILUT Tolerance=1E-08
UNET D1D2 MaxIter= 0
UNET D1D2 ZTol=0.01
UNET D1D2 QTol=0.1
UNET D1D2 MinQTol=1
DSS File=dss
Write IC File= 0
Write IC File at Fixed DateTime=0
Write IC File at Sim End=0
Echo Input=False
Echo Parameters=False
Echo Output=False
Write Detailed= 0
HDF Write Warmup=0
HDF Write Time Slices=0
HDF Flush=0
HDF Compression= 1
HDF Chunk Size= 1
HDF Spatial Parts= 1
HDF Use Max Rows=0
HDF Fixed Rows= 1
Calibration Method= 0
Calibration Iterations= 20
Calibration Max Change=0.05
Calibration Tolerance=0.2
Calibration Maximum=1.5
Calibration Minimum=0.5
Calibration Optimization Method= 1
WQ AD Non Conservative
WQ ULTIMATE=-1
WQ Max Comp Step=1HOUR
WQ Output Interval=15MIN
WQ Output Selected Increments= 0
WQ Output face flow=0
WQ Output face velocity=0
WQ Output face area=0
WQ Output face dispersion=0
WQ Output cell volume=0
WQ Output cell surface area=0
WQ Output cell continuity=0
WQ Output cumulative cell continuity=0
WQ Output face conc=0
WQ Output face dconc_dx=0
WQ Output face courant=0
WQ Output face peclet=0
WQ Output face adv mass=0
WQ Output face disp mass=0
WQ Output cell mass=0
WQ Output cell source sink temp=0
WQ Output nsm pathways=0
WQ Output nsm derived pathways=0
WQ Create Restart=0
WQ Fixed Restart=0
WQ System Summary=0
WQ Write To DSS=0
Sorting and Armoring Iterations= 10
XS Update Threshold= 0.02
Bed Roughness Predictor= 0
Hydraulics Update Threshold= 0.02
Energy Slope Method= 1
Volume Change Method= 1
Sediment Retention Method= 0
Sediment TS Multiplier= 1
Warm Up Method= 0
XS Weighting Method= 0
Number of US Weighted Cross Sections= 1
Number of DS Weighted Cross Sections= 1
Upstream XS Weight=0
Main XS Weight=1
Downstream XS Weight=0
Number of DS XS's Weighted with US Boundary= 1
Upstream Boundary Weight= 1
Weight of XSs Associated with US Boundary= 0
Number of US XS's Weighted with DS Boundary= 1
Downstream Boundary Weight= 0.5
Weight of XSs Associated with DS Boundary= 0.5
Percentile Method= 0
Sediment Output Level= 3
Mass or Volume Output= 0
Output Increment Type= 1
Profile and TS Output Increment= 1
Transport Output Increment 1
XS Output Flag= 0
XS Output Increment= 10
Read HDF5 Sediment Hotstart= 0
Sediment Hotstart Type= 0
Write Gradation File= 0
Read Gradation Hotstart= 0
Write HDF5 File= 1
Write Binary Output= 1
Write DSS Sediment File= 0
DSS Sediment Output Type= 1
SV Curve= 0
Specific Gage Flag= 0
Subcell Erosion Methods= 0
Subcell Deposition Methods= 0
Advection Scheme= 1
Matrix Solver= 0
Implicit Weighting Factor= 1
Maximum Outer Loop Convergence Iterations= 5
Convergence Maximum Absolute= 0.001
Convergence RMSE= 0.0001
Grain Fractions Max Abs Error= 0.001
Max Subgrid Regions= 1
Max Subgrid Length Scale= 3.402823E+38
Initial Layer Thickness= 3.402823E+38
Min Layer Thickness= 3.402823E+38
Max Layer Thickness= 3.402823E+38
Number of Layers= 5

--- BEAVERCK.f01 (steady flow) ---

Flow Title=Flow
Program Version=6.10
Number of Profiles= 6
Profile Names=01pct,10pct,04pct,02pct,0_2pct,01plus
River Rch & RM=BEAVERCK,Main            ,40921
     745     398     526     632    1040    1100
River Rch & RM=BEAVERCK,Main            ,35127
    1040     562     740     885    1440    1540
River Rch & RM=BEAVERCK,Main            ,33863
    1230     667     874    1040    1690    1810
River Rch & RM=BEAVERCK,Main            ,30801
    1430     783    1020    1220    1960    2110
River Rch & RM=BEAVERCK,Main            ,26184
    1600     878    1140    1360    2190    2360
River Rch & RM=BEAVERCK,Main            ,24349
    1830    1010    1320    1560    2500    2710
River Rch & RM=BEAVERCK,Main            ,18945
    2480    1390    1790    2130    3370    3670
River Rch & RM=BEAVERCK,Main            ,16783
    2760    1550    2000    2370    3740    4080
Boundary for River Rch & Prof#=BEAVERCK,Main            , 1
Up Type= 0
Dn Type= 3
Dn Slope=0.01078
Boundary for River Rch & Prof#=BEAVERCK,Main            , 2
Up Type= 0
Dn Type= 3
Dn Slope=0.01078
Boundary for River Rch & Prof#=BEAVERCK,Main            , 3
Up Type= 0
Dn Type= 3
Dn Slope=0.01078
Boundary for River Rch & Prof#=BEAVERCK,Main            , 4
Up Type= 0
Dn Type= 3
Dn Slope=0.01078
Boundary for River Rch & Prof#=BEAVERCK,Main            , 5
Up Type= 0
Dn Type= 3
Dn Slope=0.01078
Boundary for River Rch & Prof#=BEAVERCK,Main            , 6
Up Type= 0
Dn Type= 3
Dn Slope=0.01078
DSS Import GetInterval= 0
DSS Import GetPeak= 0
DSS Import FillOption= 0

--- BEAVERCK.g01 (geometry) ---

Geom Title=Geometry
Program Version=6.10

River Reach=BEAVERCK        ,Main
Reach XY= 30
2229152.11099999401190.695999995     2229192.189402050.520000011
2228668.19400002404024.7870000152229173.76585902405209.357977584
2229095.36000003406656.2489999982230074.30900003      407995.934
2229935.97399999408614.5049999952231464.96030344 410402.49686648
2231382.49000002411292.3410000212232829.21499999414184.865999997
2232880.74700002415123.9350000172231833.89800002416852.657000005
2230888.92900001417200.5929999952230169.03600003417829.226999998
2230021.38766237418366.8625676782227514.47000004      418759.706
2226808.33771633419255.8394587142225634.77963575419281.986182835
 2224862.8769701420371.246866465     2224109.149420144.208000004
2223443.43252568420657.357977584     2222353.258420652.807000011
2221258.71030347 421216.385755362220455.23808123420406.663533136
2219000.98200004421437.243500009      2218072.58422704.044000015
2217305.86300002 423097.635000022217040.09505562423131.778166682
2215808.51400004 422065.988000022214910.63700001422887.585000008

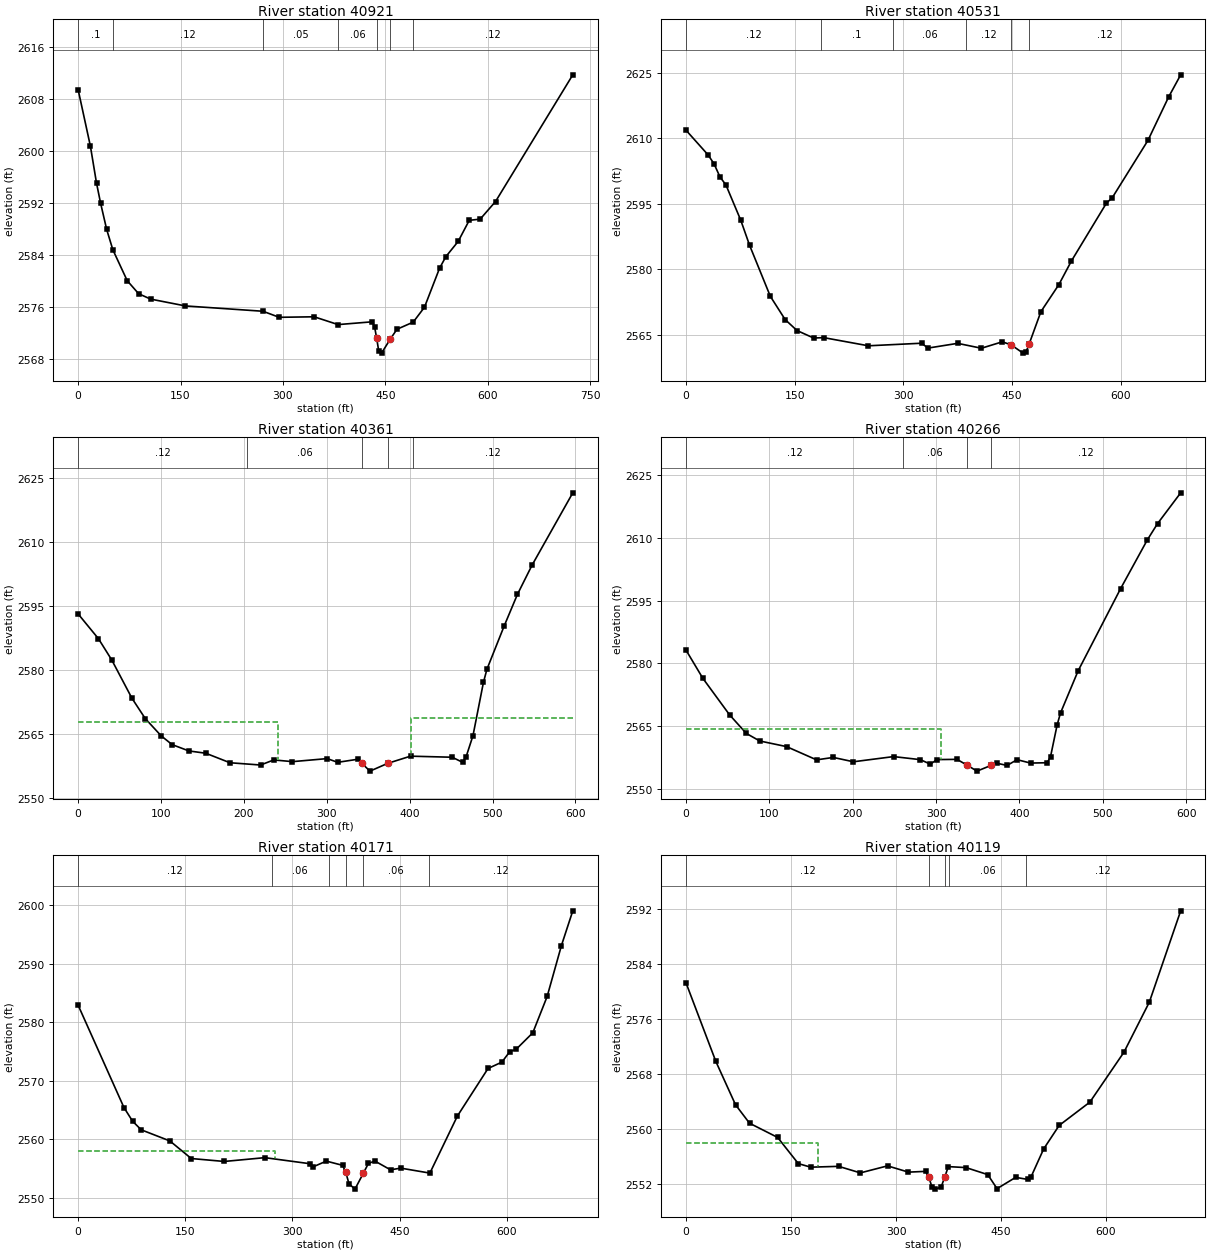
Type RM Length L Ch R = 1 ,40921   ,399.3,390.2,379
XS GIS Cut Line= 3
2228748.13633698400996.9449781362229292.96244438401274.682385212
2229405.16280064401259.635761413
#Sta/Elev= 30
       0 2609.41      18  2600.7    26.9 2595.05    32.9 2591.95    41.8 2587.91
    50.8  2584.8    71.9 2580.03    88.6 2578.03   106.2  2577.2   157.2 2576.15
   270.8 2575.33   294.6  2574.4   345.8 2574.48   380.8 2573.28   431.1 2573.71
   434.4 2572.89   437.4 2571.16   440.3 2569.27   444.5 2568.89   457.5 2571.08
   467.1 2572.56   490.9 2573.66   507.4 2575.95   529.5 2581.95   538.8 2583.74
   556.8 2586.08     573 2589.32     589  2589.5   611.5 2592.21   724.7  2611.7
#Mann= 7 ,-1,0
       0      .1       0    50.8     .12       0   270.8     .05       0
   380.8     .06       0   437.4    .045       0   457.5     .06       0
   490.9     .12       0
Bank Sta=437.4,457.5
XS Rating Curve= 0 ,0
Exp/Cntr=0.3,0.1

Type RM Length L Ch R = 1 ,40531   ,167.8,169.7,161.1
XS GIS Cut Line= 4
2228714.30929486401602.5899929532228886.53906145401638.692566647
2229286.01625573401545.9211480222229380.44352925 401565.93219678
#Sta/Elev= 30
       0 2611.87    30.5 2606.21    38.7 2604.16    46.9 2601.15      55 2599.36
    75.5 2591.26    87.7 2585.51   116.3 2573.83   136.8 2568.49   153.1 2565.99
   176.1 2564.27     190 2564.36   251.6 2562.49   325.2 2563.08   333.7 2561.96
   374.8 2563.05   407.6 2561.93   436.4  2563.4   448.5 2562.72   465.1 2560.81
   469.2 2561.09   473.3 2562.82   489.7 2570.31   514.4 2576.48   531.8 2581.92
   580.1 2595.17   588.3 2596.45   637.4 2609.54     666 2619.51   682.6 2624.57
#Mann= 6 ,-1,0
       0     .12       0  185.97      .1       0  285.97     .06       0
  385.97     .12       0   448.5    .045       0   473.3     .12       0
Bank Sta=448.5,473.3
XS Rating Curve= 0 ,0
Exp/Cntr=0.3,0.1

Type RM Length L Ch R = 1 ,40361   ,93.8,95.3,102.6
XS GIS Cut Line= 3
 2228791.9950868401757.1817040582228944.06587107401780.049491165
2229367.11993256401648.559715296
#Sta/Elev= 30
       0 2593.12    24.5 2587.33    40.6 2582.34    64.9  2573.4      81 2568.64
   100.2  2564.6   113.4 2562.55   133.7 2561.07   153.9 2560.54   183.2 2558.31
   220.1 2557.78     236 2558.97   258.6 2558.57   300.5 2559.28   313.1 2558.41
   338.2 2559.15   342.4 2558.16   352.1 2556.35   373.5 2558.17     401 2559.85
   451.3  2559.6   463.9 2558.41   468.1 2559.71   476.4 2564.67     489 2577.12
   493.2 2580.18   514.1 2590.35     530  2597.7   547.6 2604.52   596.8 2621.46
#Mann= 5 ,-1,0
       0     .12       0  203.78     .06       0   342.4    .045       0
   373.5     .06       0  403.78     .12       0
#XS Ineff= 2 , 0
          240.97 2567.95  401.94         2568.71
Permanent Ineff=
       F       F
Bank Sta=342.4,373.5
XS Rating Curve= 0 ,0
Exp/Cntr(USF)=0,0
Exp/Cntr=0.3,0.1

Type RM Length L Ch R = 1 ,40266   ,86,95.2,102.9
XS GIS Cut Line= 3
2228828.07511009401791.0832133712229098.83609685401813.646628935
2229420.09615654401795.381006812
#Sta/Elev= 30
       0 2583.18    20.2 2576.43    52.3 2567.68    72.3 2563.25    88.4 2561.44
   120.6 2560.09   156.6 2556.92   176.7  2557.5   200.8 2556.46     249  2557.7
   281.1 2556.97   293.1 2555.89   301.1 2556.98   325.1 2557.04   337.1 2555.66
   349.1 2554.22   366.1  2555.6   373.2  2556.1   385.2 2555.58   397.2 2556.96
   413.3 2556.15   433.3 2556.23   437.3 2557.65   445.3 2565.32   449.3 2568.14
   470.5 2578.26   521.4 2597.91   553.5 2609.59   565.7 2613.47   593.5 2620.85
#Mann= 4 ,-1,0
       0     .12       0     260     .06       0   337.1    .045       0
   366.1     .12       0
#XS Ineff= 2 , 0
          305.53 2564.37
Permanent Ineff=
       F       F
Bank Sta=337.1,366.1
XS Rating Curve= 0 ,0
Exp/Cntr(USF)=0,0
Exp/Cntr=0.5,0.3

Type RM Length L Ch R = 1 ,40171   ,52.9,51.9,50.9
XS GIS Cut Line= 4
2228828.07511009401808.2743871342229048.33702392401823.316664176
2229377.11822213401998.4517468842229475.96747127401988.781711642
#Sta/Elev= 30
       0 2582.94    64.2 2565.44    76.3 2563.11    88.3 2561.65   128.4 2559.75
   158.4 2556.74   204.6 2556.24   261.4 2556.89   324.8 2555.85   329.4 2555.34
   347.5  2556.3   370.2 2555.58   374.7 2554.41   379.2 2552.43   387.6 2551.51
   399.5 2554.27   406.4  2555.9   415.5 2556.31   437.4 2554.81   451.7  2555.1
   492.5 2554.25     531    2564   573.9 2572.13   593.3 2573.22   604.4 2575.01
   613.1 2575.39   636.6 2578.23   656.7 2584.44   676.7 2593.15   692.6 2599.08
#Mann= 6 ,-1,0
       0     .12       0  270.77     .06       0  350.77     .12       0
   374.7    .045       0   399.5     .06       0  490.77     .12       0
#XS Ineff= 3 ,-1
       0     275    2558     275     367  2554.5     410     505  2554.5
Permanent Ineff=
       F       F       F
Bank Sta=374.7,399.5
XS Rating Curve= 0 ,0
Exp/Cntr(USF)=0,0
Exp/Cntr=0.5,0.3

Type RM Length L Ch R = 1 ,40119   ,121,114.7,115.4
XS GIS Cut Line= 4
2228837.74514533 401844.805631382228982.79567395401856.624563341
2229371.74598033402043.5785780112229500.67978355402029.610749329
#Sta/Elev= 30
       0 2581.28    42.6 2569.87    70.7 2563.58    90.7  2560.9   130.9 2558.83
   160.4 2555.03   178.1 2554.51   218.1 2554.63   249.1 2553.68   287.9  2554.7
   317.8 2553.79   342.3  2553.9   346.8 2553.09   351.2 2551.69   355.7 2551.32
   364.5 2551.61   369.5 2553.04   374.8 2554.59     400 2554.45   431.1 2553.43
   444.4 2551.39     471 2553.03   488.8 2552.72   493.2 2553.15     511 2557.16
   533.2 2560.58   577.1 2563.97   625.8 2571.23     662 2578.49   706.8 2591.76
#Mann= 5 ,-1,0
       0     .12       0   346.8    .045       0   369.5     .12       0
  375.53     .06       0  485.53     .12       0
#XS Ineff= 3 ,-1
       0     188    2558     188     345  2553.4     372     520  2553.4
Permanent Ineff=
       F       F       F
Bank Sta=346.8,369.5
XS Rating Curve= 0 ,0
Exp/Cntr(USF)=0,0
Exp/Cntr=0.5,0.3

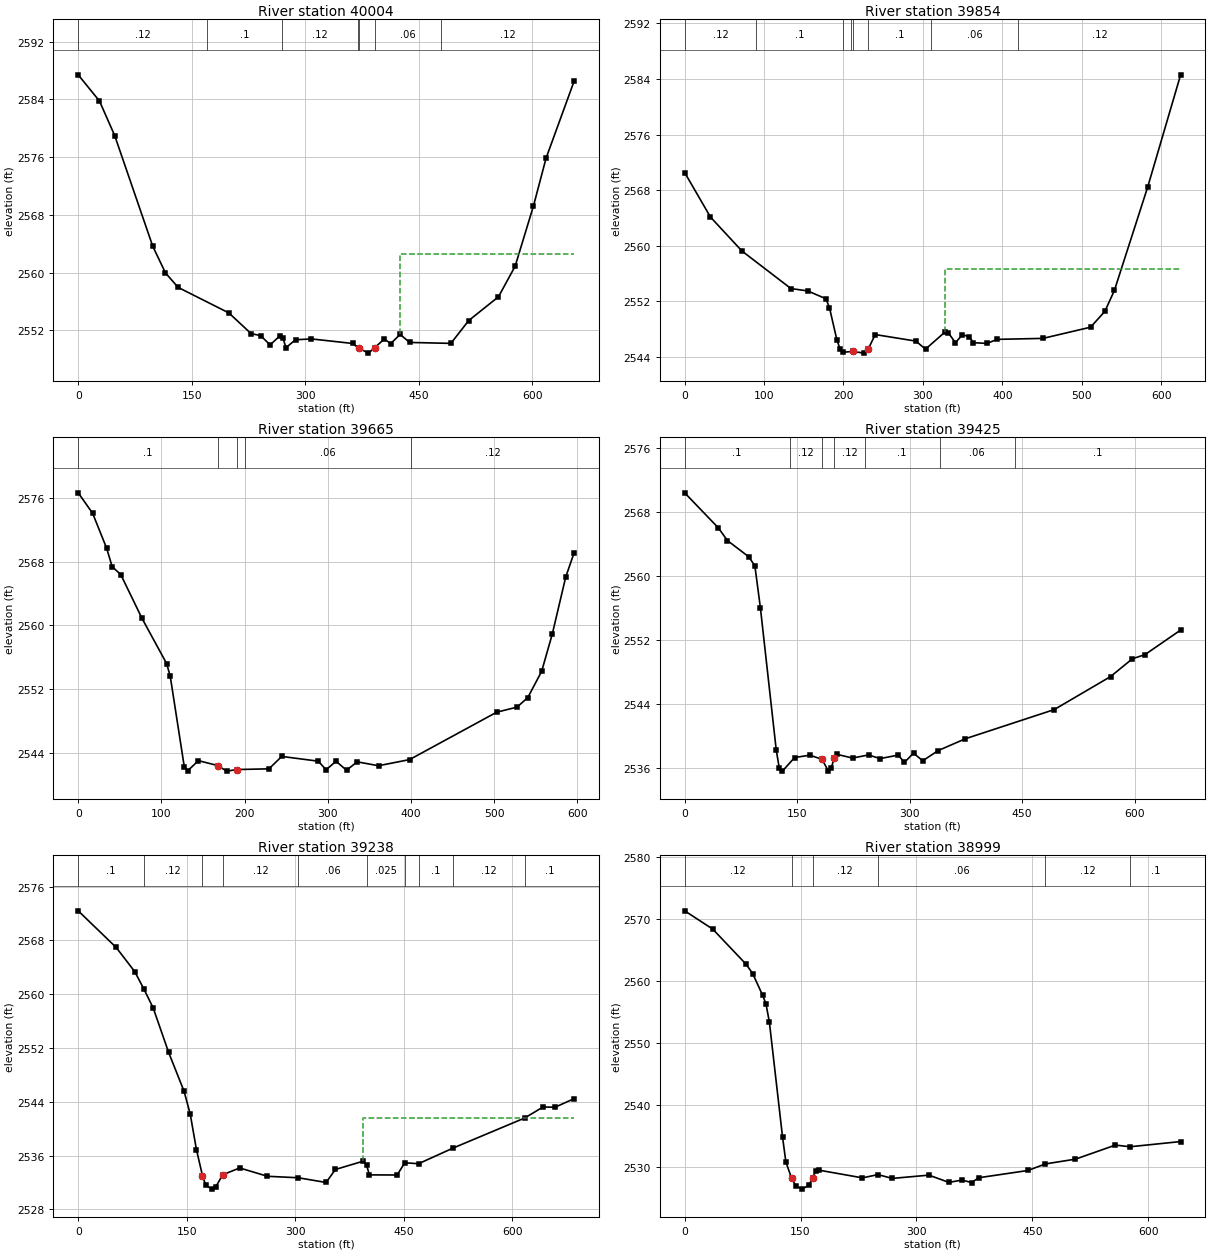
Type RM Length L Ch R = 1 ,40004   ,149.7,150.8,153.3
XS GIS Cut Line= 2
2228830.22400681401947.9526739562229455.55295242402144.576723867
#Sta/Elev= 30
       0  2587.4    28.1 2583.77    48.2 2578.99    98.5 2563.66   115.3 2559.97
     132 2557.96   199.1 2554.42   228.5 2551.55   241.1 2551.28   253.6 2549.99
   266.2 2551.21   270.4 2551.01   274.6 2549.61   287.2  2550.7   308.1 2550.82
   362.6 2550.19     371 2549.52   383.6 2548.85   391.7 2549.59   404.6 2550.81
     413 2550.17   425.5 2551.44   438.1 2550.33   492.6  2550.2   516.1 2553.36
   555.5 2556.66   577.5 2560.89   601.7 2569.23   618.4 2575.86   655.5 2586.54
#Mann= 7 ,-1,0
       0     .12       0     170      .1       0     270     .12       0
     370     .06       0     371    .045       0   391.7     .06       0
     480     .12       0
#XS Ineff= 2 , 0
                          425.41         2562.62
Permanent Ineff=
       F       F
Bank Sta=371,391.7
XS Rating Curve= 0 ,0
Exp/Cntr(USF)=0,0
Exp/Cntr=0.3,0.1

Type RM Length L Ch R = 1 ,39854   ,189,188.4,187.4
XS GIS Cut Line= 3
2228906.71515212402092.0253941692229345.72020092402295.294612904
2229472.76346263402234.596165643
#Sta/Elev= 30
       0 2570.53    32.5 2564.13    72.1 2559.25   133.8 2553.85   155.1  2553.5
   177.9 2552.38   182.3 2551.12   191.8 2546.41   195.6  2545.2     200 2544.69
   211.42544.802   226.4 2544.56   231.42545.203     240 2547.23   291.2 2546.29
   303.3 2545.13   327.8 2547.59   332.2 2547.45     341 2546.06   349.8 2547.21
   358.7 2546.91   363.5 2546.06   380.7 2545.96   393.6 2546.54   451.2 2546.68
   511.2 2548.29   529.2 2550.57   541.2 2553.58   583.2 2568.48   624.6 2584.59
#Mann= 8 ,-1,0
       0     .12       0      90      .1       0     200     .12       0
     210      .1       0   211.4    .045       0   231.4      .1       0
     310     .06       0     420     .12       0
#XS Ineff= 2 , 0
                          328.42         2556.59
Permanent Ineff=
       F       F
Bank Sta=211.4,231.4
XS Rating Curve= 0 ,0
Exp/Cntr(USF)=0,0
Exp/Cntr=0.3,0.1

Type RM Length L Ch R = 1 ,39665   ,241.2,240.1,235.1
XS GIS Cut Line= 3
2228903.89196853402309.4105308722229300.54926342402449.158118752
2229469.94027903402402.575589459
#Sta/Elev= 30
       0  2576.7    17.3 2574.13    34.2 2569.72    40.8 2567.41    51.2  2566.4
    76.6 2560.91   106.3  2555.2   110.6 2553.62   127.5 2542.22   131.8 2541.72
   144.5 2542.98   167.8 2542.36   178.4 2541.66   191.1 2541.86   229.3 2541.95
   244.7 2543.51   288.7 2542.91     298 2541.82   309.9 2542.91   322.6 2541.77
   335.3 2542.83     361 2542.34   398.3 2543.11   503.1 2549.08   527.6 2549.72
   540.5 2550.93   557.1 2554.22   569.9 2558.91   586.1 2566.11   596.2 2569.17
#Mann= 5 ,-1,0
       0      .1       0   167.8    .045       0   191.1      .1       0
     200     .06       0     400     .12       0
Bank Sta=167.8,191.1
XS Rating Curve= 0 ,0
Exp/Cntr(USF)=0,0
Exp/Cntr=0.3,0.1

Type RM Length L Ch R = 1 ,39425   ,185.6,186.9,189.6
XS GIS Cut Line= 3
2228852.07105574402563.814603076 2229310.7242476402648.189260452
2229497.91875348402594.197479096
#Sta/Elev= 30
       0 2570.35    44.8 2565.99      57  2564.4    85.5 2562.37    93.6 2561.24
   100.9 2556.05   122.1 2538.26   126.2 2535.99   130.3 2535.65   146.5 2537.34
   166.9 2537.64   183.1 2537.12   191.3 2535.71   195.3 2536.01   199.4 2537.27
   203.5 2537.73   223.8 2537.28   245.2 2537.67   260.4 2537.21   284.8 2537.65
   292.9 2536.73   305.1 2537.89   317.4 2536.94   337.9 2538.21   374.3 2539.69
   492.6 2543.32   567.8 2547.44   596.9 2549.66   613.6 2550.17   661.2 2553.24
#Mann= 7 ,-1,0
       0      .1       0     140     .12       0   183.1    .045       0
   199.4     .12       0     240      .1       0     340     .06       0
     440      .1       0
Bank Sta=183.1,199.4
XS Rating Curve= 0 ,0
Exp/Cntr=0.3,0.1

Type RM Length L Ch R = 1 ,39238   ,236.4,238.7,235.3
XS GIS Cut Line= 3
2228803.04157683402709.2046964242229231.22442185402869.185100058
2229449.23693268402800.173945549
#Sta/Elev= 30
       0 2572.41    52.5 2566.96    78.1 2563.38      91 2560.74   103.7 2557.95
     125 2551.36   146.4 2545.56   154.9 2542.17   163.5 2536.89   171.8 2533.02
   176.3 2531.58   184.8 2531.01   190.5  2531.4   199.7 2533.14   223.3 2534.16
   261.7 2532.92   304.4  2532.7   342.8    2532   355.6 2533.93   394.1 2535.17
   398.8 2534.59   402.6 2533.13     441 2533.11   451.6 2534.93   470.6 2534.79
   518.4 2537.12   617.2 2541.58   642.7 2543.22   659.5  2543.2   685.8 2544.47
#Mann= 10 ,-1,0
       0      .1       0      91     .12       0   171.8    .045       0
   199.7     .12       0   304.4     .06       0   398.8    .025       0
   451.6     .12       0   470.6      .1       0   518.4     .12       0
   617.2      .1       0
#XS Ineff= 2 , 0
                           394.3          2541.6
Permanent Ineff=
       F       T
Bank Sta=171.8,199.7
XS Rating Curve= 0 ,0
Exp/Cntr(USF)=0,0
Exp/Cntr=0.3,0.1

Type RM Length L Ch R = 1 ,38999   ,318.9,326.9,326.7
XS GIS Cut Line= 3
2228754.42008161402928.7856425882229121.43394877403074.650128254
2229350.42550691402982.112443799
#Sta/Elev= 30
       0 2571.31    36.3 2568.36    79.4  2562.7      88 2561.19   100.9 2557.67
   105.2  2556.3   109.6 2553.37   126.7 2534.75     131 2530.75   138.32528.169
   143.9  2526.9   152.4 2526.38   161.1 2527.07   165.5 2528.21   169.8 2529.35
   173.9 2529.44     230  2528.2   250.2 2528.72   268.8 2528.11   316.1 2528.64
   341.9 2527.47   359.1 2527.84   371.3 2527.44   380.7 2528.22   444.3 2529.39
   466.9 2530.45   505.8 2531.22   557.5 2533.49   576.4 2533.22   641.9 2534.06
#Mann= 6 ,-1,0
       0     .12       0   138.3    .045       0   165.5     .12       0
   250.2     .06       0   466.9     .12       0   576.4      .1       0
Bank Sta=138.3,165.5
XS Rating Curve= 0 ,0
Exp/Cntr(USF)=0,0
Exp/Cntr=0.3,0.1

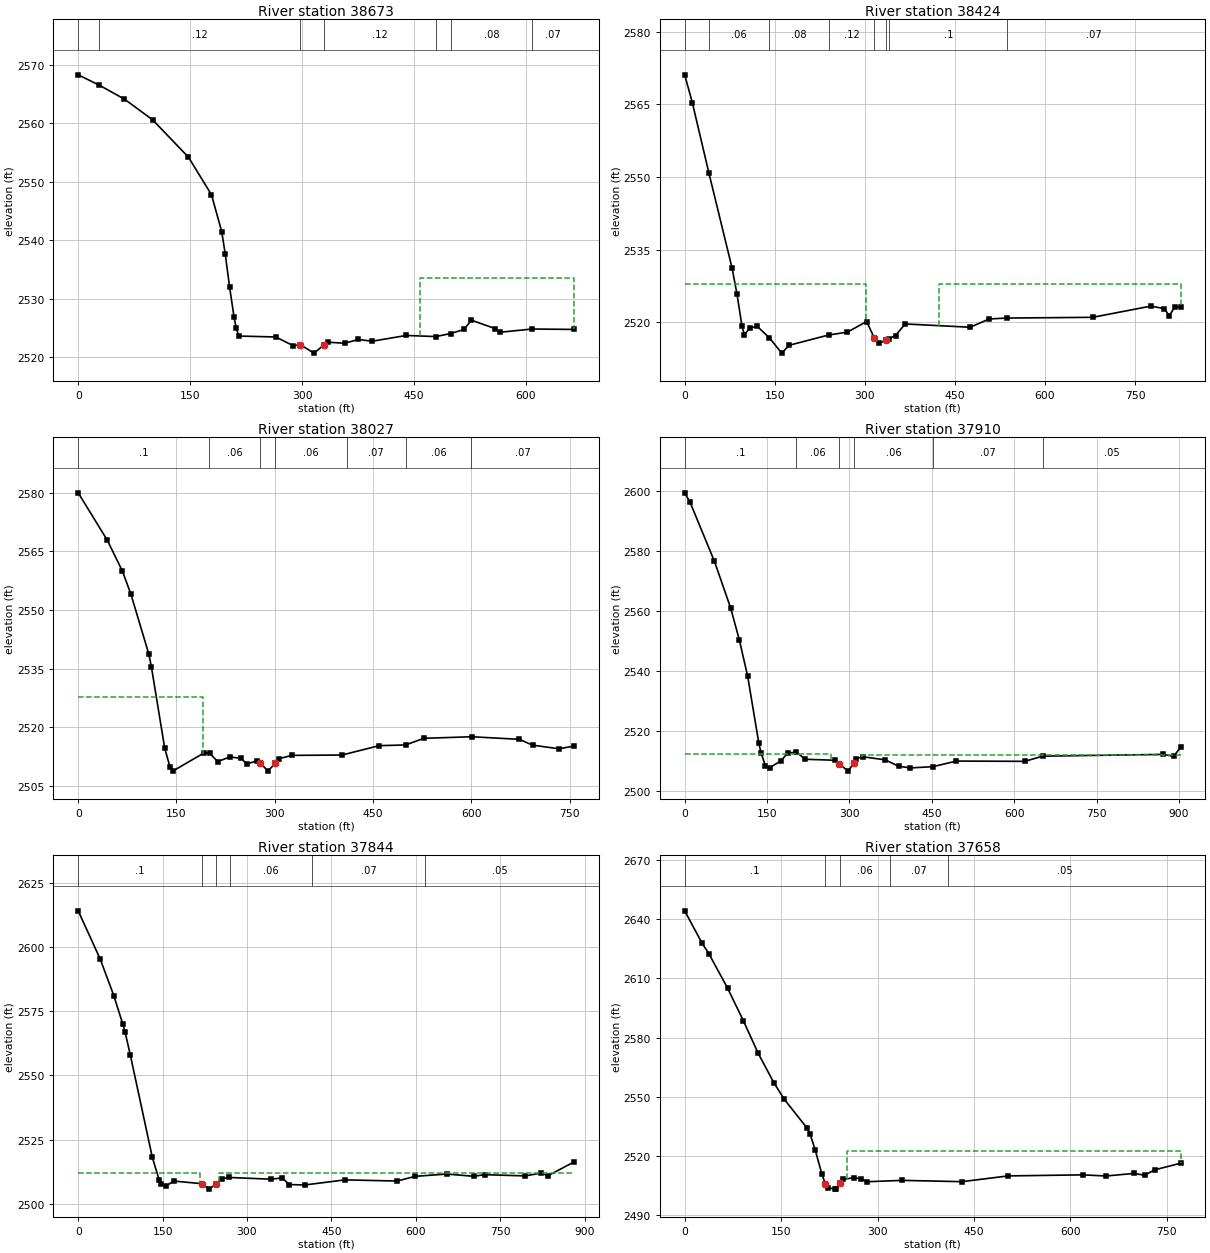
Type RM Length L Ch R = 1 ,38673   ,253.4,248.6,241.3
XS GIS Cut Line= 3
2228752.85164628403046.4182923192228807.74688282403215.809307931
2229232.79285718403452.643042722
#Sta/Elev= 30
       0 2568.25    28.1 2566.49      62 2564.09    99.6 2560.57   147.7 2554.18
   178.6 2547.76   192.3 2541.45     197 2537.66   202.9 2531.93   208.8 2526.88
   211.7 2524.97   215.2 2523.61   264.7 2523.45   288.2 2521.96   297.6 2522.15
   315.9 2520.69   328.8 2522.03   335.2 2522.55   357.1 2522.38   375.5 2523.02
   393.8 2522.72   439.6 2523.71   479.3 2523.52   499.1 2524.04   517.4 2524.75
   526.6 2526.33   558.6 2524.89   564.6 2524.25   608.2 2524.81   664.6 2524.74
#Mann= 7 ,-1,0
       0      .1       0    28.1     .12       0   297.6    .045       0
   328.8     .12       0   479.3     .06       0   499.1     .08       0
   608.2     .07       0
#XS Ineff= 2 , 0
       0                   457.9       0 2533.57
Permanent Ineff=
       F       F
Bank Sta=297.6,328.8
XS Rating Curve= 0 ,0
Exp/Cntr(USF)=0,0
Exp/Cntr=0.3,0.1

Type RM Length L Ch R = 1 ,38424   ,391.7,396.6,397.4
XS GIS Cut Line= 4
 2228459.7865895403528.7223015382228652.36049267403478.463917828
2228977.63566886403460.8157594562229270.70368489403530.210780634
#Sta/Elev= 30
       0 2571.13    12.8 2565.35    40.3 2550.86    78.9 2531.21    87.2 2525.78
    95.5 2519.14    99.6 2517.42   108.1 2518.75   120.3  2519.2   140.9 2516.82
   161.6 2513.62     174 2515.24   239.8 2517.37   270.9 2517.95     303 2520.15
   316.1 2516.67     323 2515.64     335 2516.27   340.7 2516.64   351.1 2517.24
   367.1 2519.65   475.2 2518.97   507.3 2520.68   537.2 2520.87   679.5 2521.02
   776.5 2523.34   798.7 2522.81   806.9 2521.36   816.3 2523.14   825.9 2523.17
#Mann= 8 ,-1,0
       0      .1       0    40.3     .06       0   140.9     .08       0
   239.8     .12       0   316.1    .045       0     335     .12       0
   340.7      .1       0   537.2     .07       0
#XS Ineff= 2 , 0
       0  301.73 2527.98   423.2       0    2528
Permanent Ineff=
       F       F
Bank Sta=316.1,335
XS Rating Curve= 0 ,0
Exp/Cntr=0.3,0.1

Type RM Length L Ch R = 1 ,38027   ,99,117.7,137.7
XS GIS Cut Line= 2
2228493.47066706403793.7621031622229242.93156026403901.206939179
#Sta/Elev= 30
       0    2580    44.3  2567.9    67.4 2559.98    80.5 2554.03   107.8 2538.71
   111.8 2535.38     132 2514.68   140.1 2509.78   144.2 2508.76   192.6 2513.47
   200.7 2513.34   212.9 2511.21   231.6  2512.4   249.2 2512.01   257.3 2510.54
   273.5 2511.47   277.5 2510.88   289.6 2508.81   301.1 2510.77   305.8 2511.91
     326 2512.79   402.8 2512.88   459.4 2515.28   499.8 2515.46   527.5 2517.16
   600.8 2517.56   673.4  2516.9   693.7  2515.4   734.1 2514.48   757.1 2515.19
#Mann= 7 ,-1,0
       0      .1       0     200     .06       0   277.5    .045       0
   301.1     .06       0     410     .07       0     500     .06       0
     600     .07       0
#XS Ineff= 2 , 0
          190.22 2527.85
Permanent Ineff=
       F       F
Bank Sta=277.5,301.1
XS Rating Curve= 0 ,0
Exp/Cntr(USF)=0,0
Exp/Cntr=0.5,0.3

Type RM Length L Ch R = 1 ,37910   ,68.2,65.4,66.4
XS GIS Cut Line= 4
2228494.38576778403841.708548415 2228715.3659557403869.580515941
2228752.98529466404054.6204614252229244.04361665404070.255904253
#Sta/Elev= 30
       0  2599.4     9.9 2596.22    54.2 2576.57    83.5 2561.17    99.6 2550.35
   114.7 2538.32   134.8 2516.24   138.9 2512.88   146.9 2508.57   155.1 2507.92
   175.2 2510.16   187.2 2512.71   203.4 2513.08   219.5 2510.69     274 2510.36
   281.82509.063   297.7 2506.74   307.9 2509.45   312.1 2510.91   324.4 2511.52
   365.2 2510.49   389.3 2508.39   410.7  2507.8     452 2508.23   494.8 2510.09
   618.9    2510     652 2511.72     871 2512.31   890.3 2511.67   902.9 2514.72
#Mann= 6 ,-1,0
       0      .1       0   203.4     .06       0   281.8    .045       0
   307.9     .06       0     452     .07       0     652     .05       0
#XS Ineff= 2 , 0
          267.23  2512.5  321.92            2512
Permanent Ineff=
       F       F
Bank Sta=281.8,307.9
XS Rating Curve= 0 ,0
Exp/Cntr=0.5,0.3

Type RM Length L Ch R = 1 ,37844   ,204.1,186,162.2
XS GIS Cut Line= 4
2228497.45010543403903.8598980932228665.91299647403926.410048862
2228709.68681855404086.9140631592229254.86987537404098.852378272
#Sta/Elev= 30
       0 2614.07    39.1 2595.28    63.3 2581.05    79.4 2569.87    83.5 2566.71
    92.6 2557.96   131.7 2518.15     144 2509.23     148 2507.56   156.1 2506.98
     170 2508.88   219.7 2507.86   232.7 2505.74   244.8 2507.66   255.5 2509.79
   268.5 2510.28   342.8 2509.61   362.8 2510.11   374.8 2507.52   402.8 2507.36
   474.1 2509.34   566.9 2508.89   598.9 2510.72   654.9 2511.61   702.9 2510.74
   722.9 2511.37   794.9 2510.88   822.9    2512   834.9 2510.94   881.6 2516.34
#Mann= 6 ,-1,0
       0      .1       0   219.7    .045       0   244.8      .1       0
  269.97     .06       0  416.33     .07       0  616.33     .05       0
#XS Ineff= 2 , 0
          217.35 2511.93  249.91         2511.85
Permanent Ineff=
       F       F
Bank Sta=219.7,244.8
XS Rating Curve= 0 ,0
Exp/Cntr(USF)=0,0
Exp/Cntr=0.5,0.3

Type RM Length L Ch R = 1 ,37658   ,151,148.2,142.7
XS GIS Cut Line= 2
2228477.55291357404174.4617073212229248.23747809404135.993803068
#Sta/Elev= 30
       0 2644.32    26.6 2628.17    38.1 2622.29    66.7 2605.13    91.5 2588.45
   114.3  2572.1   138.8 2557.12   154.8 2548.81   190.9 2533.92   194.9 2531.28
   202.9 2523.24   213.5 2510.72   218.9 2505.89   222.9 2503.91   233.3 2503.17
   234.9 2503.18   241.7 2506.41   246.9  2508.1   262.9 2508.97     275 2508.43
     283 2506.91   338.6 2507.61   431.4 2506.95   503.2 2509.87   619.4 2510.41
   655.4 2509.83   699.5 2511.14   715.5 2510.22   731.5 2512.98   771.6  2516.3
#Mann= 5 ,-1,0
       0      .1       0   218.9    .045       0   241.7     .06       0
     320     .07       0     410     .05       0
#XS Ineff= 2 , 0
                          252.01         2522.63
Permanent Ineff=
       F       F
Bank Sta=218.9,241.7
XS Rating Curve= 0 ,0
Exp/Cntr(USF)=0,0
Exp/Cntr=0.3,0.1

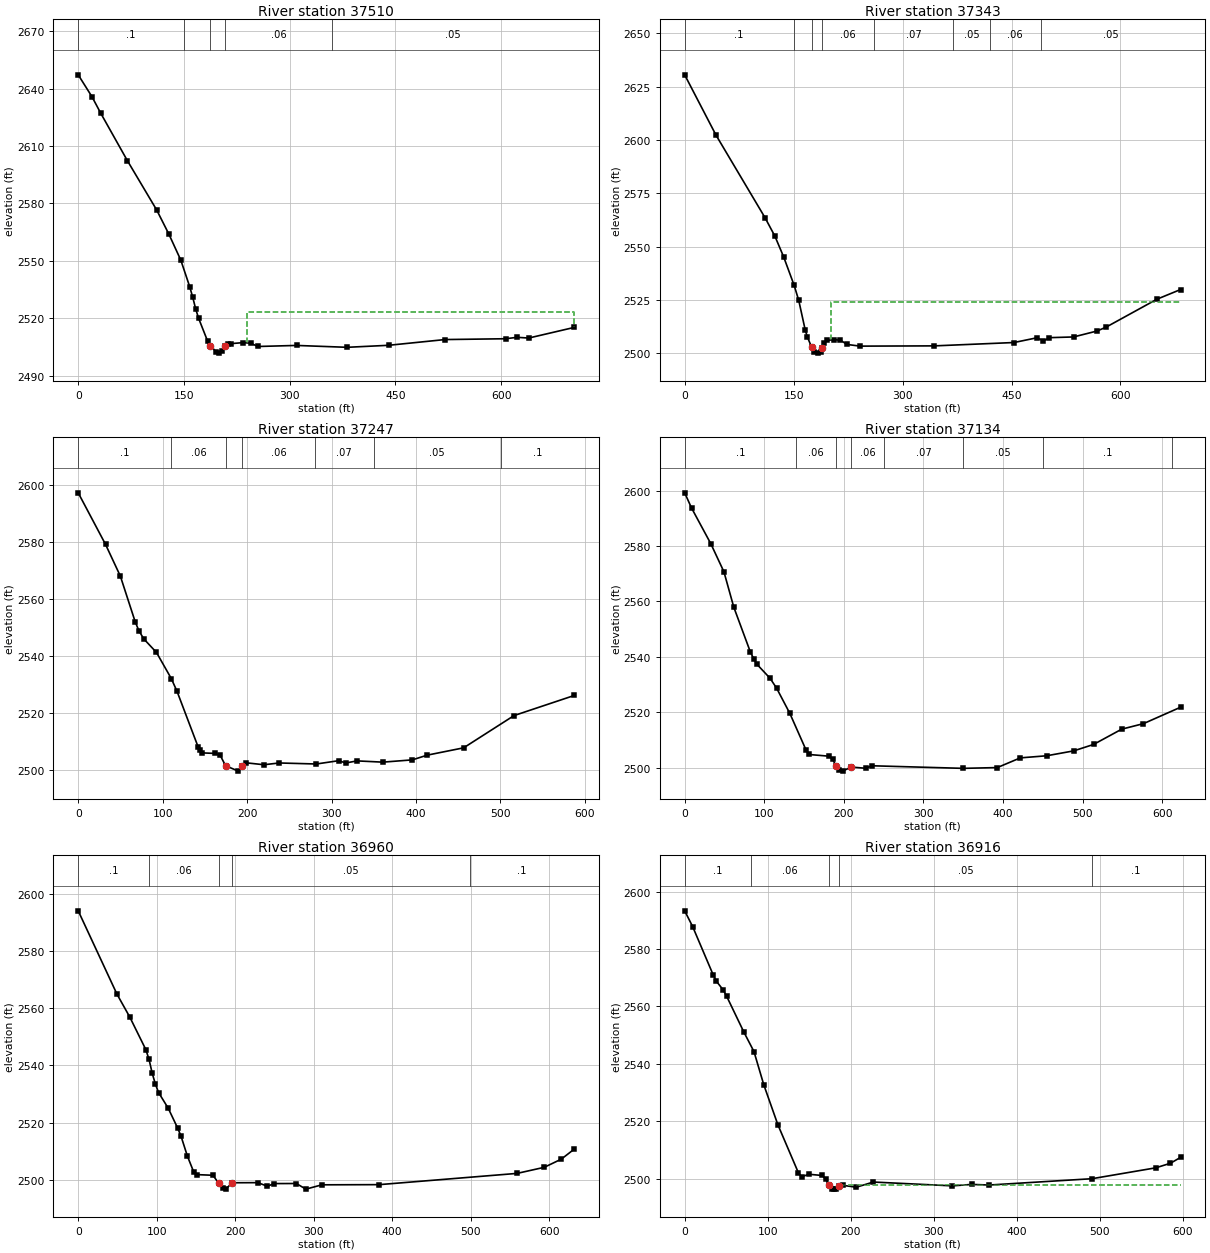
Type RM Length L Ch R = 1 ,37510   ,167.9,167,163
XS GIS Cut Line= 3
2228553.82395069404367.3743956192229053.10396921404203.488588014
2229227.15323775404165.375609502
#Sta/Elev= 30
       0 2647.22    19.5 2635.79    32.1 2627.06    69.8 2602.33   111.4 2576.54
   128.8 2563.83   145.6 2550.33   158.2 2536.48   162.5 2530.94   166.7 2524.82
   170.9  2519.9   183.5 2508.12   187.7 2505.73   196.1 2502.22   200.1 2501.76
   204.6 2502.79   208.8 2505.28     213 2506.38   217.2 2506.74     234 2507.25
   244.5 2506.95   255.1 2505.23   309.8 2505.78   381.4  2504.8   440.3 2505.85
   520.4 2508.85   606.4 2509.28   622.8 2510.02   639.2 2509.64   703.7 2515.19
#Mann= 5 ,-1,0
       0      .1       0     150     .06       0   187.7    .045       0
   208.8     .06       0     360     .05       0
#XS Ineff= 2 , 0
                          238.84         2523.39
Permanent Ineff=
       F       F
Bank Sta=187.7,208.8
XS Rating Curve= 0 ,0
Exp/Cntr(USF)=0,0
Exp/Cntr=0.3,0.1

Type RM Length L Ch R = 1 ,37343   ,95.1,96.4,99.5
XS GIS Cut Line= 3
2228657.91543891404534.6675022632229096.31627717404306.693695265
2229279.90493213404263.137770949
#Sta/Elev= 30
       0 2630.56    43.1 2602.31   110.8 2563.49   124.3 2554.88   136.3  2545.2
   150.6    2532     157 2524.89   165.9 2511.06   168.9 2507.68   174.8 2502.91
   178.4 2500.84   182.9 2500.12   187.4 2500.69   189.6 2502.66   191.9 2504.72
   195.6 2506.06   205.4 2506.45   214.4 2506.19   223.5 2504.19   241.5  2503.4
   343.9 2503.52   453.4 2505.09     485 2507.31     494 2505.84   502.2 2507.37
   535.4  2507.7     568 2510.51   580.3 2512.32   650.2 2525.39   682.8 2529.94
#Mann= 8 ,-1,0
       0      .1       0     150     .06       0   174.8    .045       0
   189.6     .06       0     260     .07       0     370     .05       0
     420     .06       0     490     .05       0
#XS Ineff= 2 , 0
                          201.24         2524.01
Permanent Ineff=
       F       F
Bank Sta=174.8,189.6
XS Rating Curve= 0 ,0
Exp/Cntr=0.3,0.1

Type RM Length L Ch R = 1 ,37247   ,111.7,112.8,115
XS GIS Cut Line= 3
2228730.54693623404581.9840362022229123.77440193404406.975542214
2229270.90226289404352.165738576
#Sta/Elev= 30
       0 2597.11    32.4    2579    49.9 2567.91    67.5 2551.87    71.8 2548.81
    77.6 2545.91    92.7 2541.14   110.2    2532     117 2527.53   141.9 2508.11
   144.2 2506.78   146.3 2505.92   162.4 2505.73   168.2 2505.05   174.5 2501.42
   189.7 2499.52   194.4 2501.23   198.8 2502.44     220 2501.76   238.1 2502.38
     282 2502.02   308.3 2503.17     317 2502.38   330.2 2503.11   360.8 2502.67
   395.8 2503.47   413.3 2505.12   456.5 2507.69   516.2    2519   587.4 2526.04
#Mann= 7 ,-1,0
       0      .1       0     110     .06       0   174.5    .045       0
   194.4     .06       0     280     .07       0     350     .05       0
  500.41      .1       0
Bank Sta=174.5,194.4
XS Rating Curve= 0 ,0
Exp/Cntr(USF)=0,0
Exp/Cntr=0.3,0.1

Type RM Length L Ch R = 1 ,37134   ,173.2,173.8,174.9
XS GIS Cut Line= 3
2228752.49280191404660.0678226092229198.98578714 404541.87850299
2229314.78744374404429.658340928
#Sta/Elev= 30
       0 2599.18     8.6 2593.72    32.8 2580.84    49.3  2570.7    61.7 2557.93
    82.4 2541.86    86.6 2539.37    90.7 2537.35   107.3 2532.27   115.5 2528.71
   132.1 2519.62   152.6 2506.32   155.9 2504.79   181.7 2504.16   185.9 2503.05
     190 2500.73   194.1 2499.03   198.3 2498.78   209.3 2500.24   227.2 2499.82
   235.5 2500.71     350 2499.78   392.8 2500.06   421.7 2503.56   454.8 2504.32
   488.7 2506.08   513.7  2508.4   549.1 2513.92   576.4 2515.91   623.1 2521.84
#Mann= 8 ,-1,0
       0      .1       0     140     .06       0     190    .045       0
   209.3     .06       0     250     .07       0     350     .05       0
     450      .1       0  611.87     .05       0
Bank Sta=190,209.3
XS Rating Curve= 0 ,0
Exp/Cntr(USF)=0,0
Exp/Cntr=0.3,0.1

Type RM Length L Ch R = 1 ,36960   ,44.5,44.2,44
XS GIS Cut Line= 3
2228799.69350661404815.033803984 2229210.3715465404733.853261215
2229407.35374587404652.672718447
#Sta/Elev= 30
       0 2594.18    49.4 2564.97    65.7 2556.96    86.1 2545.58    90.2 2542.13
    94.3 2537.24    98.3 2533.47   102.4 2530.51   114.7    2525   126.9 2517.94
     131  2515.2   139.1 2508.23   147.3 2502.58   151.4 2501.77   171.7 2501.54
     179 2498.69     184 2497.07   188.1  2496.7     196 2498.92   228.8 2498.96
   241.1 2497.69   249.2 2498.63   277.8 2498.66     290 2496.69   310.4  2498.2
   383.3 2498.26     559  2502.2   593.6 2504.33   615.3 2507.19   631.7 2510.68
#Mann= 5 ,-1,0
       0      .1       0      90     .06       0     179    .045       0
     196     .05       0  498.62      .1       0
Bank Sta=179,196
XS Rating Curve= 0 ,0
Exp/Cntr(USF)=0,0
Exp/Cntr=0.5,0.3

Type RM Length L Ch R = 1 ,36916   ,40.1,40.1,41.7
XS GIS Cut Line= 3
2228814.84125853404863.4144135032229194.85835692404774.511234082
2229379.08608746404679.638897105
#Sta/Elev= 30
       0 2593.28     9.6 2587.79    34.2 2571.06    38.3 2568.71    46.6 2565.64
    50.7 2563.43    71.2 2551.09    83.5 2544.23    95.3 2532.67   112.3 2518.73
   136.9 2502.08     141 2500.56   149.3  2501.5   165.7 2501.06   169.8 2499.82
   173.9 2497.79     178 2496.34   179.4 2496.31   182.7 2496.46   186.2 2497.33
   190.3 2497.64   206.8 2496.98   227.3 2498.78   322.6 2497.45   345.9 2497.95
     367 2497.74   490.7 2499.94   567.5 2503.73   585.3 2505.33   597.5 2507.39
#Mann= 5 ,-1,0
       0      .1       0      80     .06       0   173.9    .045       0
   186.2     .05       0  490.28      .1       0
#XS Ineff= 2 , 0
          173.13 2497.99  187.87         2497.78
Permanent Ineff=
       F       F
Bank Sta=173.9,186.2
XS Rating Curve= 0 ,0
Exp/Cntr=0.5,0.3