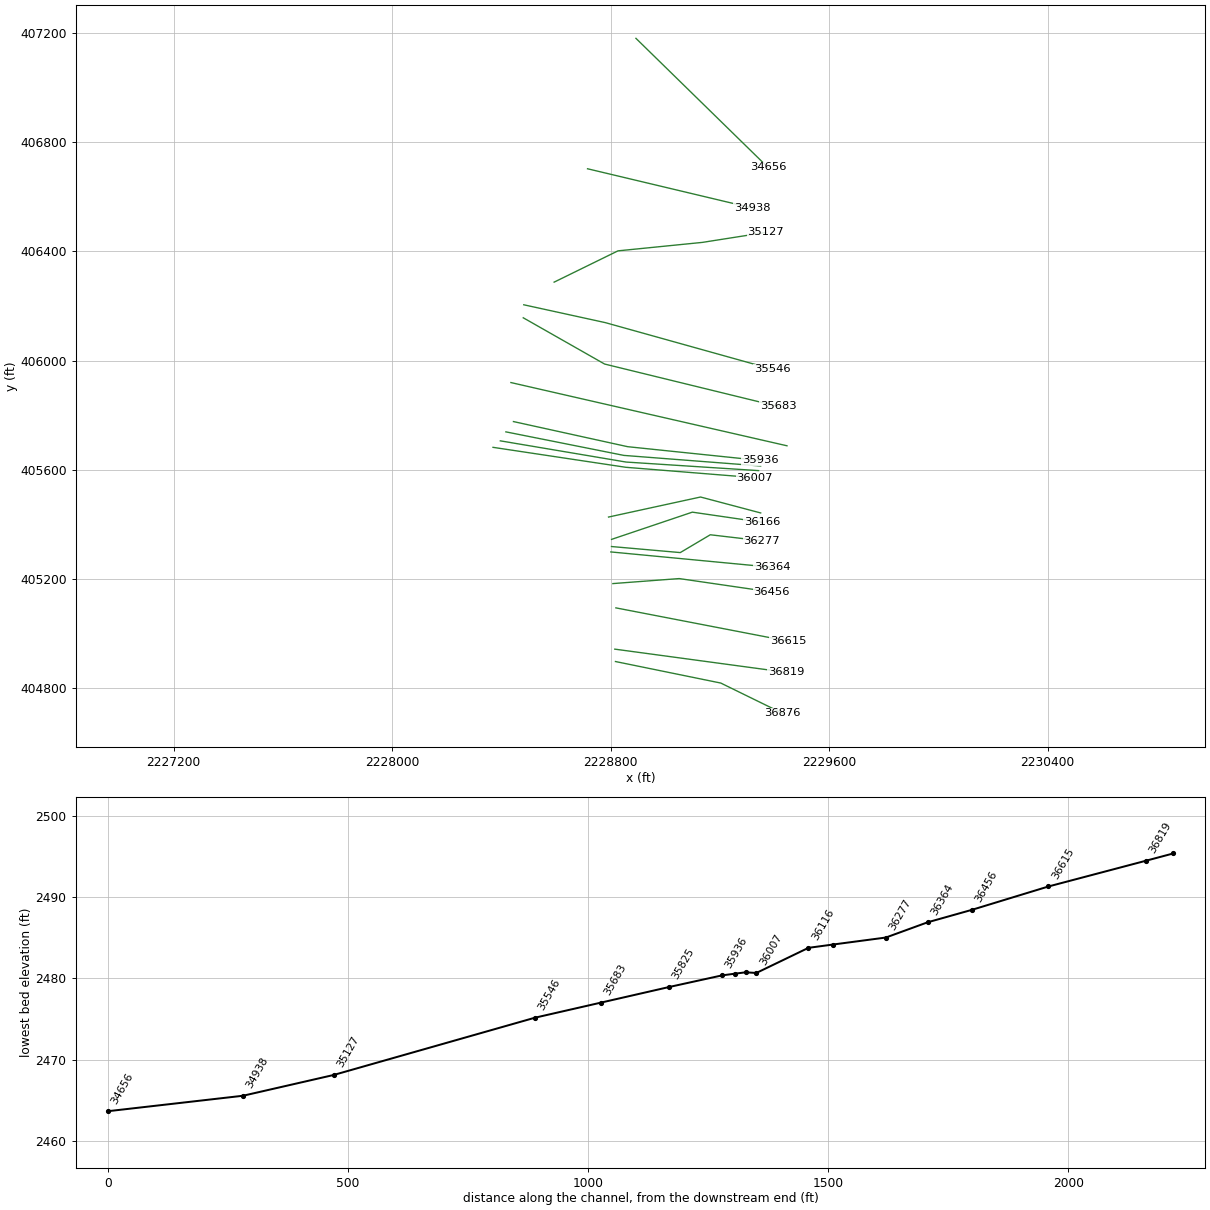
HEC-RAS study BEAVERCK.prj: BEAVERCK

--- BEAVERCK.g01 (geometry) --- (continued)

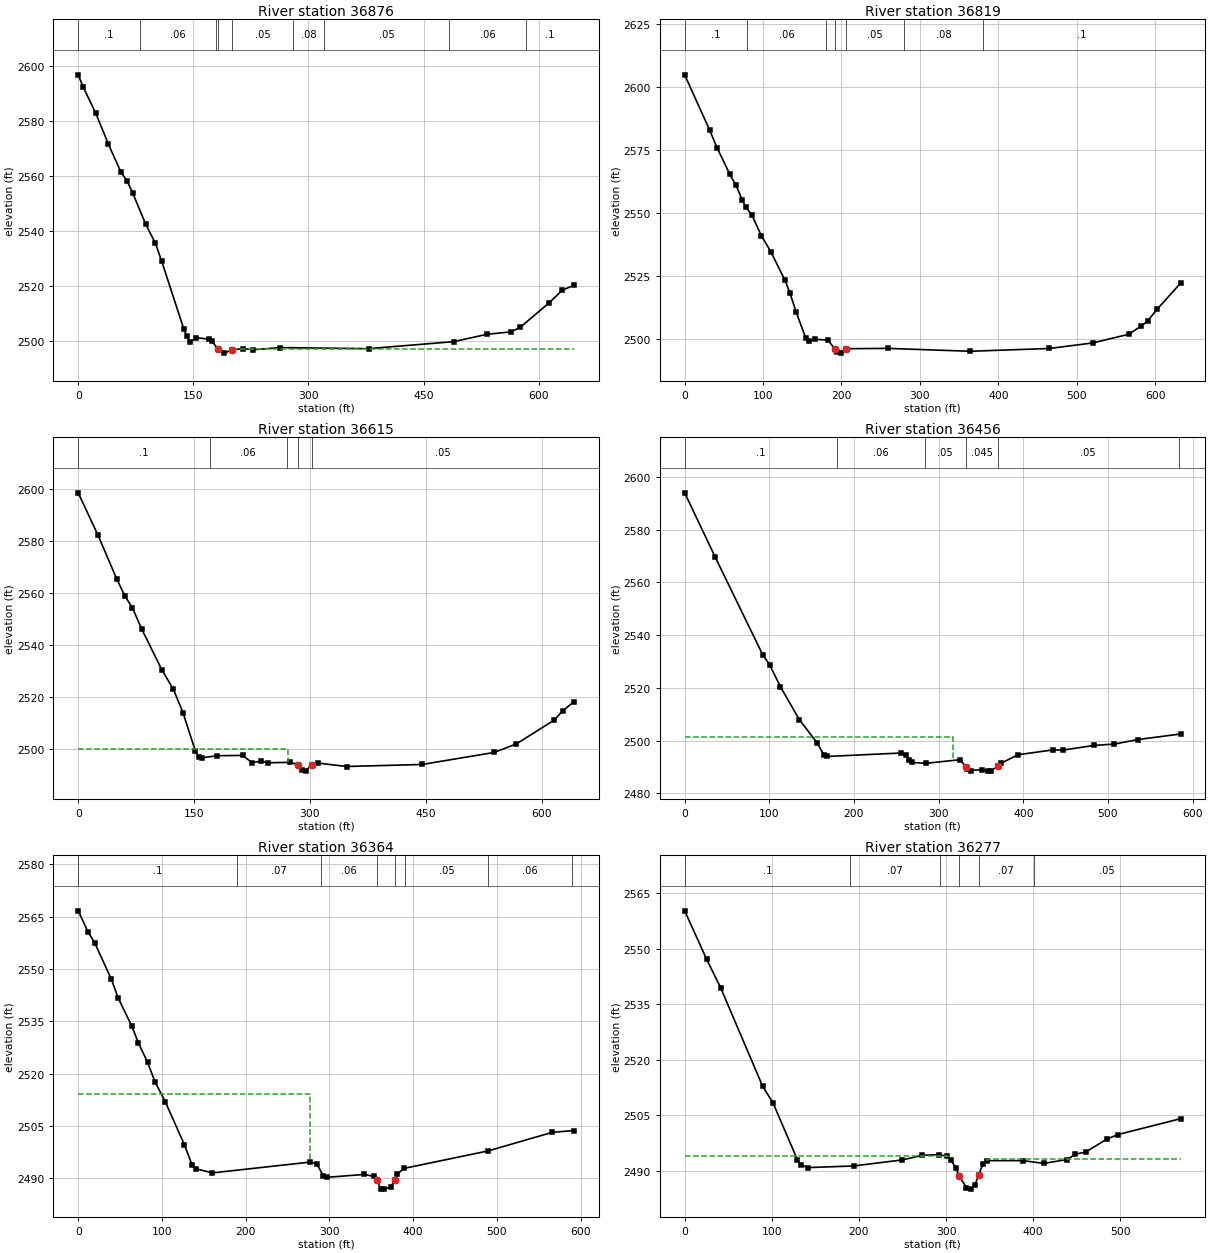
Type RM Length L Ch R = 1 ,36876   ,56.6,57,58.4
XS GIS Cut Line= 3
2228817.60097928404898.6020097742229203.20855743404819.809130029
2229430.03654458404708.782799478
#Sta/Elev= 30
       0  2596.9     6.7 2592.32      23 2582.83    39.4 2571.55    55.7 2561.41
    63.9 2558.07    71.2 2553.65    88.1 2542.35   100.6 2535.45   108.8 2528.91
   137.4 2504.34   141.4 2501.52   145.5 2499.42   153.7 2501.03     170 2500.56
   174.1 2499.81   182.3 2496.87   190.4 2495.43     200 2496.58   214.9 2497.09
   227.2 2496.66   263.2 2497.44   378.2 2497.06     489 2499.61   532.7 2502.31
   563.9 2503.19   575.7  2504.8   612.9 2513.64   630.7 2518.38   646.1 2520.19
#Mann= 9 ,-1,0
       0      .1       0      80     .06       0     180     .05       0
   182.3    .045       0     200     .05       0     280     .08       0
     320     .05       0  483.58     .06       0  583.58      .1       0
#XS Ineff= 2 , 0
          181.79 2496.94  201.08         2496.88
Permanent Ineff=
       F       F
Bank Sta=182.3,200
XS Rating Curve= 0 ,0
Exp/Cntr(USF)=0,0
Exp/Cntr=0.5,0.3

Type RM Length L Ch R = 1 ,36819   ,185.8,203.3,193.9
XS GIS Cut Line= 2
2228815.21331626404943.9676072042229441.97485969404859.205569902
#Sta/Elev= 30
       0 2604.88    31.8    2583    41.3 2575.97    57.5  2565.5    65.6    2561
    73.6 2555.09      78 2552.45    85.7 2549.27    97.8 2541.13     110 2534.66
   127.8 2523.49   134.2 2518.46   142.2 2510.78   154.4 2500.54   158.4 2499.23
   166.5 2500.02   182.6 2499.67   191.8 2496.09   194.7 2495.01   198.8 2494.53
     206 2496.28   259.3 2496.41   364.2 2495.27   465.2 2496.37   520.6 2498.58
   566.1 2501.99   582.2 2505.27   590.3 2507.21   602.4 2511.89   632.5 2522.28
#Mann= 7 ,-1,0
       0      .1       0      80     .06       0     180     .05       0
   191.8    .045       0     206     .05       0     280     .08       0
     380      .1       0
Bank Sta=191.8,206
XS Rating Curve= 0 ,0
Exp/Cntr(USF)=0,0
Exp/Cntr=0.3,0.1

Type RM Length L Ch R = 1 ,36615   ,156,159.8,161.1
XS GIS Cut Line= 2
2228819.24024587405095.0585302422229449.58328384 404973.28771609
#Sta/Elev= 30
       0 2598.44    25.4 2582.28    49.8 2565.35    60.4 2558.77    70.2 2554.17
    82.4  2545.9   108.2 2530.37   123.2 2522.83   135.6 2513.89   151.7 2499.09
   155.8 2496.96   159.8 2496.47   180.2 2497.28   212.8 2497.39     225 2494.62
   237.2  2495.2   245.4 2494.56   273.9 2494.73   284.1  2493.9   290.2 2491.74
   294.3 2491.35   302.4 2493.85   310.6 2494.44   347.3 2493.13     445 2493.91
   538.5 2498.54   567.2 2501.83   616.1 2510.97   627.2 2514.54     642 2518.13
#Mann= 5 ,-1,0
       0      .1       0     170     .06       0     270     .05       0
   284.1    .045       0   302.4     .05       0
#XS Ineff= 2 , 0
          271.12 2499.92
Permanent Ineff=
       F       F
Bank Sta=284.1,302.4
XS Rating Curve= 0 ,0
Exp/Cntr(USF)=0,0
Exp/Cntr=0.3,0.1

Type RM Length L Ch R = 1 ,36456   ,91.6,91.8,85.9
XS GIS Cut Line= 3
2228808.19279247405183.9802500512229050.98658151405202.330943409
2229389.76861274405152.925230522
#Sta/Elev= 30
       0  2593.9    36.1 2569.52    92.2 2532.55   100.3  2528.8     113 2520.51
   135.4 2508.02   156.4 2499.18   164.4 2494.66   168.5 2494.02   256.1 2495.33
   260.9 2494.47   264.9 2492.57   268.9 2491.73   285.1 2491.42   325.5  2492.8
     3322490.191   333.7 2489.34   337.7 2488.66   351.4 2489.07   357.9 2488.46
   361.9 2488.65     370 2490.22     374 2491.47   393.7 2494.66   434.7 2496.49
   446.8 2496.42   483.2 2498.18   507.4  2498.7   535.7 2500.44   585.9 2502.53
#Mann= 6 ,-1,0
       0      .1       0     180     .06       0  283.49     .05       0
     332    .045       0     370     .05       0  583.49     .06       0
#XS Ineff= 2 , 0
           317.1 2501.44
Permanent Ineff=
       F       F
Bank Sta=332,370
XS Rating Curve= 0 ,0
Exp/Cntr(USF)=0,0
Exp/Cntr=0.3,0.1

Type RM Length L Ch R = 1 ,36364   ,80.9,87,98.8
XS GIS Cut Line= 2
2228800.65454098405299.8807754052229390.40730756405243.770694375
#Sta/Elev= 30
       0  2566.7    11.6 2560.71    19.6 2557.57    39.7 2547.03    47.7 2541.72
    63.8 2533.78      72 2528.78    82.8  2523.3    91.9 2517.58     104 2511.98
   126.8 2499.69   136.1  2493.8   140.2  2492.8   160.2 2491.58   277.2 2494.68
   284.8 2494.26   292.8 2490.73   296.9 2490.31   341.1 2491.13   353.1 2490.61
   357.1 2489.49   361.1 2486.98     365 2486.93   373.2 2487.54   378.4 2489.67
   381.2 2491.29   389.3 2492.88     490  2497.9   566.1  2503.2   592.4 2503.73
#Mann= 8 ,-1,0
       0      .1       0     190     .07       0     290     .06       0
   357.1    .045       0   378.4     .06       0     390     .05       0
     490     .06       0     590     .05       0
#XS Ineff= 2 , 0
          276.53 2514.17
Permanent Ineff=
       F       F
Bank Sta=357.1,378.4
XS Rating Curve= 0 ,0
Exp/Cntr(USF)=0,0
Exp/Cntr=0.5,0.3

Type RM Length L Ch R = 1 ,36277   ,114.1,111,108.3
XS GIS Cut Line= 4
2228803.14691705405319.6583151132229054.94065289405297.493112383
2229164.83641801405362.7077440542229352.25980064405340.789107401
#Sta/Elev= 30
       0 2560.27    25.1 2547.22    41.2 2539.53    89.4  2512.9   101.4 2508.36
   129.5 2492.93   133.5  2491.6   141.6 2490.87   193.8 2491.31     250 2492.95
   272.8 2494.18   291.5 2494.37   300.7 2493.96   305.4 2492.95   311.8 2490.65
   314.9 2488.63   323.5 2485.47   328.6 2485.05   333.3 2486.12   337.3 2488.88
   342.6 2491.94   347.2 2492.74   388.5 2492.75   412.1    2492     439 2493.05
   448.4 2494.47   460.7 2495.12   484.6 2498.56     497 2499.78   569.3 2504.09
#Mann= 6 ,-1,0
       0      .1       0     190     .07       0  292.77     .06       0
   314.9    .045       0   337.3     .07       0  400.56     .05       0
#XS Ineff= 2 , 0
           301.7    2494  346.98          2493.3
Permanent Ineff=
       F       F
Bank Sta=314.9,337.3
XS Rating Curve= 0 ,0
Exp/Cntr=0.5,0.3

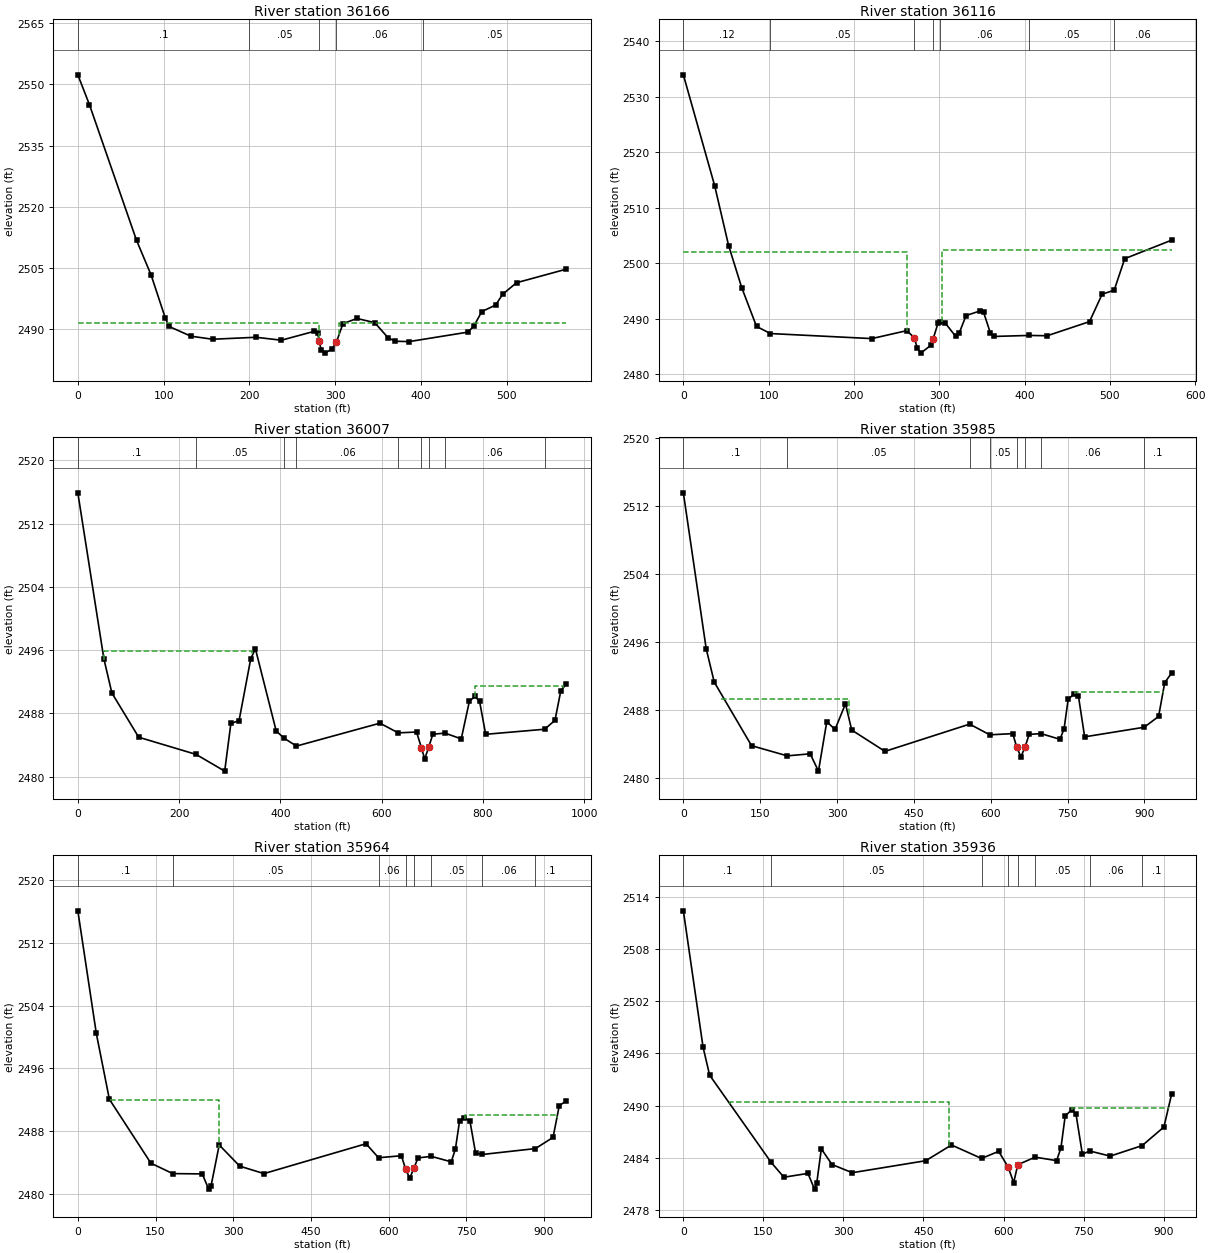
Type RM Length L Ch R = 1 ,36166   ,51.6,50.1,48.4
XS GIS Cut Line= 3
2228803.39529909405345.8684589362229099.11241881405445.528219784
2229353.39853071405408.519442933
#Sta/Elev= 30
       0  2552.3    13.5 2545.01    68.4 2511.79    85.3 2503.35   102.1 2492.66
   106.3 2490.71   131.7 2488.33     157 2487.58   207.7 2488.06   237.2 2487.34
   275.2  2489.5   279.4 2489.13   281.4 2487.04   283.6  2484.9   287.9 2484.18
   296.3 2485.21   301.32486.882     309 2491.41   325.3 2492.66     346 2491.64
   361.6 2487.92   369.8 2487.09   385.9    2487   454.6 2489.32   461.5 2490.83
   470.8 2494.36   486.9 2495.95     495 2498.58   511.2 2501.41     569 2504.72
#Mann= 5 ,-1,0
       0      .1       0     200     .05       0   281.4    .045       0
   301.3     .06       0  402.06     .05       0
#XS Ineff= 2 , 0
          280.56 2491.54  304.08         2491.66
Permanent Ineff=
       F       F
Bank Sta=281.4,301.3
XS Rating Curve= 0 ,0
Exp/Cntr(USF)=0,0
Exp/Cntr=0.5,0.3

Type RM Length L Ch R = 1 ,36116   ,111.7,108.5,104.8
XS GIS Cut Line= 3
 2228792.2977204405427.6207471142229129.12086949405500.979161305
2229349.30317609405442.617156679
#Sta/Elev= 30
       0 2533.96    36.7 2513.97    53.1 2503.15    68.4  2495.6    85.8 2488.59
   102.1 2487.31   220.9  2486.4   261.9 2487.83   270.82486.563   274.2 2484.71
   278.3 2483.78   290.3  2485.2   292.72486.278   298.7 2489.23   301.4 2489.44
   306.9 2489.23   319.2 2486.82   323.3 2487.36   331.5 2490.56   347.9 2491.39
     352 2491.14   360.1 2487.35   364.4 2486.79   405.6 2486.97   426.5 2486.91
   476.2 2489.46     491 2494.41   505.1 2495.12   517.5 2500.81   572.5 2504.15
#Mann= 7 ,-1,0
       0     .12       0   102.1     .05       0   270.8    .045       0
   292.7     .05       0   301.4     .06       0   405.6     .05       0
   505.1     .06       0
#XS Ineff= 2 , 0
       0   261.9    2502   302.8       0 2502.36
Permanent Ineff=
       F       F
Bank Sta=270.8,292.7
XS Rating Curve= 0 ,0
Exp/Cntr(USF)=0,0
Exp/Cntr=0.3,0.1

Type RM Length L Ch R = 1 ,36007   ,22.3,22.4,22.5
XS GIS Cut Line= 3
2228369.35105278405682.8420958912228855.37975823405609.806136989
2229326.55056727405571.838315491
#Sta/Elev= 30
       0  2515.9    51.4 2494.91    67.2 2490.57   120.2 2484.97   233.4  2482.8
     290 2480.68   302.2 2486.71   318.4 2487.08   341.5 2494.92   350.7 2496.15
   391.7 2485.76   407.3 2484.85   431.6 2483.85   596.6 2486.75   632.7 2485.52
   668.9 2485.63   678.5 2483.63   684.9 2482.23   692.9 2483.71     701 2485.35
     725 2485.49   757.1 2484.76   773.2 2489.53   784.1 2490.13   793.3 2489.52
   805.3 2485.34   921.7 2485.98   942.2 2487.11   953.8 2490.88   964.2 2491.66
#Mann= 9 ,-1,0
       0      .1       0   233.4     .05       0   407.3      .1       0
   431.6     .06       0   632.7     .05       0   678.5    .045       0
   692.9     .05       0     725     .06       0   921.7      .1       0
#XS Ineff= 2 ,-1
   52.23  344.09 2495.91  783.41  958.53 2491.49
Permanent Ineff=
       F       F
Bank Sta=678.5,692.9
XS Rating Curve= 0 ,0
Exp/Cntr(USF)=0,0
Exp/Cntr=0.5,0.3

Type RM Length L Ch R = 1 ,35985   ,21.4,21.2,21.1
XS GIS Cut Line= 3
2228396.16638034405706.6047520542228856.48275537405628.962961704
2229341.68830662405597.612356671
#Sta/Elev= 30
       0 2513.56    44.6 2495.17    60.3 2491.25   133.1 2483.76   202.8 2482.56
   247.5  2482.8   263.7 2480.76   279.9 2486.58   296.1 2485.68   316.4  2488.7
   328.6  2485.6   393.5 2483.09   558.7  2486.3   598.1 2485.04   642.9 2485.18
   650.8 2483.55   658.9 2482.45   666.9 2483.61   674.9 2485.09   698.1 2485.18
   735.1 2484.51   743.1 2485.77   751.1 2489.25   763.1 2489.87   771.1  2489.6
   783.2  2484.8   899.3 2485.93   927.5  2487.2   939.5 2491.19     953 2492.33
#Mann= 8 ,-1,0
       0      .1       0   202.8     .05       0   558.7     .06       0
   598.1     .05       0   650.8    .045       0   666.9     .05       0
   698.1     .06       0   899.3      .1       0
#XS Ineff= 4 ,-1
   73.73  322.58 2489.28   323.2  640.242484.573  678.65  761.47 2484.59
  763.44  938.56 2490.06
Permanent Ineff=
       F       F       F       F
Bank Sta=650.8,666.9
XS Rating Curve= 0 ,0
Exp/Cntr(USF)=0,0
Exp/Cntr=0.5,0.3

Type RM Length L Ch R = 1 ,35964   ,28.2,27.9,27.6
XS GIS Cut Line= 3
2228416.49792157 405739.477889882228848.44653731  405653.3178125
2229349.24922715405614.582795477
#Sta/Elev= 30
       0 2516.09    35.7 2500.45    60.9 2492.06   141.1 2483.91   183.2 2482.58
   240.3 2482.54   252.6  2480.6   257.1 2480.97     273 2486.23   312.6 2483.53
   359.4 2482.58   556.5 2486.39   580.6  2484.6   624.7 2484.86   632.8 2483.18
   640.8 2481.99   648.7 2483.24   656.8 2484.58   682.4 2484.78     721 2484.08
     729 2485.71   737.1  2489.3   745.1 2489.71   757.1 2489.29     768 2485.18
   781.2 2485.02   883.5 2485.77   917.6  2487.2   929.6 2491.26   942.8 2491.82
#Mann= 8 ,-1,0
       0      .1       0   183.2     .05       0   580.6     .06       0
   632.8    .045       0   648.7     .06       0   682.4     .05       0
   781.2     .06       0   883.5      .1       0
#XS Ineff= 4 ,-1
   61.44  271.89 2492.01  271.89  612.552484.168  660.61  738.792484.168
  748.08  924.73 2490.09
Permanent Ineff=
       F       F       F       F
Bank Sta=632.8,648.7
XS Rating Curve= 0 ,0
Exp/Cntr=0.5,0.3

Type RM Length L Ch R = 1 ,35936   ,112.4,110.6,109
XS GIS Cut Line= 3
2228444.11315941 405777.19444702 2228862.1487829405685.232411872
2229346.61754849405634.948228617
#Sta/Elev= 30
       0 2512.41    36.9 2496.73    49.2  2493.5   164.6 2483.45   188.5 2481.75
   233.5 2482.19   245.8 2480.38   249.9 2481.04   258.6 2485.01   278.6 2483.21
   316.6 2482.27   454.2 2483.65   502.5 2485.46   558.8 2483.91   590.9 2484.73
   608.4 2482.95   619.1 2481.13   626.7 2483.19   659.3 2484.06   699.5 2483.66
   707.6 2485.12   715.6  2488.8   727.7 2489.51   735.7 2489.07   747.8  2484.4
   761.5 2484.77     800 2484.18   859.8 2485.39   900.6 2487.53   915.1 2491.33
#Mann= 8 ,-1,0
       0      .1       0   164.6     .05       0   558.8     .06       0
   608.4    .045       0   626.7     .06       0   659.3     .05       0
   761.5     .06       0   859.8      .1       0
#XS Ineff= 2 ,-1
   87.56     498 2490.44  728.11  909.37 2489.73
Permanent Ineff=
       F       F
Bank Sta=608.4,626.7
XS Rating Curve= 0 ,0
Exp/Cntr(USF)=0,0
Exp/Cntr=0.3,0.1

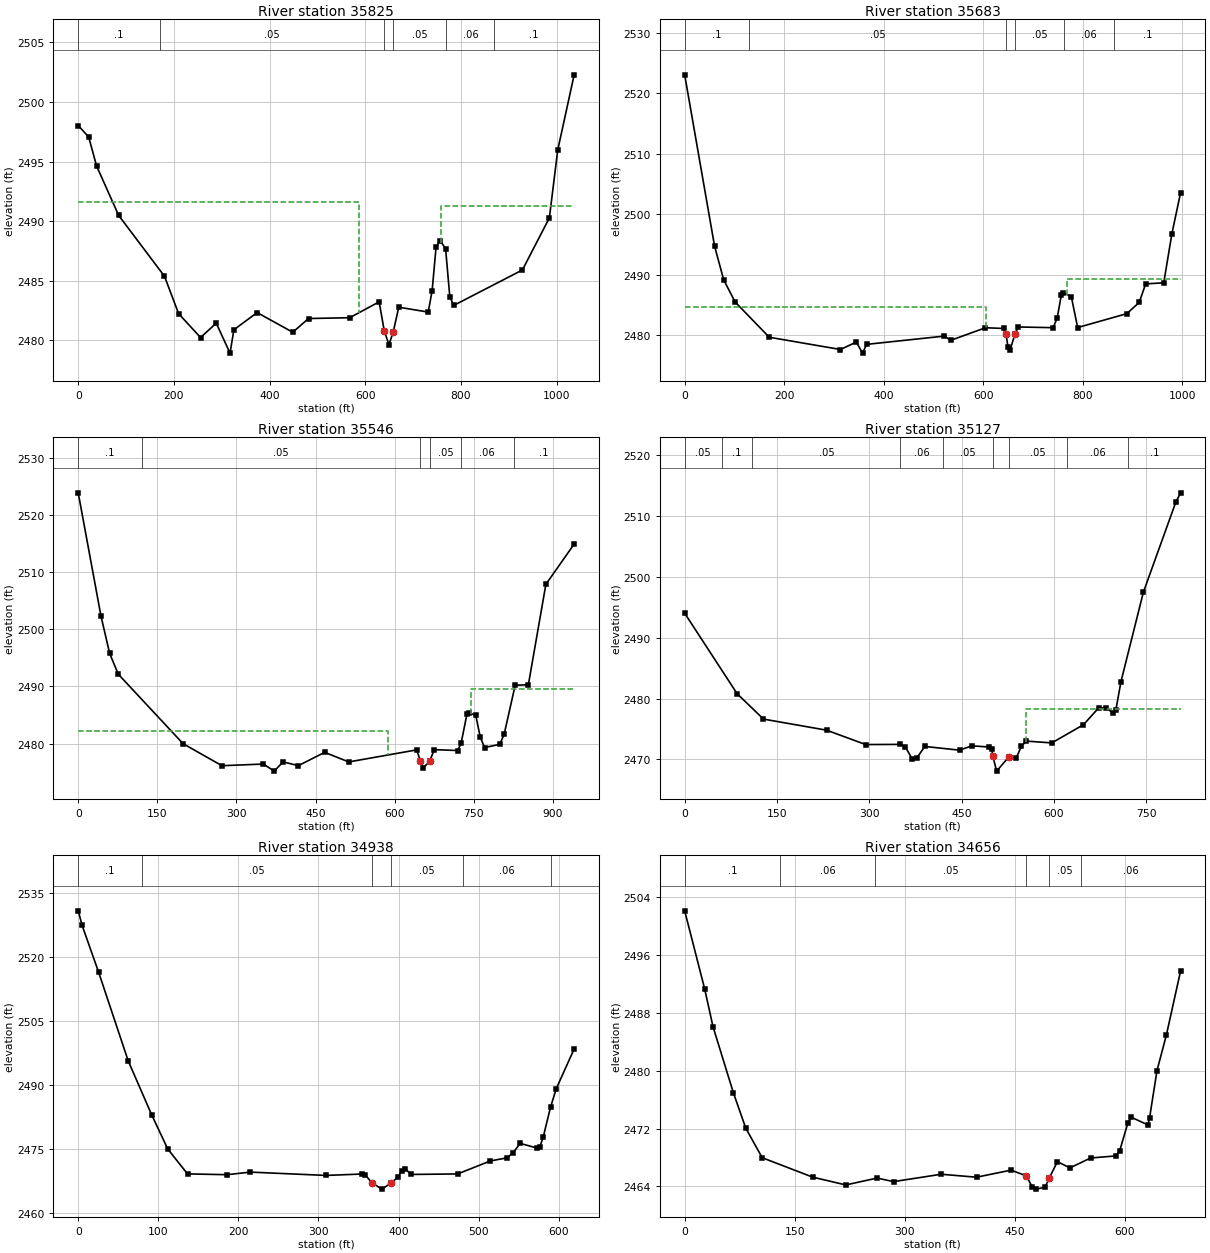
Type RM Length L Ch R = 1 ,35825   ,141.3,141.6,141
XS GIS Cut Line= 2
2228434.87088858405920.0346631782229445.57061507405688.533608508
#Sta/Elev= 30
       0 2498.02    21.9 2497.06    38.3 2494.64    84.5 2490.49   180.4 2485.38
   209.9 2482.25   255.8 2480.25   288.6 2481.45   317.4 2478.94   325.5  2480.9
   374.1 2482.34   448.6 2480.69   481.5 2481.84   567.7 2481.91   629.2 2483.24
   639.8 2480.82   649.7 2479.65   658.72480.733   670.2 2482.79   731.8 2482.38
     740 2484.19   748.2 2487.82   756.4 2488.38   768.1  2487.7   776.9 2483.67
   785.1 2482.94   928.7 2485.91   985.1 2490.28  1002.6 2495.97  1036.9 2502.27
#Mann= 6 ,-1,0
       0      .1       0     170     .05       0   639.8    .045       0
   658.7     .05       0     770     .06       0     870      .1       0
#XS Ineff= 2 , 0
          587.83  2491.6  759.42         2491.29
Permanent Ineff=
       F       F
Bank Sta=639.8,658.7
XS Rating Curve= 0 ,0
Exp/Cntr(USF)=0,0
Exp/Cntr=0.3,0.1

Type RM Length L Ch R = 1 ,35683   ,137.4,137.3,136.8
XS GIS Cut Line= 3
2228480.04182608406157.1820850362228777.88769519405987.791069423
2229413.10400374405832.515971778
#Sta/Elev= 30
       0 2523.07      60 2494.75    78.4 2489.14   101.4 2485.48   169.9 2479.65
   313.1 2477.62     345 2478.86   357.4 2477.02   365.6 2478.47   522.1 2479.84
   534.4 2479.13   604.4 2481.22   641.5  2481.1   645.6 2480.23   649.7 2478.03
   653.8 2477.47   663.8 2480.23   670.3 2481.35   740.5 2481.23   748.5 2482.83
   756.8 2486.59   760.9 2486.98   776.9 2486.39   789.7 2481.25   888.5 2483.55
   913.3 2485.41   926.4 2488.47   962.7 2488.66   979.1  2496.8   996.6 2503.59
#Mann= 6 ,-1,0
       0      .1       0     130     .05       0   645.6    .045       0
   663.8     .05       0  762.64     .06       0  862.64      .1       0
#XS Ineff= 2 , 0
          605.14 2484.64  769.08         2489.21
Permanent Ineff=
       F       F
Bank Sta=645.6,663.8
XS Rating Curve= 0 ,0
Exp/Cntr(USF)=0,0
Exp/Cntr=0.3,0.1

Type RM Length L Ch R = 1 ,35546   ,413,419.4,420.9
XS GIS Cut Line= 3
2228481.93112509406204.7896184322228780.39107193406139.464151167
 2229391.8528451405968.877144366
#Sta/Elev= 30
       0 2523.92    43.2 2502.31    59.6 2495.78      76 2492.14   198.8 2479.97
   272.5 2476.11     351  2476.4   371.7 2475.16   388.3 2476.78   417.4 2476.12
   467.3 2478.45   512.9 2476.77   641.7 2478.88  648.65 2476.96   654.6 2475.73
   666.6 2476.93   674.9 2478.92   719.6 2478.77   726.1 2480.11   737.2 2485.23
   741.3 2485.39   753.8 2484.92   762.1 2481.18   770.4 2479.29   799.5 2479.86
   807.8  2481.7   828.5 2490.21   853.5 2490.29   886.7 2507.89   940.3 2514.94
#Mann= 6 ,-1,0
       0      .1       0     120     .05       0  648.65    .045       0
   666.6     .05       0  725.53     .06       0  825.53      .1       0
#XS Ineff= 2 , 0
          587.67 2482.17  744.93         2489.49
Permanent Ineff=
       F       F
Bank Sta=648.65,666.6
XS Rating Curve= 0 ,0
Exp/Cntr=0.3,0.1

Type RM Length L Ch R = 1 ,35127   ,193.4,188.6,182.4
XS GIS Cut Line= 4
2228593.18914481 406287.730651232228826.88646501406402.226653747
2229135.74680346406433.1901370792229367.99770978406469.669504544
#Sta/Elev= 30
       0 2494.01    85.1 2480.81     128 2476.63   230.6 2474.81   294.1 2472.45
     350 2472.48     358 2472.13   370.1 2470.03   377.4  2470.3   390.2 2472.14
   446.5 2471.53   466.6 2472.24   494.7 2472.05   498.7 2471.72  500.67 2470.53
   506.8 2468.09   526.5 2470.41   538.9 2470.31     547 2472.17     555 2473.02
   596.4 2472.72   647.9 2475.71   672.3 2478.44   684.5 2478.49   696.6 2477.57
   700.5 2478.13   708.7 2482.74   745.2 2497.46   797.8 2512.22   805.7 2513.77
#Mann= 9 ,-1,0
       0     .05       0      60      .1       0     110     .05       0
  350.24     .06       0  420.24     .05       0  500.67    .045       0
   526.5     .05       0  620.65     .06       0  720.65      .1       0
#XS Ineff= 2 , 0
                          554.09         2478.31
Permanent Ineff=
       F       F
Bank Sta=500.67,526.5
XS Rating Curve= 0 ,0
Exp/Cntr(USF)=0,0
Exp/Cntr=0.3,0.1

Type RM Length L Ch R = 1 ,34938   ,291.7,281.8,272.8
XS GIS Cut Line= 2
2228715.37414299406702.7675013612229317.84937648406559.379258823
#Sta/Elev= 30
       0 2530.92     4.9 2527.48    25.5 2516.49    62.5 2495.63    91.7 2483.01
   111.8 2474.96   136.5 2469.11   185.9 2468.92   214.8 2469.53   309.2 2468.75
   354.4 2469.08   358.5 2468.85   366.8 2467.03   379.1 2465.53   390.6 2466.93
   399.7 2468.43   403.8  2469.9   407.9 2470.34   416.1 2468.98   473.8  2469.1
   514.8 2472.16   535.3 2472.87   543.4 2474.13   551.8 2476.29   572.4  2475.2
   576.5 2475.49   580.6 2477.71   589.8 2484.78     597 2489.15   619.3 2498.46
#Mann= 6 ,-1,0
       0      .1       0      80     .05       0   366.8    .045       0
   390.6     .05       0     480     .06       0     590      .1       0
Bank Sta=366.8,390.6
XS Rating Curve= 0 ,0
Exp/Cntr=0.3,0.1

Type RM Length L Ch R = 1 ,34656   ,93.3,94.5,95.9
XS GIS Cut Line= 2
2228892.60292328407180.3248668632229376.10468535406707.567588391
#Sta/Elev= 30
       0 2502.15    27.4 2491.28    38.6 2486.12    66.5 2476.93    83.3 2472.06
   105.7 2467.97   174.5 2465.28   219.7  2464.2   262.2 2465.15   284.9 2464.66
   349.8 2465.68   397.9 2465.27   445.1 2466.25   465.8 2465.45   473.7 2463.97
   479.4 2463.62   491.3 2463.88   496.9 2465.11   508.2 2467.42   525.3 2466.56
   553.5 2467.93   588.1 2468.22   593.1 2468.92   604.4 2472.82   609.2 2473.56
   631.6 2472.51   633.9  2473.5     644 2480.04   656.8 2484.96   676.2 2493.85
#Mann= 6 ,-1,0
       0      .1       0     130     .06       0     260     .05       0
   465.8    .045       0   496.9     .05       0     540     .06       0
Bank Sta=465.8,496.9
XS Rating Curve= 0 ,0
Exp/Cntr(USF)=0,0
Exp/Cntr=0.5,0.3