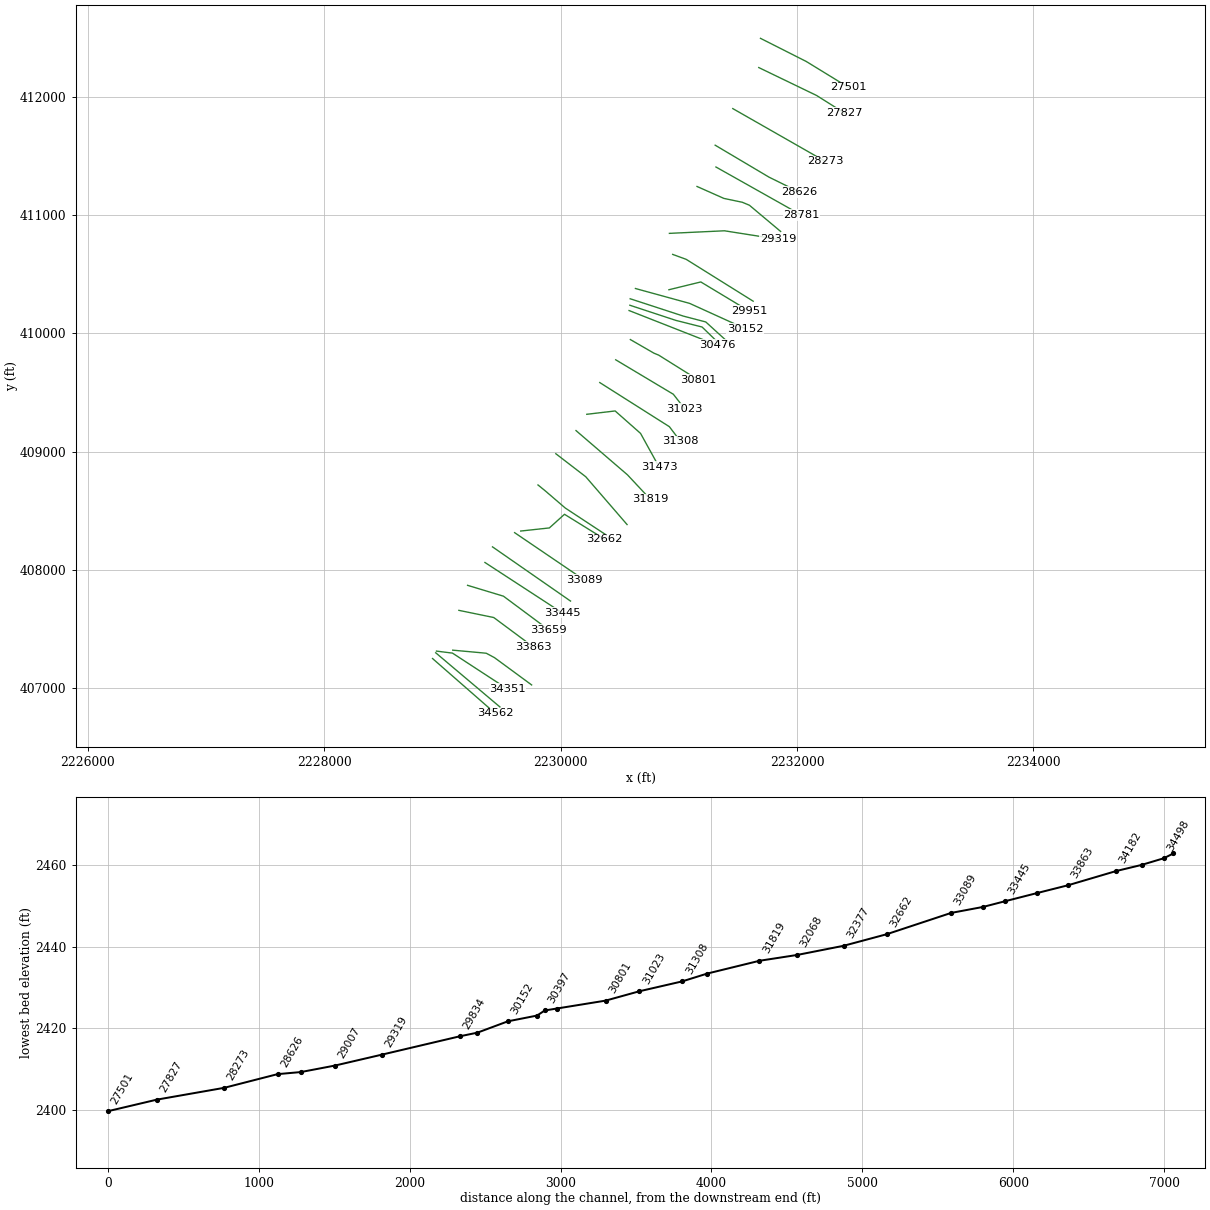
HEC-RAS study BEAVERCK.prj: BEAVERCK

--- BEAVERCK.g01 (geometry) --- (continued)

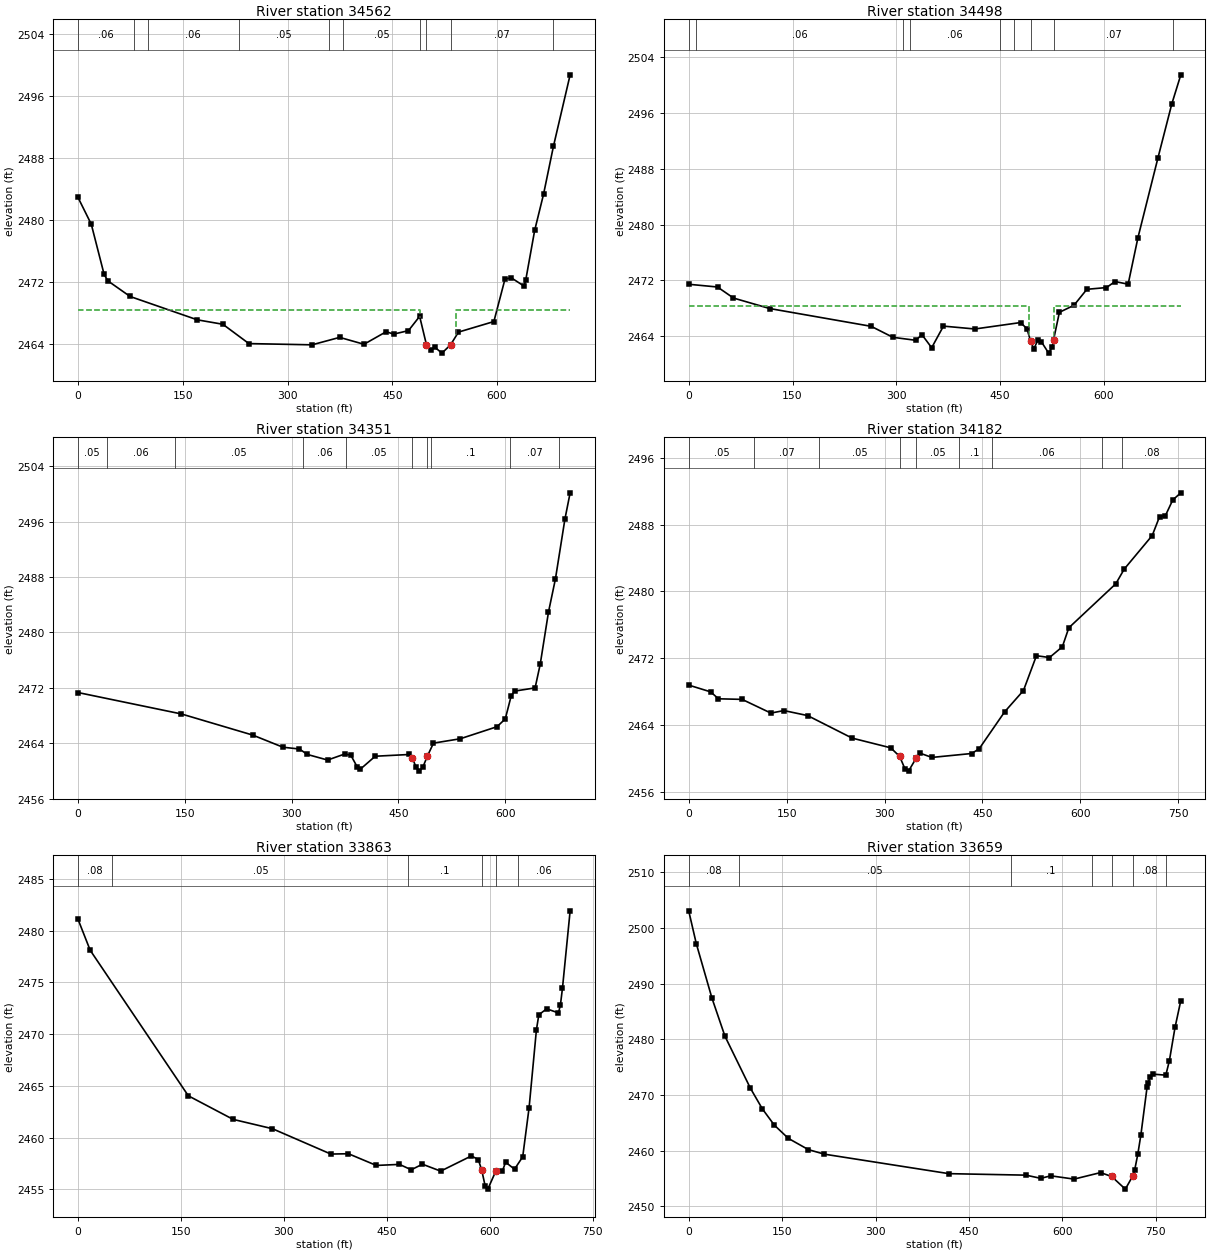
Type RM Length L Ch R = 1 ,34562   ,65.3,64.3,66.5
XS GIS Cut Line= 2
2228915.99177662 407249.677871022229446.42676554406785.666222633
#Sta/Elev= 30
       0 2482.87      19 2479.42    37.4 2472.95    42.8 2472.12    74.6 2470.11
   170.9  2467.1   207.4 2466.53   244.7 2464.04   335.1 2463.88   374.7 2464.84
   409.5 2463.95   441.3 2465.57     452 2465.26   473.2 2465.71   489.2 2467.55
   498.9 2463.91   505.1 2463.22   510.7 2463.59   521.1 2462.81   533.4 2463.87
   544.8 2465.52   595.5 2466.88   611.4 2472.35   620.4 2472.52   638.7 2471.45
   641.1 2472.21   653.9 2478.62   666.6 2483.28   680.8 2489.47   704.7 2498.68
#Mann= 10 ,-1,0
       0     .06       0      80      .1       0     100     .06       0
     230     .05       0     360     .06       0     380     .05       0
     490     .07       0   498.9    .045       0   533.4     .07       0
     680      .1       0
#XS Ineff= 2 , 0
          489.81  2468.4  541.89          2468.4
Permanent Ineff=
       F       F
Bank Sta=498.9,533.4
XS Rating Curve= 0 ,0
Exp/Cntr(USF)=0,0
Exp/Cntr=0.5,0.3

Type RM Length L Ch R = 1 ,34498   ,139.9,146.9,148.6
XS GIS Cut Line= 2
2228942.70529814407298.3068958692229486.06036225406839.934252615
#Sta/Elev= 30
       0 2471.46    41.6 2471.07    64.7 2469.49   117.1 2467.99   263.6 2465.45
     295 2463.88   328.3 2463.45   336.8 2464.28     351 2462.39     368 2465.48
   413.4 2465.07   479.4 2465.99   488.6 2465.11   493.8 2463.39   498.6 2462.22
   504.3 2463.47   509.5 2463.24     520 2461.62   525.2 2462.48     527 2463.49
   535.5 2467.45   556.6 2468.46   575.2 2470.74   603.5 2470.99   615.9 2471.85
   634.8 2471.47     649 2478.13   677.9 2489.53   697.9 2497.24   710.9 2501.39
#Mann= 9 ,-1,0
       0     .05       0      10     .06       0     310     .05       0
     320     .06       0     450     .05       0     470     .07       0
   493.8    .045       0     527     .07       0     700      .1       0
#XS Ineff= 2 , 0
          491.93  2468.4  527.86          2468.4
Permanent Ineff=
       F       F
Bank Sta=493.8,527
XS Rating Curve= 0 ,0
Exp/Cntr=0.5,0.3

Type RM Length L Ch R = 1 ,34351   ,168.1,168.7,169.5
XS GIS Cut Line= 3
2228949.54868636407312.4820151642229084.57530055407295.592412404
2229549.38734553406992.358100821
#Sta/Elev= 30
       0 2471.33   145.2 2468.24   245.4 2465.19   287.8 2463.44     311 2463.18
   321.9  2462.4   350.5 2461.59   374.8 2462.47   383.2 2462.27   391.9 2460.63
   396.7 2460.29   417.4 2462.14   465.1 2462.39   469.62461.891   474.7 2460.54
   479.5 2459.99   484.2 2460.54   490.52462.129   499.2 2464.03   536.8 2464.66
   588.4  2466.4     600 2467.52   608.4 2470.88   613.2 2471.54   641.9    2472
   649.1 2475.42   660.7 2482.94   670.5 2487.75   683.8 2496.37   691.1 2500.15
#Mann= 10 ,-1,0
       0     .05       0      40     .06       0  136.08     .05       0
  316.08     .06       0  376.08     .05       0   469.6    .045       0
   490.5     .05       0  496.08      .1       0  606.08     .07       0
  676.08     .06       0
Bank Sta=469.6,490.5
XS Rating Curve= 0 ,0
Exp/Cntr(USF)=0,0
Exp/Cntr=0.3,0.1

Type RM Length L Ch R = 1 ,34182   ,321,318.9,313
XS GIS Cut Line= 4
2229086.75766763407320.4792887472229370.15870632407294.639782277
2229440.17543353407257.130821273 2229754.4171735 407026.24232798
#Sta/Elev= 30
       0 2468.79    33.6 2467.98    45.6 2467.15    81.8 2467.08   125.9 2465.44
     146 2465.74   182.2 2465.14   250.5 2462.44   309.6 2461.28   323.2 2460.25
   331.5 2458.73   336.8 2458.49     3492460.108   355.1 2460.62   372.6 2460.13
   433.5  2460.6     445 2461.16   484.1 2465.59   512.9 2468.14   532.8 2472.31
   552.8 2472.09   572.5 2473.38   582.4 2475.65   654.4 2480.92   667.3 2482.68
   710.2  2486.7   721.4 2488.95   730.2 2489.05   741.7 2490.96     754 2491.81
#Mann= 9 ,-1,0
       0     .05       0     100     .07       0     200     .05       0
   323.2    .045       0     349     .05       0  414.01      .1       0
  464.01     .06       0  634.01      .1       0  664.01     .08       0
Bank Sta=323.2,349
XS Rating Curve= 0 ,0
Exp/Cntr(USF)=0,0
Exp/Cntr=0.3,0.1

Type RM Length L Ch R = 1 ,33863   ,201.9,204.2,204.4
XS GIS Cut Line= 3
2229138.80855103407657.3613819892229433.83181231407596.662816271
2229767.65526869 407348.88164433
#Sta/Elev= 30
       0 2481.09    17.7  2478.1   160.7 2464.03     226 2461.75   283.2 2460.85
   368.3  2458.4     394 2458.43   434.6  2457.3   468.3  2457.4   485.5 2456.88
   501.7 2457.42   528.3 2456.75   573.1 2458.22   583.1 2457.87   588.1 2456.85
     593 2455.35     597 2455.01   608.4 2456.72     618 2456.72   622.9 2457.61
   635.9 2456.94   647.8 2458.13   657.1 2462.87   667.8 2470.42   671.3 2471.86
   682.7 2472.44   699.9 2472.04   702.8 2472.84   705.7 2474.41   716.9 2481.91
#Mann= 6 ,-1,0
       0     .08       0      50     .05       0   481.2      .1       0
   588.1    .045       0   608.4      .1       0   641.2     .06       0
Bank Sta=588.1,608.4
XS Rating Curve= 0 ,0
Exp/Cntr(USF)=0,0
Exp/Cntr=0.3,0.1

Type RM Length L Ch R = 1 ,33659   ,211.8,214.2,215.2
XS GIS Cut Line= 3
2229212.45754423 407868.994055162229515.95037282407777.240409308
 2229895.6693072407494.921498992
#Sta/Elev= 30
       0  2503.1    12.2  2497.2    37.3 2487.43    58.2 2480.58    99.1 2471.23
   118.3 2467.52   137.6 2464.59   160.1 2462.22   192.1 2460.21   217.8 2459.39
   417.7 2455.89   541.6 2455.62   565.2 2455.05   581.5  2455.5   618.8 2454.91
   661.3 2456.08   679.2 2455.38   701.1 2453.11   712.7  2455.4   716.1 2456.54
   721.1 2459.35   726.1 2462.86     736 2471.41   737.5 2472.19     741 2473.24
   746.2 2473.76   766.1 2473.58   771.8 2476.15   780.9 2482.15   790.2 2486.99
#Mann= 7 ,-1,0
       0     .08       0      80     .05       0  517.06      .1       0
  647.06     .08       0   679.2    .045       0   712.7     .08       0
  767.06     .06       0
Bank Sta=679.2,712.7
XS Rating Curve= 0 ,0
Exp/Cntr(USF)=0,0
Exp/Cntr=0.3,0.1

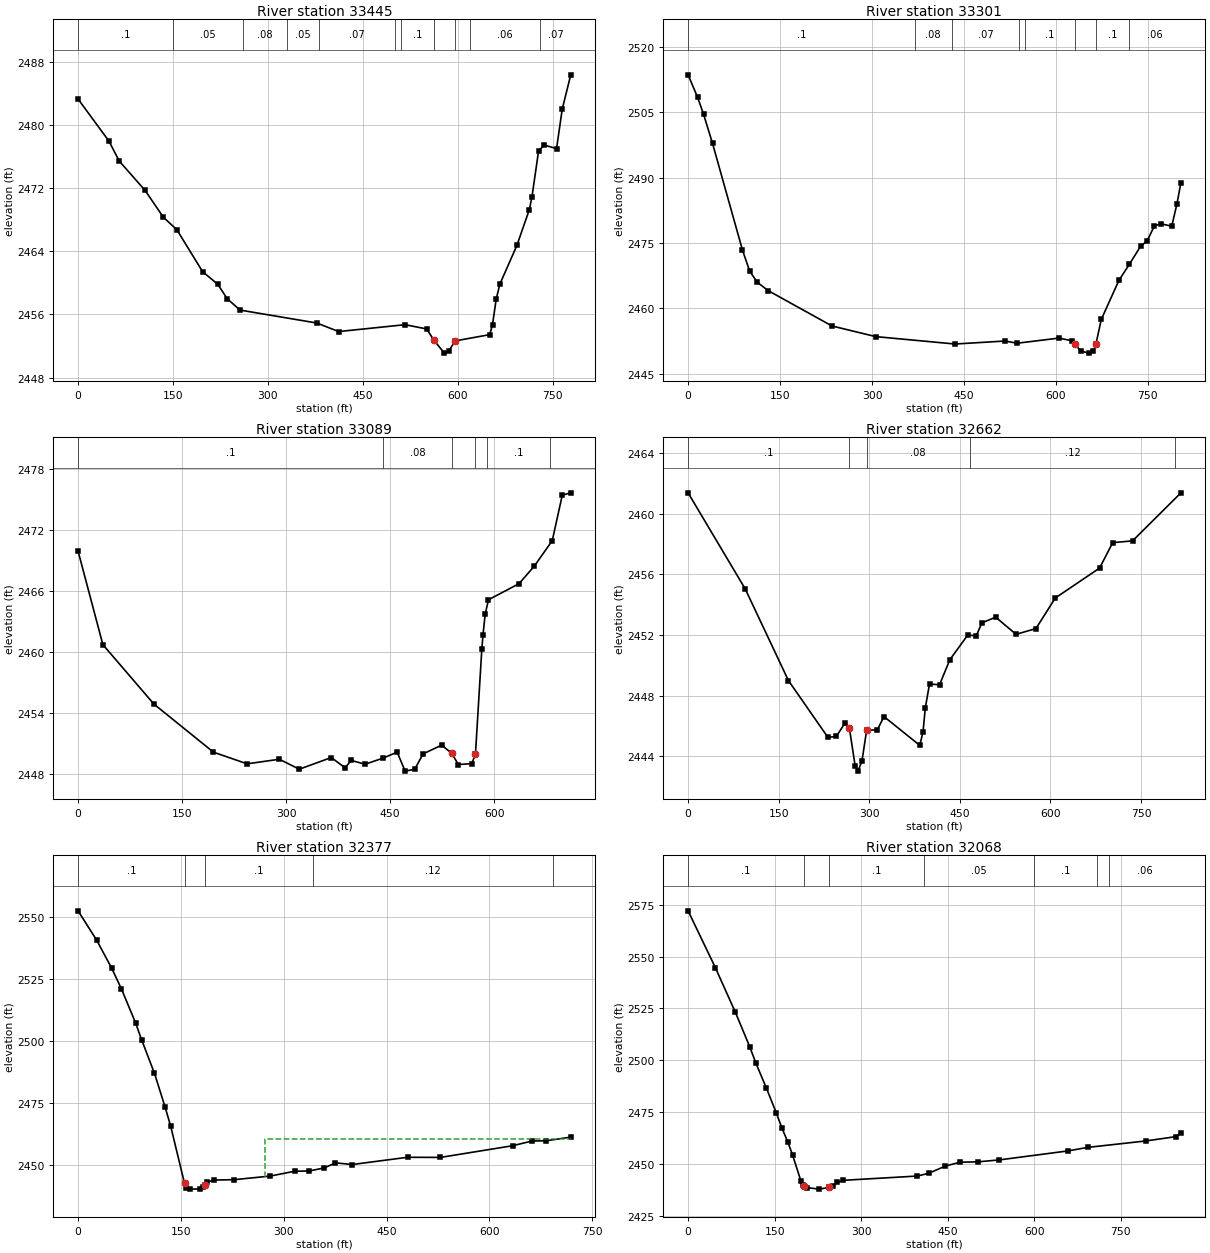
Type RM Length L Ch R = 1 ,33445   ,141.2,144.1,141.4
XS GIS Cut Line= 2
 2229359.2633776408062.3825087262230011.42006043407637.492548702
#Sta/Elev= 30
       0 2483.26    48.8 2477.93    65.1  2475.4   105.6 2471.72   134.8 2468.29
   156.1 2466.71   196.8  2461.4   220.7 2459.81   235.7 2457.97   255.9 2456.54
   377.3  2454.9   411.7 2453.82   516.7 2454.69   550.8 2454.15   562.3 2452.71
   578.7 2451.09   585.5 2451.32   595.8 2452.64   650.4 2453.43   654.8 2454.69
   660.6 2457.92   666.4 2459.82   693.3 2464.72     713 2469.26   717.2 2470.91
   727.6  2476.7   736.3 2477.43     756 2476.98   764.9 2481.96   778.4 2486.32
#Mann= 11 ,-1,0
       0      .1       0     150     .05       0     260     .08       0
     330     .05       0     380     .07       0     500     .08       0
     510      .1       0   562.3    .045       0   595.8      .1       0
     620     .06       0     730     .07       0
Bank Sta=562.3,595.8
XS Rating Curve= 0 ,0
Exp/Cntr(USF)=0,0
Exp/Cntr=0.3,0.1

Type RM Length L Ch R = 1 ,33301   ,211.5,212,212
XS GIS Cut Line= 2
2229423.39531524 408194.451720462230083.44900704407735.843010053
#Sta/Elev= 30
       0 2513.57    15.6 2508.38    25.3 2504.51    39.9 2497.82    88.6 2473.41
   100.4 2468.54     113 2465.94   130.8 2464.04   234.7 2455.94   306.1  2453.5
   435.4  2451.8   517.2 2452.49   536.7 2451.98     605 2453.16   626.1 2452.55
   630.9 2451.84   640.2 2450.22   653.6 2449.71   661.2 2450.15   665.4 2451.87
     674 2457.43   702.7 2466.38     720 2470.13   738.3 2474.27   748.7 2475.43
   760.8 2478.93   771.7 2479.39   788.9 2478.82   797.6 2484.04   803.7 2488.69
#Mann= 8 ,-1,0
       0      .1       0     370     .08       0     430     .07       0
     540     .08       0     550      .1       0   630.9    .045       0
   665.4      .1       0     720     .06       0
Bank Sta=630.9,665.4
XS Rating Curve= 0 ,0
Exp/Cntr=0.3,0.1

Type RM Length L Ch R = 1 ,33089   ,395.1,427.1,448.9
XS GIS Cut Line= 2
2229610.53037434408314.6518962472230198.23364994407915.608232462
#Sta/Elev= 30
       0 2469.94    35.8 2460.71   109.4 2454.85   195.2 2450.11   243.7 2448.96
   290.2 2449.41     319 2448.43   365.1 2449.58   385.2 2448.56   393.6  2449.3
     414 2448.92     440 2449.53   460.1 2450.11   471.6 2448.24   485.5 2448.43
   497.5 2449.94   524.2  2450.8   538.7 2450.01   548.3 2448.89   567.7 2448.98
     573 2449.92   582.2 2460.29   583.9 2461.68     587 2463.71   591.8 2465.14
   635.8 2466.72   657.7 2468.44   683.7 2470.96   698.2 2475.45   710.4 2475.68
#Mann= 6 ,-1,0
       0      .1       0     440     .08       0   538.7    .045       0
     573     .08       0     590      .1       0     680     .06       0
Bank Sta=538.7,573
XS Rating Curve= 0 ,0
Exp/Cntr(USF)=0,0
Exp/Cntr=0.3,0.1

Type RM Length L Ch R = 1 ,32662   ,302.6,284.7,245.2
XS GIS Cut Line= 4
2229661.98299575408328.3725952892229904.38201214408354.670601785
2230032.44186986408470.1531520492230372.02917113408259.769100082
#Sta/Elev= 30
       0 2461.39    94.7 2455.04   166.1    2449   231.5 2445.25   245.5 2445.31
   259.6 2446.19   266.92445.899   276.6 2443.36   281.2 2443.02   287.9 2443.69
   295.62445.715   313.4 2445.75   324.3 2446.62   383.6 2444.72     389 2445.62
   392.7 2447.19   399.7 2448.77   416.3 2448.72   433.3 2450.37     463    2452
   477.1 2451.95   486.5 2452.81   509.3 2453.18     543 2452.05   575.9 2452.43
     608 2454.45   681.2 2456.42     703  2458.1   735.9 2458.22   815.7 2461.38
#Mann= 5 ,-1,0
       0      .1       0   266.9    .045       0   295.6     .08       0
  466.26     .12       0  806.26     .06       0
Bank Sta=266.9,295.6
XS Rating Curve= 0 ,0
Exp/Cntr(USF)=0,0
Exp/Cntr=0.3,0.1

Type RM Length L Ch R = 1 ,32377   ,307.6,308.5,310.3
XS GIS Cut Line= 4
2229808.33711885 408718.269126382229870.08026454408667.959896562
2230039.30221938408522.7491650412230386.89326176408294.070847685
#Sta/Elev= 30
       0 2552.32    27.1 2540.52      49 2529.25    63.2 2520.91    83.9 2507.19
    92.9 2500.24   111.5 2486.83   126.9 2473.32   135.1 2465.59   155.3 2442.52
   157.6  2440.8   163.8  2440.2   177.3 2440.28   182.4 2440.93   185.2 2441.96
   188.3 2443.04   198.4 2443.86   227.8 2444.01   280.5 2445.47   315.9 2447.41
   337.2 2447.51   359.3 2448.76   375.5 2450.78   400.1 2450.12   480.6 2453.03
   528.7 2452.98     634 2457.69   662.1 2459.58   682.7 2459.68   718.7 2461.13
#Mann= 5 ,-1,0
       0      .1       0   155.3    .045       0   185.2      .1       0
  342.63     .12       0  692.63     .07       0
#XS Ineff= 2 , 0
                          272.44         2460.38
Permanent Ineff=
       F       F
Bank Sta=155.3,185.2
XS Rating Curve= 0 ,0
Exp/Cntr(USF)=0,0
Exp/Cntr=0.3,0.1

Type RM Length L Ch R = 1 ,32068   ,250.8,249.1,249.1
XS GIS Cut Line= 3
2229959.26480831408982.3925829262230211.95434899408788.016013173
2230561.83217454408383.255391454
#Sta/Elev= 30
       0 2572.07    47.2 2544.73    81.9 2523.19     107 2506.46   117.2 2498.86
   135.6 2486.71   152.7 2474.81   162.6 2467.39   172.7 2460.73   181.2  2454.3
   195.5 2441.87   198.3 2440.16   201.2 2439.35   205.4 2438.72   226.9 2437.95
   244.7 2438.78   251.3 2439.36   258.5 2441.17   268.6 2442.19   397.5 2444.26
     417 2445.59   445.7 2449.05   471.3 2450.93   502.5  2451.1   539.3 2452.03
   658.4 2456.37   692.7 2458.07   793.1 2461.16   845.6 2463.26   853.8 2465.19
#Mann= 7 ,-1,0
       0      .1       0   201.2    .045       0   244.7      .1       0
   408.8     .05       0   598.8      .1       0   708.8     .05       0
   728.8     .06       0
Bank Sta=201.2,244.7
XS Rating Curve= 0 ,0
Exp/Cntr(USF)=0,0
Exp/Cntr=0.3,0.1

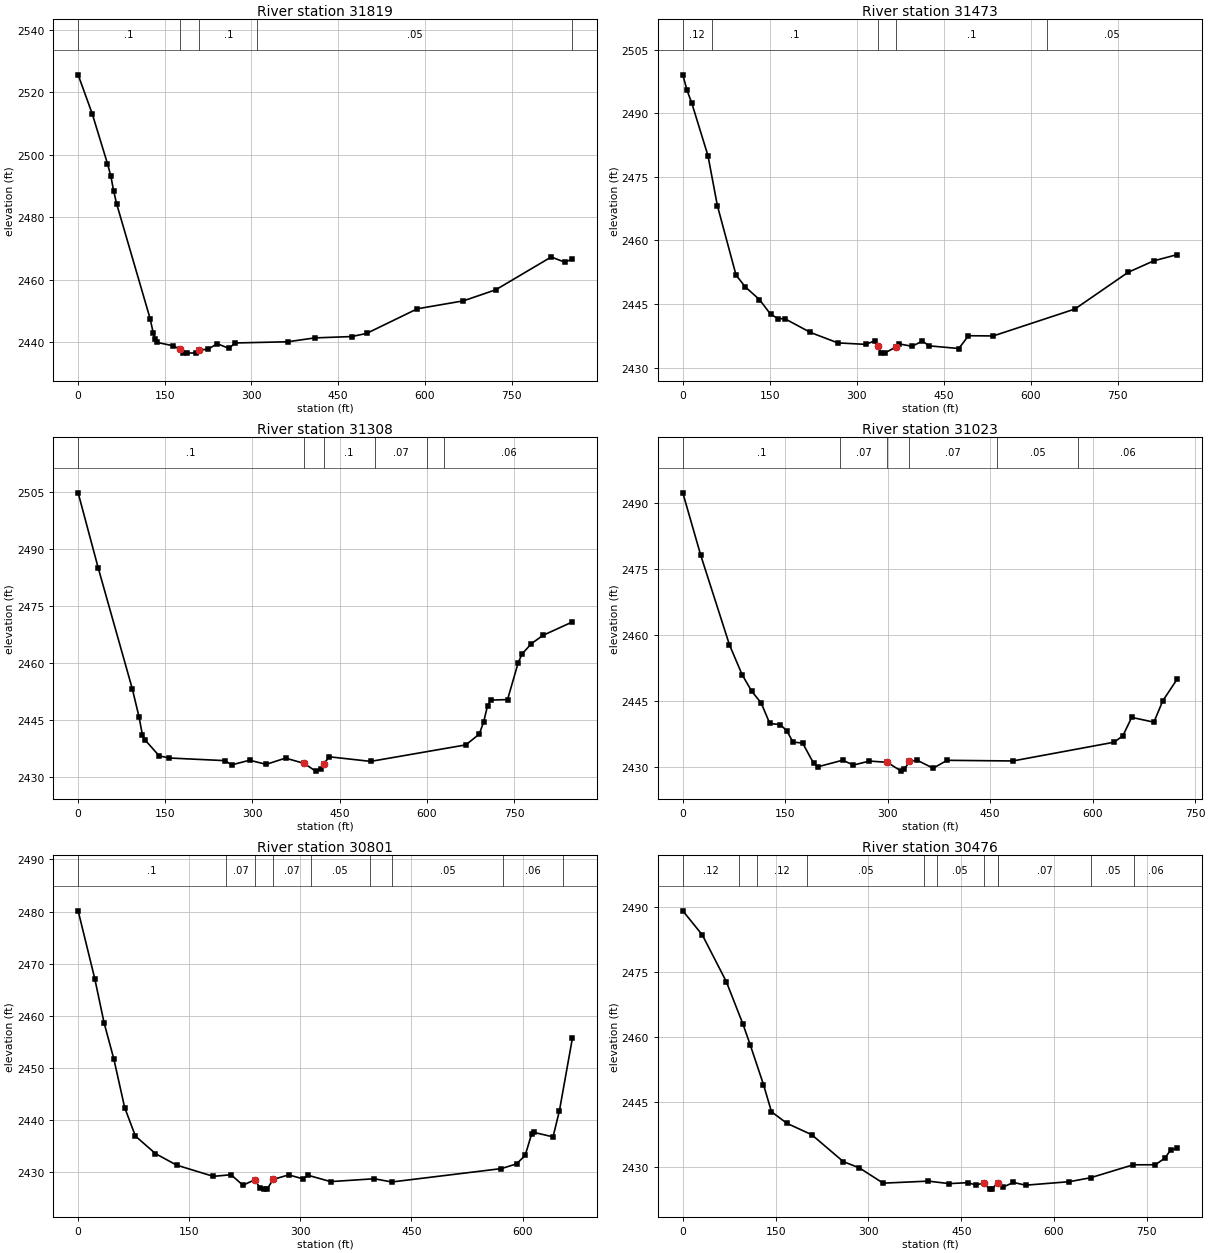
Type RM Length L Ch R = 1 ,31819   ,348.4,346,347.5
XS GIS Cut Line= 3
 2230129.6567942 409178.44086747  2230565.185274408803.966243845
2230757.21284314408598.812156865
#Sta/Elev= 30
       0 2525.51    24.4 2513.05    50.8  2497.1    56.6 2493.14    61.3 2488.52
    66.6  2484.3   124.6 2447.53   129.9 2443.02   133.2 2440.99     136 2439.98
   164.4 2438.88   175.7 2437.79   181.4 2436.73     188 2436.53   204.1  2436.6
   209.7  2437.5   224.9 2437.81   240.7 2439.53   260.8 2438.08   272.1 2439.78
   362.9 2440.16   409.5  2441.4   473.5 2441.83   499.2 2442.83     587 2450.71
   666.6 2453.24   722.8 2456.79   818.7 2467.27   841.7 2465.64   855.4 2466.57
#Mann= 5 ,-1,0
       0      .1       0   175.7    .045       0   209.7      .1       0
     310     .05       0  855.39     .06       0
Bank Sta=175.7,209.7
XS Rating Curve= 0 ,0
Exp/Cntr=0.3,0.1

Type RM Length L Ch R = 1 ,31473   ,159.3,165.4,166.7
XS GIS Cut Line= 4
2230220.98408116409316.1522835862230460.95515493409344.384174618
2230675.83121445 409154.603129352230832.67505351408870.715780644
#Sta/Elev= 30
       0 2499.12     7.2 2495.48    15.3 2492.51    43.4 2480.02    59.6 2468.24
    91.8 2451.83   107.9 2449.01   132.1 2446.06   151.5 2442.57   164.3 2441.56
   176.4  2441.5     220 2438.29   267.3 2435.82   315.3 2435.47   331.1 2436.29
   336.6 2434.97   342.5  2433.5   348.2  2433.4     368  2434.9   373.7 2435.56
   395.4 2435.02   413.4 2436.25   424.6 2435.12   476.1 2434.49   492.7 2437.51
   535.5 2437.46   676.2 2443.81     768 2452.48   812.2 2455.19   852.6 2456.66
#Mann= 5 ,-1,0
       0     .12       0      50      .1       0   336.6    .045       0
     368      .1       0  628.31     .05       0
Bank Sta=336.6,368
XS Rating Curve= 0 ,0
Exp/Cntr(USF)=0,0
Exp/Cntr=0.3,0.1

Type RM Length L Ch R = 1 ,31308   ,281.1,285.1,283.3
XS GIS Cut Line= 3
2230330.94450075409584.4837717452230919.63969482  409211.3719814
2231012.63193011409089.150219708
#Sta/Elev= 30
       0 2504.67    34.6 2484.89    93.1 2453.19   104.7 2445.81   110.5  2441.1
   115.1 2439.69   139.5  2435.5   156.9 2434.94   252.5 2434.25   264.2 2433.13
   295.1 2434.36   323.5 2433.27   356.9 2434.91   388.8 2433.53   408.7 2431.49
   417.1 2431.98   422.9 2433.44   432.1 2435.26   503.4 2434.05   667.1 2438.39
   690.3 2441.22   697.9  2444.5   704.6 2448.73   710.3 2450.17   738.9  2450.3
   757.3 2460.03   763.9 2462.29   780.1 2465.04   800.3 2467.22   850.6 2470.73
#Mann= 6 ,-1,0
       0      .1       0   388.8    .045       0   422.9      .1       0
     510     .07       0     600     .05       0     630     .06       0
Bank Sta=388.8,422.9
XS Rating Curve= 0 ,0
Exp/Cntr=0.3,0.1

Type RM Length L Ch R = 1 ,31023   ,218.8,222.3,225.5
XS GIS Cut Line= 3
 2230465.6604701409777.2731704352230953.44480959409485.543629775
2231049.11955142409363.205435305
#Sta/Elev= 30
       0 2492.34    26.2 2478.16    68.2 2457.82    86.8 2450.99   100.8 2447.25
   114.8 2444.54   127.3  2439.9   142.8 2439.63   152.1 2438.25   161.4 2435.66
   175.4 2435.44   191.5 2430.84   197.3 2430.03     234 2431.54   249.8 2430.44
   273.3 2431.35   299.4 2431.06   319.7 2429.06   324.5 2429.46   331.5 2431.27
   343.2 2431.53   366.5 2429.72   386.9 2431.52   483.1 2431.37   631.2 2435.63
   644.2 2437.08   657.2 2441.28   689.7 2440.19   702.7 2445.05   723.7 2449.96
#Mann= 6 ,-1,0
       0      .1       0     230     .07       0   299.4    .045       0
   331.5     .07       0     460     .05       0  578.37     .06       0
Bank Sta=299.4,331.5
XS Rating Curve= 0 ,0
Exp/Cntr(USF)=0,0
Exp/Cntr=0.3,0.1

Type RM Length L Ch R = 1 ,30801   ,323.5,324.2,322.9
XS GIS Cut Line= 4
2230589.74480703409948.4062674572230789.38097808 409833.15239551
2230829.51402278 409816.687556662231162.92700948409607.789913756
#Sta/Elev= 30
       0 2480.15    22.5 2467.11    35.1 2458.63    48.1 2451.79    62.8 2442.43
    77.3 2436.96   104.4 2433.59     133 2431.38   182.5 2429.23   206.5 2429.54
   222.5 2427.52   238.8  2428.6   244.9 2427.08   250.8 2426.78   255.2 2426.81
   263.3 2428.64   284.2 2429.51   303.1 2428.77   310.6 2429.43   340.8 2428.22
   399.8 2428.77   423.4 2428.15   571.5 2430.72   591.8 2431.62   603.4 2433.23
   612.1  2437.3     615 2437.67   641.1  2436.8   649.7  2441.8   667.3 2455.78
#Mann= 9 ,-1,0
       0      .1       0     200     .07       0   238.8    .045       0
   263.3     .07       0   313.9     .05       0   393.9     .07       0
   423.9     .05       0   573.9     .06       0   653.9      .1       0
Bank Sta=238.8,263.3
XS Rating Curve= 0 ,0
Exp/Cntr(USF)=0,0
Exp/Cntr=0.3,0.1

Type RM Length L Ch R = 1 ,30476   ,77.6,79.8,82.8
XS GIS Cut Line= 2
2230578.75637479410193.9032387712231322.31630005409901.870639728
#Sta/Elev= 30
       0 2489.14    31.6 2483.55    70.3 2472.78    97.3 2462.92     109 2458.15
   130.4 2448.99   143.3 2442.71   168.3 2440.04   208.4 2437.41   259.4 2431.19
   285.2 2429.76   323.8 2426.22   396.9 2426.69   430.5 2426.11   461.4 2426.34
   473.7 2425.76   486.1 2426.28   495.7 2424.84     500 2424.92   508.6 2426.31
   517.2 2425.29   534.4 2426.39     554 2425.75   624.9 2426.56     659 2427.47
   727.8 2430.46   763.8 2430.47   778.9 2431.99   788.5 2433.88   798.9 2434.26
#Mann= 11 ,-1,0
       0     .12       0      90     .06       0     120     .12       0
     200     .05       0     390     .07       0     410     .05       0
   486.1    .045       0   508.6     .05       0     510     .07       0
     660     .05       0     730     .06       0
Bank Sta=486.1,508.6
XS Rating Curve= 0 ,0
Exp/Cntr(USF)=0,0
Exp/Cntr=0.5,0.3

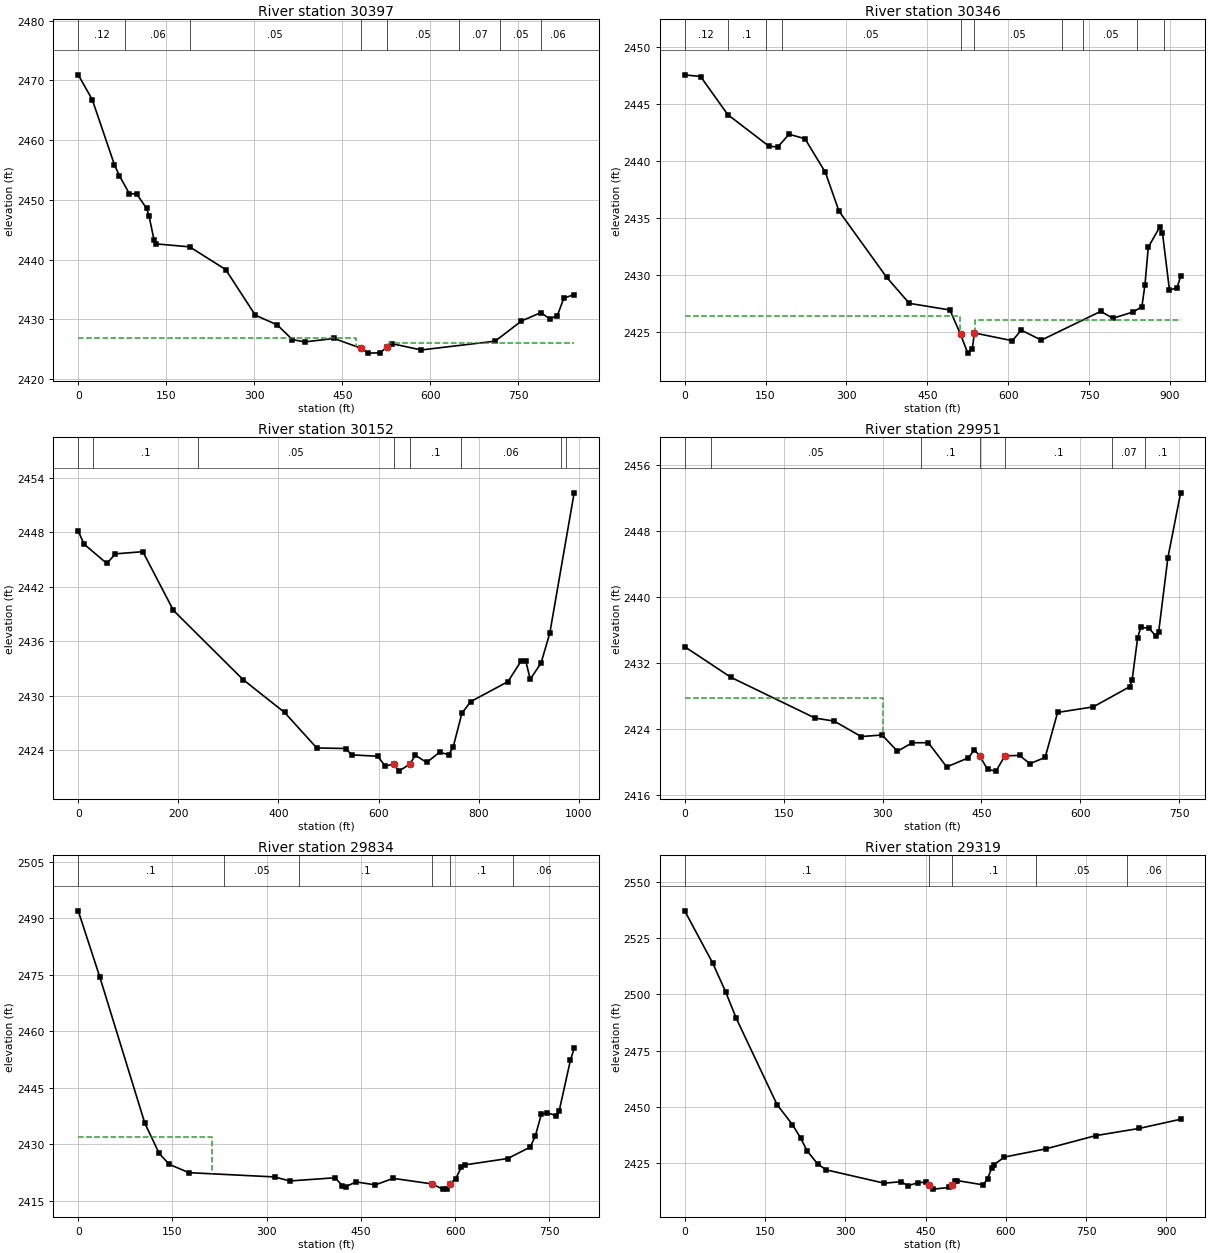
Type RM Length L Ch R = 1 ,30397   ,53.9,50.8,50.1
XS GIS Cut Line= 4
2230585.49558861410238.831330931 2230974.1235858410110.786268274
  2231196.517642410054.6261530732231344.78034613 409910.85625816
#Sta/Elev= 30
       0 2470.92    23.9 2466.78    61.8 2455.85    70.2 2454.03    87.1 2451.06
    99.7 2450.97   116.5 2448.58   120.7 2447.31   129.2 2443.29   133.3 2442.63
     190 2442.14   251.3 2438.34   301.8 2430.71   339.2 2429.08     365 2426.62
   386.1 2426.24     436 2426.81   481.1 2425.21   493.8 2424.36   514.4 2424.41
   525.7 2425.35   535.1 2425.93   584.6 2424.89   710.5 2426.36   755.3 2429.74
   788.5 2431.14   803.4 2430.09   816.4 2430.62   827.5 2433.55   845.1 2434.16
#Mann= 8 ,-1,0
       0     .12       0      80     .06       0     190     .05       0
   481.1    .045       0   525.7     .05       0  648.55     .07       0
  718.55     .05       0  788.55     .06       0
#XS Ineff= 2 , 0
          474.01  2426.9  529.93            2426
Permanent Ineff=
       F       F
Bank Sta=481.1,525.7
XS Rating Curve= 0 ,0
Exp/Cntr(USF)=0,0
Exp/Cntr=0.5,0.3

Type RM Length L Ch R = 1 ,30346   ,199.4,193.5,199.2
XS GIS Cut Line= 4
2230588.08574656410293.6872433272231038.50567098410146.751381568
2231227.96730651410097.3078406262231413.04935853409928.847536386
#Sta/Elev= 30
       0 2447.56    29.5 2447.41      80 2444.06   156.4 2441.29   172.6 2441.22
   193.6 2442.34   223.1 2441.95     261 2438.99   286.2 2435.59   374.6 2429.78
   416.6 2427.49     492 2426.91   511.7 2424.77   525.1 2423.12   533.4 2423.51
   537.5 2424.89   607.8 2424.21   624.3 2425.14   661.5 2424.26   771.8 2426.79
   794.3 2426.18   832.1 2426.74   848.1  2427.2   853.8 2429.14   859.9 2432.42
   880.8 2434.16   886.2 2433.68   899.2 2428.66   913.3 2428.86   919.9 2429.86
#Mann= 10 ,-1,0
       0     .12       0      80      .1       0     150     .06       0
     180     .05       0   511.7    .045       0   537.5     .05       0
  699.59      .1       0  739.59     .05       0  839.59     .06       0
  889.59     .07       0
#XS Ineff= 2 , 0
          510.79  2426.4  538.25            2426
Permanent Ineff=
       F       F
Bank Sta=511.7,537.5
XS Rating Curve= 0 ,0
Exp/Cntr=0.5,0.3

Type RM Length L Ch R = 1 ,30152   ,200,201.2,194.6
XS GIS Cut Line= 3
2230632.67008538410380.3548212372231090.93662542410254.556163188
 2231560.4351885410041.147725425
#Sta/Elev= 30
       0 2448.13    11.9 2446.69    57.3 2444.57    74.2 2445.63   129.1 2445.87
   190.3  2439.4   329.3 2431.79   412.3 2428.17   476.6 2424.26   534.6  2424.2
   546.2  2423.5     598 2423.35   613.9 2422.26   630.4  2422.5   640.3 2421.71
   662.2 2422.46   673.5 2423.46   696.3 2422.66   721.9 2423.79   740.2 2423.52
   749.1 2424.34   766.6 2428.08   784.1 2429.36   858.8 2431.57     885 2433.84
   894.1 2433.87   903.1 2431.82   924.8 2433.62   942.2 2436.89   990.9 2452.35
#Mann= 8 ,-1,0
       0     .12       0      30      .1       0     240     .05       0
   630.4    .045       0   662.2      .1       0  765.22     .06       0
  965.22     .07       0  975.22      .1       0
Bank Sta=630.4,662.2
XS Rating Curve= 0 ,0
Exp/Cntr(USF)=0,0
Exp/Cntr=0.3,0.1

Type RM Length L Ch R = 1 ,29951   ,116.4,117.5,111.2
XS GIS Cut Line= 3
2230915.93482126410370.0028205492231185.70622445410435.877232956
2231591.93176763410191.200844016
#Sta/Elev= 30
       0 2433.99    70.2 2430.28   197.9 2425.35   226.7 2424.99   267.6 2423.12
   299.3 2423.31   322.6 2421.34   344.9 2422.37   369.3 2422.38   397.3 2419.45
   430.2 2420.55   439.3 2421.55   447.6 2420.72   459.2 2419.15     472 2418.94
   485.5 2420.79   507.8 2420.84   523.3 2419.84   546.5 2420.59   565.4 2426.04
   619.5 2426.71   674.9 2429.16   678.3 2429.92   686.8 2435.09   691.5 2436.34
     704 2436.22   714.8 2435.23   718.6 2435.77   732.6 2444.75   751.9  2452.6
#Mann= 7 ,-1,0
       0      .1       0      40     .05       0   357.7      .1       0
   447.6    .045       0   485.5      .1       0   647.7     .07       0
   697.7      .1       0
#XS Ineff= 2 , 0
          300.52 2427.79
Permanent Ineff=
       F       F
Bank Sta=447.6,485.5
XS Rating Curve= 0 ,0
Exp/Cntr(USF)=0,0
Exp/Cntr=0.3,0.1

Type RM Length L Ch R = 1 ,29834   ,497.3,515,510.4
XS GIS Cut Line= 3
2230947.80264052 410668.990807442231062.06004978410627.109405225
2231628.50771745410273.243718955
#Sta/Elev= 30
       0 2492.03    34.5 2474.36   106.1 2435.54   128.9 2427.53   144.9 2424.64
   176.1 2422.42   312.8 2421.28   336.7 2420.21   409.1 2421.06   420.7  2418.9
     426 2418.71   442.4 2419.96     473 2419.17   501.5  2420.9   562.8 2419.44
   580.4 2418.04   586.4 2418.18     592 2419.52     601 2420.82     610 2423.83
   615.2 2424.47     684 2426.18   719.7 2429.22   727.9 2432.24   737.3 2437.92
   746.7 2438.35   760.9 2437.58   765.6 2438.72   783.6 2452.26   789.6 2455.45
#Mann= 6 ,-1,0
       0      .1       0  231.69     .05       0  351.69      .1       0
   562.8    .045       0     592      .1       0  691.69     .06       0
#XS Ineff= 2 , 0
          212.98 2431.95
Permanent Ineff=
       F       F
Bank Sta=562.8,592
XS Rating Curve= 0 ,0
Exp/Cntr=0.3,0.1

Type RM Length L Ch R = 1 ,29319   ,317.6,311.9,307.7
XS GIS Cut Line= 3
     2230919.912      410846.929     2231385.939      410868.659
     2231840.377      410797.216
#Sta/Elev= 30
       0 2537.04    52.3 2513.89    76.3 2501.22    96.4 2489.33   172.5 2451.09
   201.4 2442.16   216.7 2436.23   228.5 2430.63   248.5 2424.69   264.6 2422.11
   372.7  2416.2   404.7 2416.86   416.7 2415.01   436.7 2416.48   451.5 2416.58
   456.8 2415.61   464.8 2413.56   493.1 2414.29   498.7 2415.42   505.2 2417.22
   509.3 2417.34   557.9 2415.45     566 2418.25   574.1 2423.14   578.1 2424.45
   597.5  2427.8   675.3 2431.46   767.7 2437.29   849.4  2440.5   926.6 2444.57
#Mann= 5 ,-1,0
       0      .1       0   456.8    .045       0   498.7      .1       0
  656.53     .05       0  826.53     .06       0
Bank Sta=456.8,498.7
XS Rating Curve= 0 ,0
Exp/Cntr=0.3,0.1

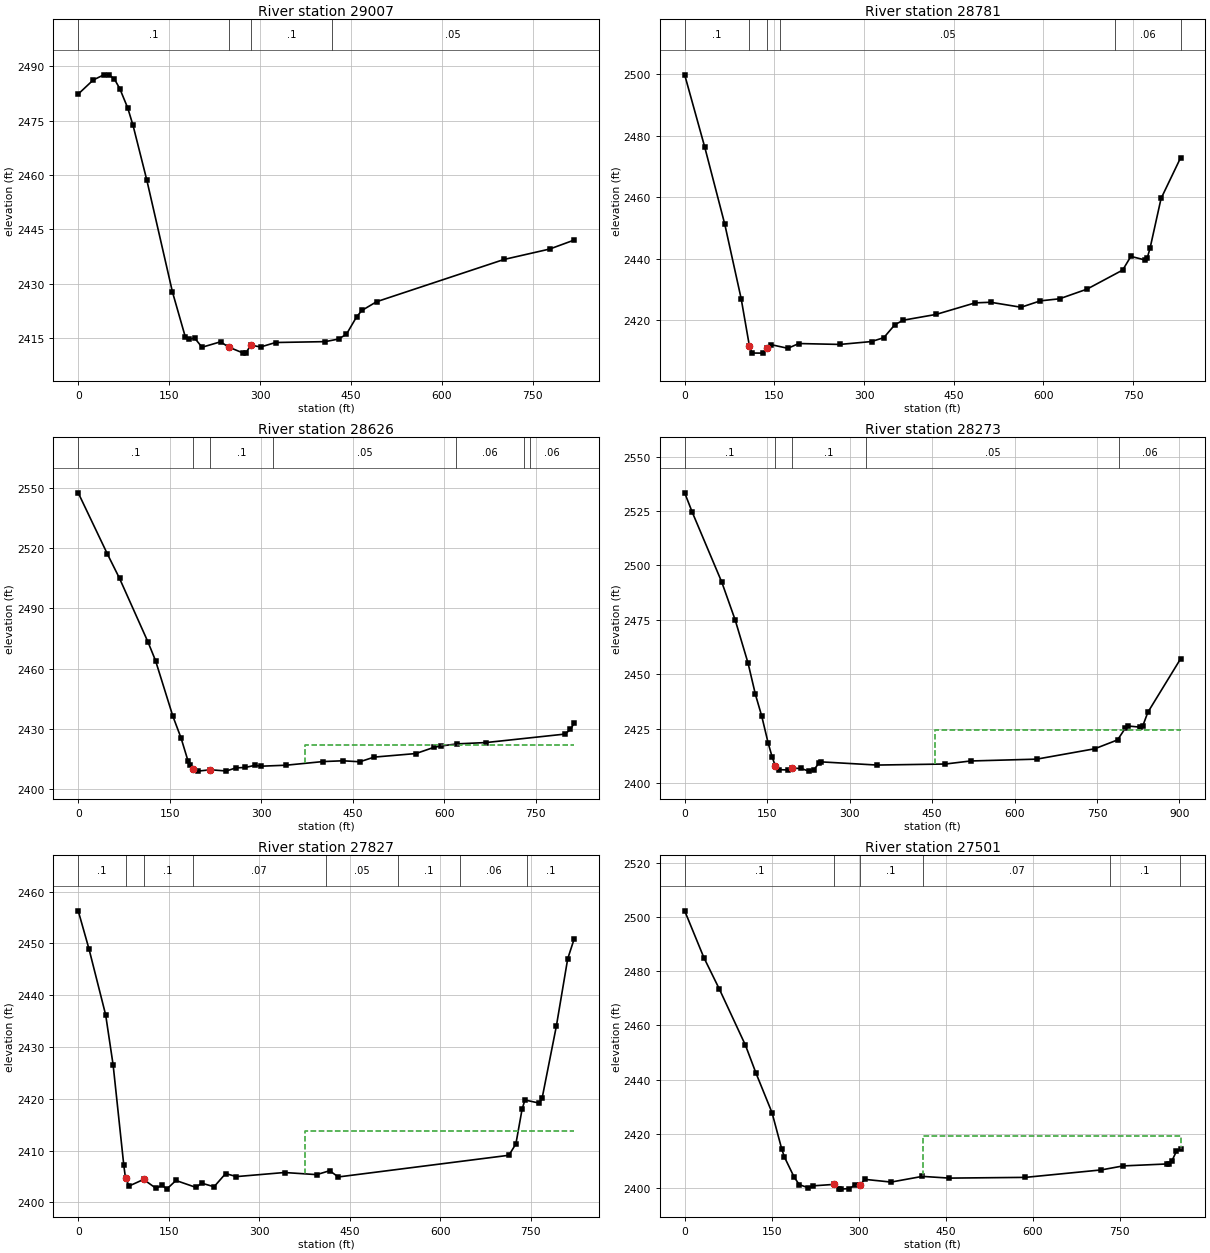
Type RM Length L Ch R = 1 ,29007   ,227.8,226.1,218.4
XS GIS Cut Line= 5
2231153.51654253411243.7838880022231381.15615994411142.620094433
  2231536.929508411110.0666173092231596.94384561411084.870156131
2231861.17363757410863.150519972
#Sta/Elev= 30
       0 2482.35    24.8 2486.24    42.3 2487.66    51.1 2487.65    59.8 2486.46
    68.6 2483.85    81.7 2478.52    90.5 2473.68   113.1 2458.68   155.5 2427.75
   176.7 2415.35   182.4 2414.64   191.9 2415.08   204.3  2412.5   234.9 2414.01
     248 2412.56   272.6 2410.88   276.7    2411   284.9 2413.05   301.2 2412.59
   325.7 2413.81   407.5 2414.05   429.7 2414.77   442.6  2416.1   459.5 2420.93
   468.2 2422.67   492.4 2425.07   702.5 2436.72   777.8 2439.59   818.3 2442.07
#Mann= 4 ,-1,0
       0      .1       0     248    .045       0   284.9      .1       0
  418.24     .05       0
Bank Sta=248,284.9
XS Rating Curve= 0 ,0
Exp/Cntr(USF)=0,0
Exp/Cntr=0.3,0.1

Type RM Length L Ch R = 1 ,28781   ,155.3,154.3,154.4
XS GIS Cut Line= 2
2231313.81321267 411408.427630472232036.66801005 411001.79552489
#Sta/Elev= 30
       0 2499.85    33.5 2476.36      67 2451.27    94.5 2426.98   108.3 2411.55
   112.8 2409.32   131.2 2409.29   137.2 2411.12     145 2412.03   172.5 2410.86
   190.9 2412.41   259.5 2412.12   312.5 2413.06     333 2414.32   351.5 2418.54
   365.6 2420.01   420.4 2421.88   485.8 2425.65   511.7 2425.84   562.6 2424.22
   594.8  2426.3   626.9 2426.97   672.8 2430.11   732.5 2436.32   746.2 2440.77
   769.1 2439.64   773.7 2440.36   778.3 2443.45   796.7 2459.61   829.4 2472.87
#Mann= 6 ,-1,0
       0      .1       0   108.3    .045       0   137.2      .1       0
     160     .05       0     720     .06       0  829.38      .1       0
Bank Sta=108.3,137.2
XS Rating Curve= 0 ,0
Exp/Cntr=0.3,0.1

Type RM Length L Ch R = 1 ,28626   ,351.3,353.5,351.9
XS GIS Cut Line= 3
2231307.24284998411592.9772629752231762.90726514 411322.54228487
2232016.67159391411197.512414856
#Sta/Elev= 30
       0 2547.68    47.6 2517.29    67.7 2504.99   114.4 2473.19   126.7 2463.95
   155.2 2436.13   168.5 2425.35   179.9 2413.93   182.5  2411.8   187.7 2409.87
   196.4 2408.78   216.5 2409.46   242.8 2408.84   258.2 2410.39   273.9 2410.61
   289.5 2411.68   298.8 2411.23   340.6 2411.73   401.1 2413.55   433.7 2413.94
   461.6 2413.45   484.8 2415.77   553.6 2417.56   582.6 2420.61   594.6 2421.34
   621.5 2422.39   668.7 2423.05   797.7 2427.27   806.7 2429.57   812.8 2432.74
#Mann= 7 ,-1,0
       0      .1       0   187.7    .045       0   216.5      .1       0
     320     .05       0  619.87     .06       0  729.87     .05       0
  739.87     .06       0
#XS Ineff= 2 , 0
                          371.24         2422.01
Permanent Ineff=
       F       F
Bank Sta=187.7,216.5
XS Rating Curve= 0 ,0
Exp/Cntr(USF)=0,0
Exp/Cntr=0.3,0.1

Type RM Length L Ch R = 1 ,28273   ,443.2,445.9,443.4
XS GIS Cut Line= 2
2231456.38893162411902.6325077952232239.83645802411455.325201107
#Sta/Elev= 30
       0 2533.36    13.6 2524.55    67.5 2492.29    91.9 2474.88   115.3 2455.05
   128.7 2440.66   140.1 2430.77   151.8 2418.38   159.2 2411.85   165.1 2407.65
   172.3 2406.08   188.6 2405.97   194.4 2406.77     212 2406.66   225.4 2405.43
   234.7 2405.92   243.9 2409.01   248.5 2409.68   349.8 2408.22   474.2  2408.7
   519.9 2410.09   640.3 2410.94   745.9 2415.71   787.4 2419.78   801.2 2425.06
   805.8 2426.19   828.8 2425.64   833.4 2426.28   842.4 2432.44   902.1 2457.08
#Mann= 5 ,-1,0
       0      .1       0   165.1    .045       0   194.4      .1       0
     330     .05       0     790     .06       0
#XS Ineff= 2 , 0
                          454.69         2424.49
Permanent Ineff=
       F       F
Bank Sta=165.1,194.4
XS Rating Curve= 0 ,0
Exp/Cntr=0.3,0.1

Type RM Length L Ch R = 1 ,27827   ,315.7,325.5,311.4
XS GIS Cut Line= 3
 2231676.0738018412249.8083936682232165.45116741412013.533617198
2232401.17723982411864.994946607
#Sta/Elev= 30
       0  2456.3    17.9 2448.92    45.5  2436.2    57.9 2426.51    75.6 2407.11
    78.4 2404.66    84.4 2403.15   108.4 2404.41   128.9  2402.7   139.4 2403.29
   146.7 2402.54     162 2404.21   195.3 2402.87   204.4  2403.7   225.2    2403
   244.4 2405.55   262.2 2404.96     342 2405.75   395.4 2405.34   416.9  2406.1
     431 2404.89   713.9 2409.08   725.5 2411.27   735.8 2417.98   740.5 2419.76
   764.1 2419.16   768.9 2420.05   792.5 2433.96   811.4 2447.03   822.1 2450.86
#Mann= 8 ,-1,0
       0      .1       0    78.4    .045       0   108.4      .1       0
     190     .07       0     410     .05       0     530      .1       0
  633.43     .06       0  743.43      .1       0
#XS Ineff= 2 , 0
                          376.34          2413.7
Permanent Ineff=
       F       F
Bank Sta=78.4,108.4
XS Rating Curve= 0 ,0
Exp/Cntr=0.3,0.1

Type RM Length L Ch R = 1 ,27501   ,153.3,151.4,144.3
XS GIS Cut Line= 3
2231690.64124671412497.0364911512232077.56495967412301.516529812
2232436.70425708412081.299310199
#Sta/Elev= 30
       0 2502.23    33.1 2484.99      60 2473.29   104.8 2452.69   123.1 2442.33
   150.5 2427.89   167.5 2414.31     172  2411.5   188.6 2404.14   197.5 2401.36
   212.4 2400.23   221.4 2400.91   257.1 2401.44     266 2399.72     269  2399.7
   283.9 2399.91     293 2401.13   301.7 2401.25     311 2403.29   355.8  2402.3
   409.6 2404.39     456 2403.76   587.2 2404.03   718.1 2406.78   755.6 2408.25
   832.1 2408.98   835.4 2409.06     840 2410.18   847.4 2413.57   854.8 2414.52
#Mann= 6 ,-1,0
       0      .1       0   257.1    .045       0   301.7      .1       0
     410     .07       0  733.52      .1       0  853.52     .06       0
#XS Ineff= 2 , 0
                          410.85         2419.29
Permanent Ineff=
       F       F
Bank Sta=257.1,301.7
XS Rating Curve= 0 ,0
Exp/Cntr(USF)=0,0
Exp/Cntr=0.3,0.1