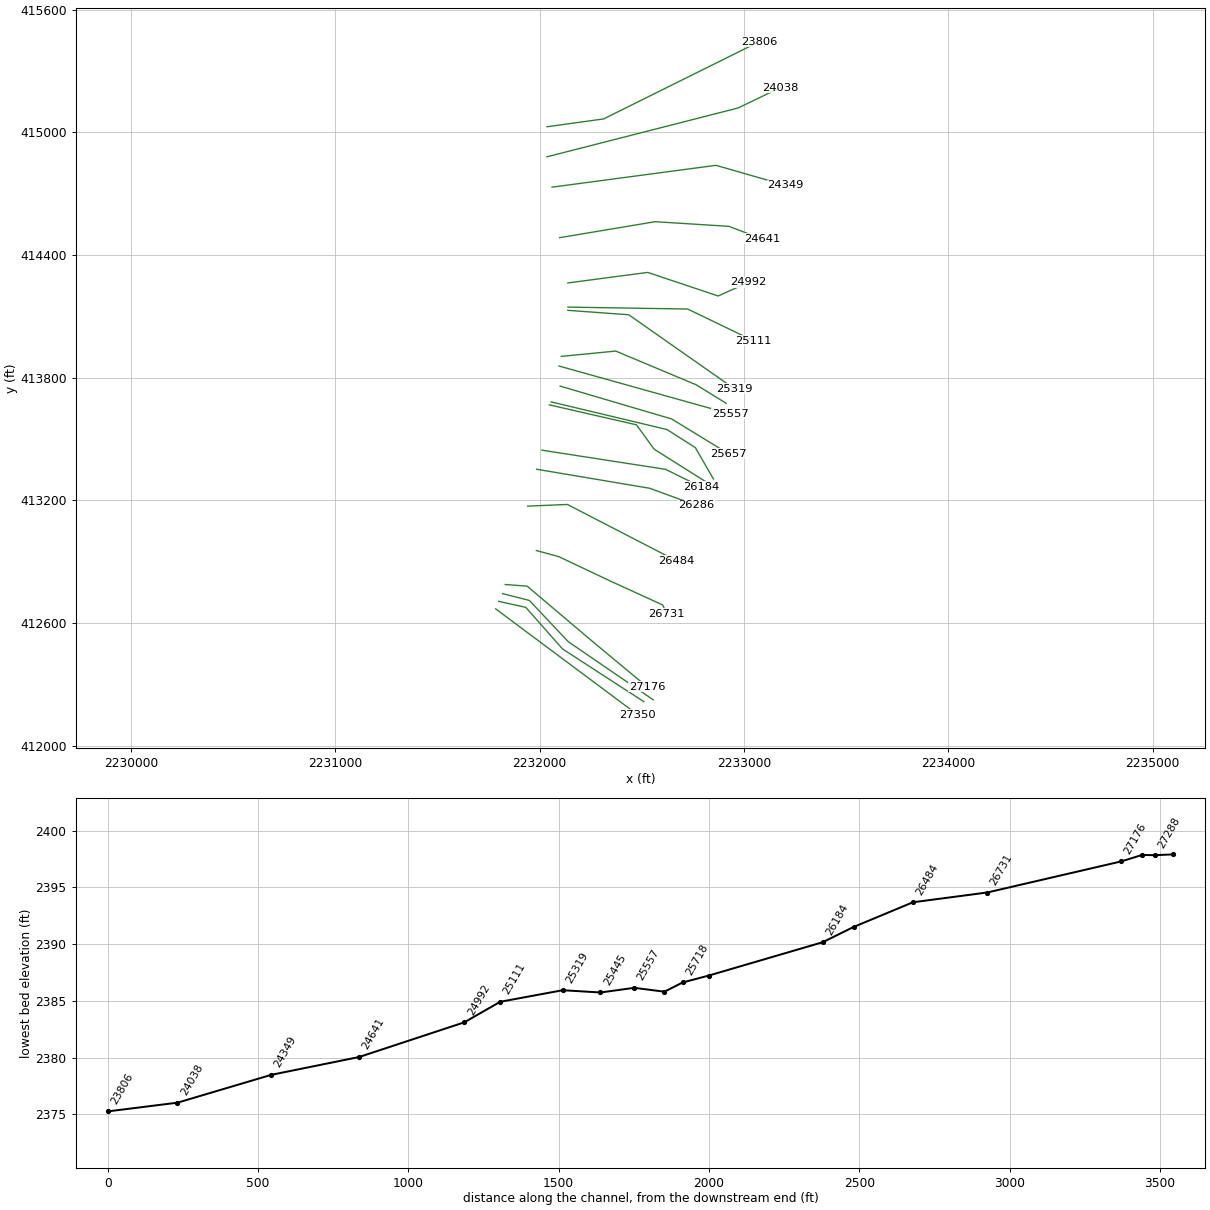
HEC-RAS study BEAVERCK.prj: BEAVERCK

--- BEAVERCK.g01 (geometry) --- (continued)

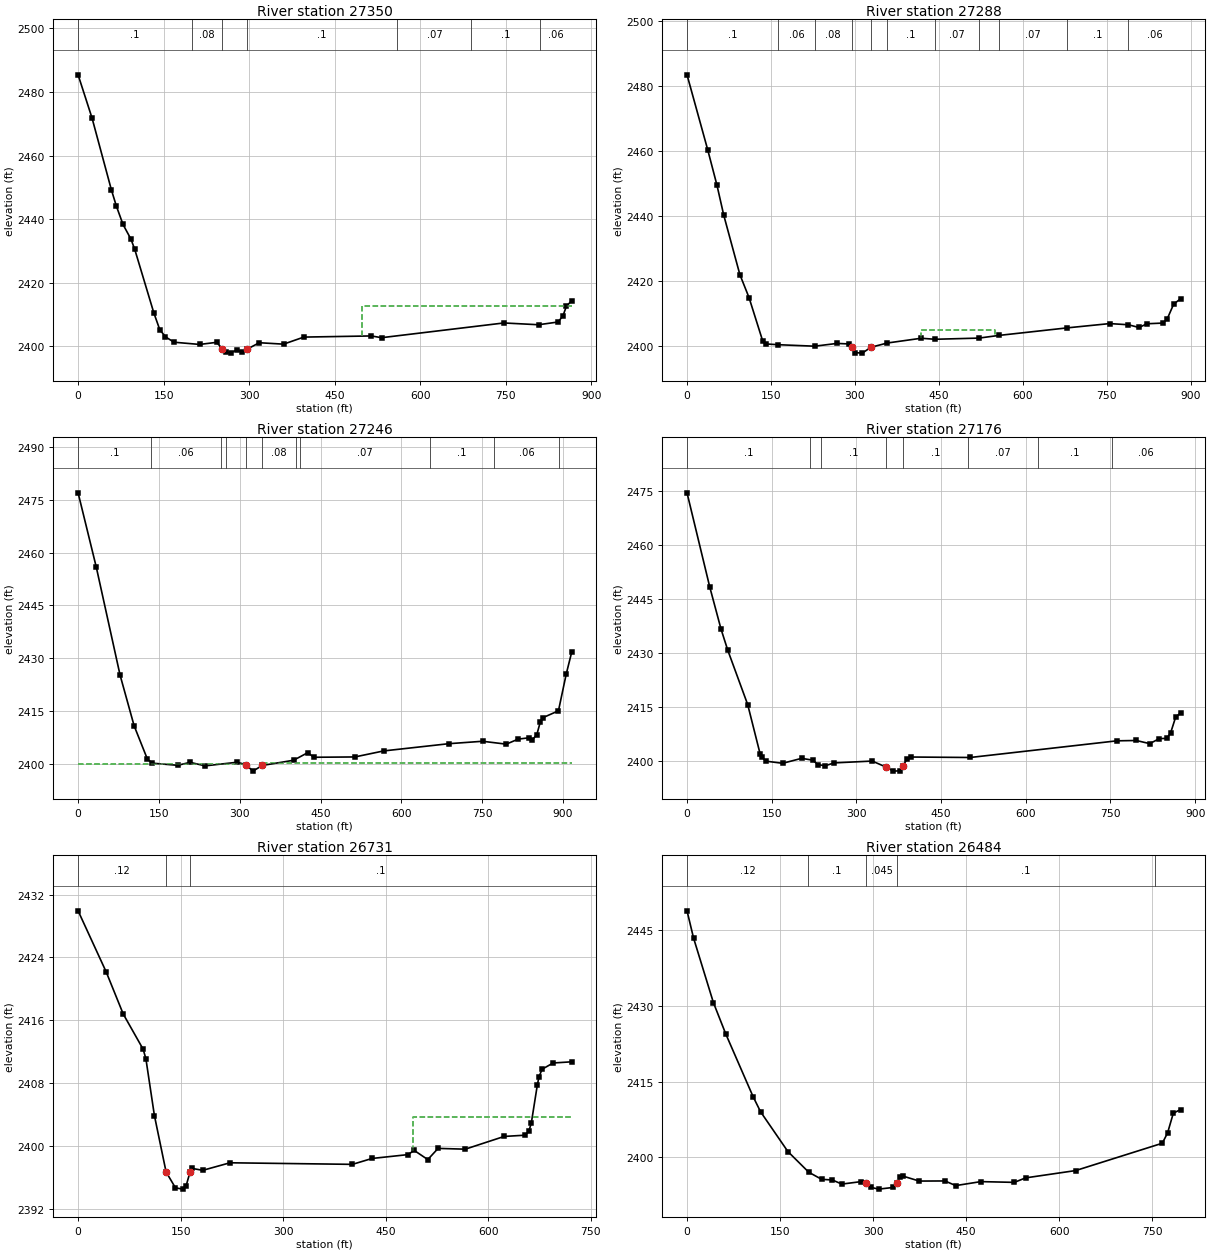
Type RM Length L Ch R = 1 ,27350   ,64.5,62.2,53.9
XS GIS Cut Line= 2
2231785.32073204412668.5463738582232479.51164787412151.219385631
#Sta/Elev= 30
       0 2485.35    24.5 2471.75    58.4 2449.21    67.3 2444.02    78.8 2438.33
    92.7 2433.72    99.4 2430.49   132.8 2410.58   143.2 2405.31   153.2 2403.03
   168.2 2401.33   213.2 2400.63     243 2401.29   253.3 2399.23   258.8 2398.12
   267.4  2397.9   277.9 2398.91   287.9 2398.21     296 2399.09   317.8 2401.17
   360.4 2400.72     396 2402.94   514.4  2403.3   532.3 2402.75   746.9 2407.38
   807.7 2406.82     842 2407.68   850.5 2409.61   856.6 2412.61   865.8 2414.38
#Mann= 7 ,-1,0
       0      .1       0     200     .08       0   253.3    .045       0
     296      .1       0     560     .07       0     690      .1       0
     810     .06       0
#XS Ineff= 2 , 0
                          498.44         2412.69
Permanent Ineff=
       F       F
Bank Sta=253.3,296
XS Rating Curve= 0 ,0
Exp/Cntr(USF)=0,0
Exp/Cntr=0.5,0.3

Type RM Length L Ch R = 1 ,27288   ,41.2,41.8,42.3
XS GIS Cut Line= 4
2231800.05939267412705.3930254412231932.70733837412675.915704175
 2232112.5189981412472.522187436 2232510.4628352412214.595626354
#Sta/Elev= 30
       0 2483.38      37 2460.32    53.4 2449.51    65.7 2440.17    94.4 2421.98
   110.8 2414.89   135.3  2401.5   140.3 2400.66   162.9 2400.42   228.1 2399.96
   267.7 2400.81     289 2400.66   294.4 2399.74   299.7 2397.99   313.1 2397.83
   328.3 2399.62   357.7 2400.94   418.2  2402.4   442.9 2402.09   521.4 2402.45
   557.4 2403.28   678.3 2405.58   754.9 2406.91   788.4 2406.55   807.4 2405.71
   821.7 2406.86   850.3 2407.07   857.8 2408.37   869.3  2412.9   881.6 2414.54
#Mann= 11 ,-1,0
       0      .1       0   162.9     .06       0   228.1     .08       0
   294.4    .045       0   328.3     .08       0   357.7      .1       0
   442.9     .07       0   521.4      .1       0   557.4     .07       0
   678.3      .1       0   788.4     .06       0
#XS Ineff= 3 ,-1
     100     278    2400     343   418.2    2400   418.2     550    2405
Permanent Ineff=
       F       F       F
Bank Sta=294.4,328.3
XS Rating Curve= 0 ,0
Exp/Cntr(USF)=0,0
Exp/Cntr=0.5,0.3

Type RM Length L Ch R = 1 ,27246   ,67.4,69.7,72
XS GIS Cut Line= 4
2231819.40023982412743.068053393 2231950.1185629412709.853525789
 2232140.5224533412507.8949729562232556.38606154412223.568267873
#Sta/Elev= 30
       0 2476.98    33.8 2455.83    77.9 2425.17     104 2410.74   128.7 2401.24
   137.9 2400.11   184.9  2399.5   207.8 2400.35   235.8 2399.35   295.2 2400.37
   311.7 2399.69   324.5 2397.85     342 2399.47     400 2400.94   426.6 2403.12
   437.2 2401.79   513.8 2401.88   567.1 2403.59   688.2 2405.65   750.9 2406.34
   794.8 2405.52     817 2406.95   837.2 2407.33   843.3 2406.74   851.6 2408.26
   857.8 2411.71   862.6 2413.03   891.7    2415   906.2 2425.49   916.2 2431.62
#Mann= 11 ,-1,0
       0      .1       0  134.87     .06       0  264.87      .1       0
  274.87     .08       0   311.7    .045       0     342     .08       0
  404.87      .1       0  412.43     .07       0  652.43      .1       0
  772.43     .06       0  892.43      .1       0
#XS Ineff= 2 , 0
           309.2    2400  344.96          2400.3
Permanent Ineff=
       F       F
Bank Sta=311.7,342
XS Rating Curve= 0 ,0
Exp/Cntr=0.5,0.3

Type RM Length L Ch R = 1 ,27176   ,434,445.8,439.8
XS GIS Cut Line= 4
2231832.17905759412787.7370235062231939.34627039412779.677301747
2232263.82344916412505.2689105762232526.86786337412287.007564939
#Sta/Elev= 30
       0 2474.41    40.1 2448.42    60.2 2436.66    72.2 2430.78   107.5 2415.71
   129.5 2402.04   132.5 2401.16     140 2400.04   169.4 2399.45   202.9 2400.82
   222.8 2400.32   231.9 2399.09   244.8 2398.76   260.3 2399.56   328.1 2400.07
   351.7 2398.46   365.2 2397.28   376.6 2397.36   382.22398.688   390.1 2400.72
   396.3 2401.19   501.6 2401.06   761.6 2405.68   795.7 2405.77   819.6  2404.9
   836.7  2406.3   849.9 2406.35   856.6  2407.9   865.5 2412.25   874.2  2413.4
#Mann= 8 ,-1,0
       0      .1       0  217.47     .06       0  237.47      .1       0
   351.7    .045       0   382.2      .1       0  497.47     .07       0
  622.42      .1       0  752.42     .06       0
Bank Sta=351.7,382.2
XS Rating Curve= 0 ,0
Exp/Cntr(USF)=0,0
Exp/Cntr=0.3,0.1

Type RM Length L Ch R = 1 ,26731   ,247.1,246.8,245.4
XS GIS Cut Line= 5
2231984.48438328412953.8106549062232094.02979852412924.093248813
2232344.08953855412805.7522195822232602.29978559412687.771122257
2232622.57263078412644.580708917
#Sta/Elev= 30
       0 2429.93    41.1 2422.16      66 2416.81      95 2412.35    99.1 2411.15
   111.6  2403.9   128.7 2396.72   142.4  2394.7   153.3 2394.54   157.7 2394.88
   163.72396.706   167.1 2397.17   182.3 2396.93   222.1 2397.89   401.2 2397.69
   429.9 2398.44   482.6 2398.93   491.4 2399.47   511.4  2398.3   526.5 2399.72
   566.2 2399.62   623.1 2401.24   654.1  2401.4   659.3 2401.92   662.9 2402.99
   671.7 2407.83     674  2408.8   678.5 2409.78   694.6 2410.58   721.8 2410.73
#Mann= 3 ,-1,0
       0     .12       0   128.7    .045       0   163.7      .1       0
#XS Ineff= 2 , 0
                          489.11         2403.72
Permanent Ineff=
       F       F
Bank Sta=128.7,163.7
XS Rating Curve= 0 ,0
Exp/Cntr=0.3,0.1

Type RM Length L Ch R = 1 ,26484   ,185.2,197.6,204.2
XS GIS Cut Line= 3
2231941.73003917413171.0658315582232136.22094808413179.298250982
2232670.29915826412903.512200251
#Sta/Elev= 30
       0 2448.88    10.5  2443.5    42.5 2430.69    62.5 2424.45   106.5 2412.03
   118.6 2409.02   162.6 2401.14   196.2 2397.04   217.1 2395.62   234.2  2395.5
   249.6 2394.68   280.1 2395.16   289.2 2394.81   297.1 2394.01     309 2393.68
   332.8 2394.02   338.6 2394.94   343.2 2396.16   347.5 2396.29   374.3 2395.28
   415.9  2395.3   433.2 2394.38   473.7 2395.17   527.7 2395.02   545.8 2395.91
   626.5 2397.36   766.2 2402.78   774.7 2404.81     784 2408.74   795.7 2409.47
#Mann= 5 ,-1,0
       0     .12       0  194.67      .1       0   289.2    .045       0
   338.6      .1       0  754.67     .06       0
Bank Sta=289.2,338.6
XS Rating Curve= 0 ,0
Exp/Cntr(USF)=0,0
Exp/Cntr=0.3,0.1

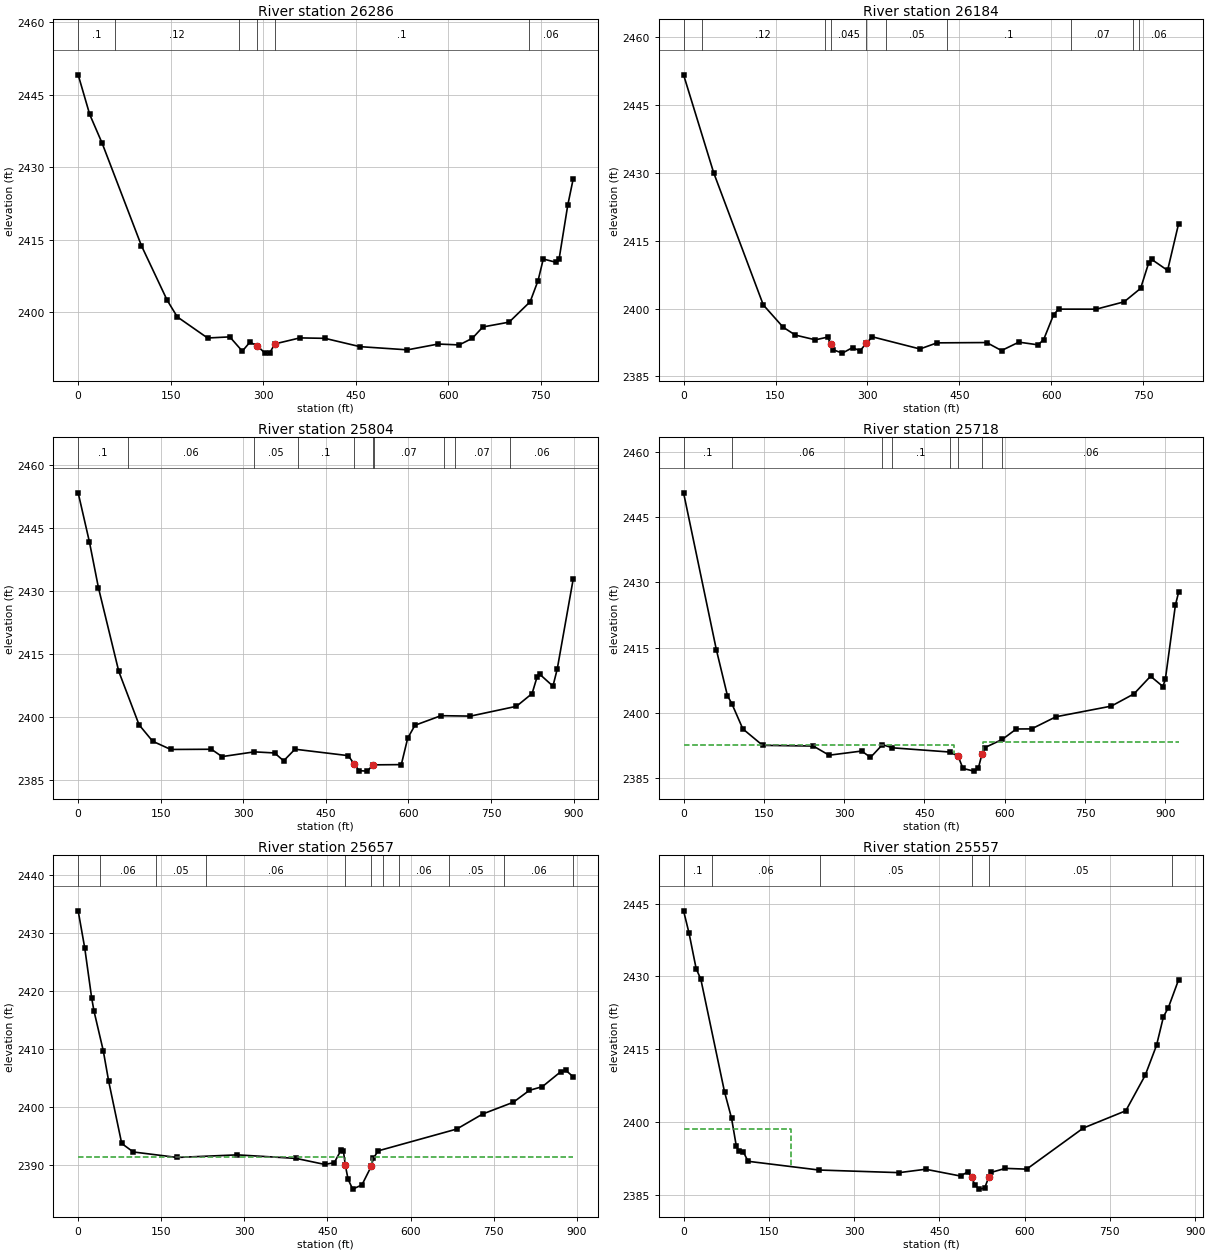
Type RM Length L Ch R = 1 ,26286   ,109,102.4,101.7
XS GIS Cut Line= 3
2231985.72993665 413351.492196382232539.05669502413258.501937557
2232765.66424977413175.507017193
#Sta/Elev= 30
       0 2449.07    18.7 2440.88      39 2434.88   102.5 2413.74   144.4 2402.41
   160.7    2399   209.8 2394.63   245.8 2394.86   266.1 2391.91   278.3 2393.75
   290.5 2393.03   302.6  2391.5   310.7  2391.6   318.9 2393.41   359.4 2394.65
     400 2394.56   456.8 2392.84   533.8 2392.18   583.6 2393.38   617.7  2393.2
     639 2394.57     656 2396.91   698.6 2397.91   732.7 2402.13   745.5  2406.5
     754 2410.97   775.3 2410.27   779.5 2410.87   793.7 2422.13   802.4 2427.49
#Mann= 6 ,-1,0
       0      .1       0      60     .12       0     260      .1       0
   290.5    .045       0   318.9      .1       0  731.09     .06       0
Bank Sta=290.5,318.9
XS Rating Curve= 0 ,0
Exp/Cntr=0.3,0.1

Type RM Length L Ch R = 1 ,26184   ,406.8,379.2,364.1
XS GIS Cut Line= 3
2232011.70560428413444.793777433  2232616.788432413351.150006475
2232791.72734478413264.709602515
#Sta/Elev= 30
       0 2451.71    49.1 2430.05     130 2400.83   162.4 2395.89   182.3 2394.15
     215  2393.1   234.9  2393.7   240.5 2392.09   243.3 2390.94     259 2390.16
   275.7 2391.39   287.9 2390.65   298.32392.423   308.1 2393.76   385.6 2391.08
   413.3 2392.43   494.4  2392.5   518.6 2390.73   546.9 2392.59   578.4 2391.99
   587.4 2393.17   603.6 2398.66   611.7 2399.89     673 2399.88   718.7 2401.51
   745.5 2404.48   758.8 2410.17   763.3 2410.91   789.5 2408.46   807.4 2418.74
#Mann= 10 ,-1,0
       0      .1       0      30     .12       0     230      .1       0
   240.5    .045       0   298.3      .1       0     330     .05       0
     430      .1       0  632.29     .07       0  732.29      .1       0
  742.29     .06       0
Bank Sta=240.5,298.3
XS Rating Curve= 0 ,0
Exp/Cntr(USF)=0,0
Exp/Cntr=0.3,0.1

Type RM Length L Ch R = 1 ,25804   ,69.2,86.9,103.6
XS GIS Cut Line= 4
2232048.24478782413666.3734059142232473.96630613413568.958820577
2232560.59247723 413449.768170932232827.36223469413281.747439711
#Sta/Elev= 30
       0 2453.38    20.4 2441.74    36.9 2430.78    73.8 2410.92   110.7 2398.22
   135.3 2394.33   168.2 2392.37     242 2392.42   261.4 2390.67     320  2391.8
   356.9 2391.54   373.3 2389.66   393.9 2392.43   490.8  2390.9     5012388.985
   510.6 2387.32   525.5 2387.22   535.5 2388.71   587.1 2388.77   598.7 2395.04
   611.9 2398.12   659.2  2400.4   712.8  2400.3   796.3 2402.63   824.7 2405.66
   833.6 2409.54   838.8 2410.23   862.6 2407.42   870.4 2411.49   899.3 2432.79
#Mann= 10 ,-1,0
       0      .1       0      90     .06       0     320     .05       0
     400      .1       0     501    .045       0   535.5      .1       0
  536.72     .07       0  664.07     .06       0  684.07     .07       0
  784.07     .06       0
Bank Sta=501,535.5
XS Rating Curve= 0 ,0
Exp/Cntr(USF)=0,0
Exp/Cntr=0.5,0.3

Type RM Length L Ch R = 1 ,25718   ,60.7,60.1,57.7
XS GIS Cut Line= 4
2232056.53028357413681.1651428722232623.96871795413545.569465046
 2232762.5121279413457.137501246 2232850.9440917413303.855430661
#Sta/Elev= 30
       0  2450.6    61.3 2414.49    81.9 2403.98    90.1 2402.14   110.7 2396.32
   147.7 2392.54   242.3 2392.38   271.9 2390.27   332.8 2391.23   349.2 2389.76
   371.5 2392.69   390.3 2391.97   497.3    2391   512.9 2390.04   521.9 2387.23
   542.5 2386.61   550.7 2387.31   557.4 2390.48   563.1 2392.03   595.4  2393.9
   621.6  2396.3   650.1 2396.32   695.7 2399.11   799.1 2401.56   841.4 2404.37
   872.4 2408.43   895.5 2406.06   900.1  2407.8   918.8 2424.77   924.7  2427.7
#Mann= 8 ,-1,0
       0      .1       0    90.1     .06       0   371.5     .05       0
   390.3      .1       0   497.3     .07       0   512.9    .045       0
   557.4     .07       0   595.4     .06       0
#XS Ineff= 2 , 0
           504.9  2392.6  559.43          2393.2
Permanent Ineff=
       F       F
Bank Sta=512.9,557.4
XS Rating Curve= 0 ,0
Exp/Cntr(USF)=0,0
Exp/Cntr=0.5,0.3

Type RM Length L Ch R = 1 ,25657   ,100.2,100.6,103.4
XS GIS Cut Line= 3
2232100.75724018413758.2263411772232646.21613405413597.573052735
2232923.40305242413428.026164677
#Sta/Elev= 30
       0 2433.88    11.9 2427.44    24.4 2418.81    28.6 2416.55    45.3 2409.72
    55.1 2404.43    78.6 2393.69    99.5 2392.22   178.7 2391.27   287.2 2391.72
   393.4 2391.11   444.9 2390.07   462.3 2390.36   474.8 2392.58   478.9 2392.36
   482.3 2389.92   487.3  2387.5   495.6  2385.8   512.3 2386.53     529 2389.72
   533.1 2391.14   541.5 2392.41   683.5 2396.18   730.3 2398.78   785.6 2400.81
   814.7 2402.87     838  2403.5     871 2406.07   880.4 2406.32   893.6 2405.22
#Mann= 11 ,-1,0
       0      .1       0      40     .06       0     140     .05       0
     230     .06       0   482.3    .045       0     529     .06       0
     550     .05       0  578.63     .06       0  668.63     .05       0
  768.63     .06       0  893.55     .05       0
#XS Ineff= 2 , 0
          480.97 2391.41  530.82         2391.41
Permanent Ineff=
       F       F
Bank Sta=482.3,529
XS Rating Curve= 0 ,0
Exp/Cntr=0.5,0.3

Type RM Length L Ch R = 1 ,25557   ,114.3,112.3,109.3
XS GIS Cut Line= 2
2232094.85080122413856.5552044072232933.48059125413622.210500339
#Sta/Elev= 30
       0 2443.53     9.7 2438.88    22.1 2431.62    30.4  2429.4      72 2406.22
    84.4 2400.76    92.7 2395.07    96.9 2393.98   105.2 2393.79   113.5 2391.88
   238.1 2390.08   379.3 2389.54   425.8 2390.24   487.3 2388.84   499.8 2389.69
     507 2388.67   512.2    2387   520.5 2386.14   529.7 2386.36   537.1 2388.69
   541.3  2389.6   566.2 2390.42   603.6 2390.26   703.3 2398.74     778  2402.3
   812.1 2409.61     832 2415.77   844.3 2421.72   852.8 2423.55   870.8 2429.29
#Mann= 6 ,-1,0
       0      .1       0      50     .06       0     240     .05       0
     507    .045       0   537.1     .05       0     860      .1       0
#XS Ineff= 2 , 0
             189 2398.59
Permanent Ineff=
       F       F
Bank Sta=507,537.1
XS Rating Curve= 0 ,0
Exp/Cntr(USF)=0,0
Exp/Cntr=0.3,0.1

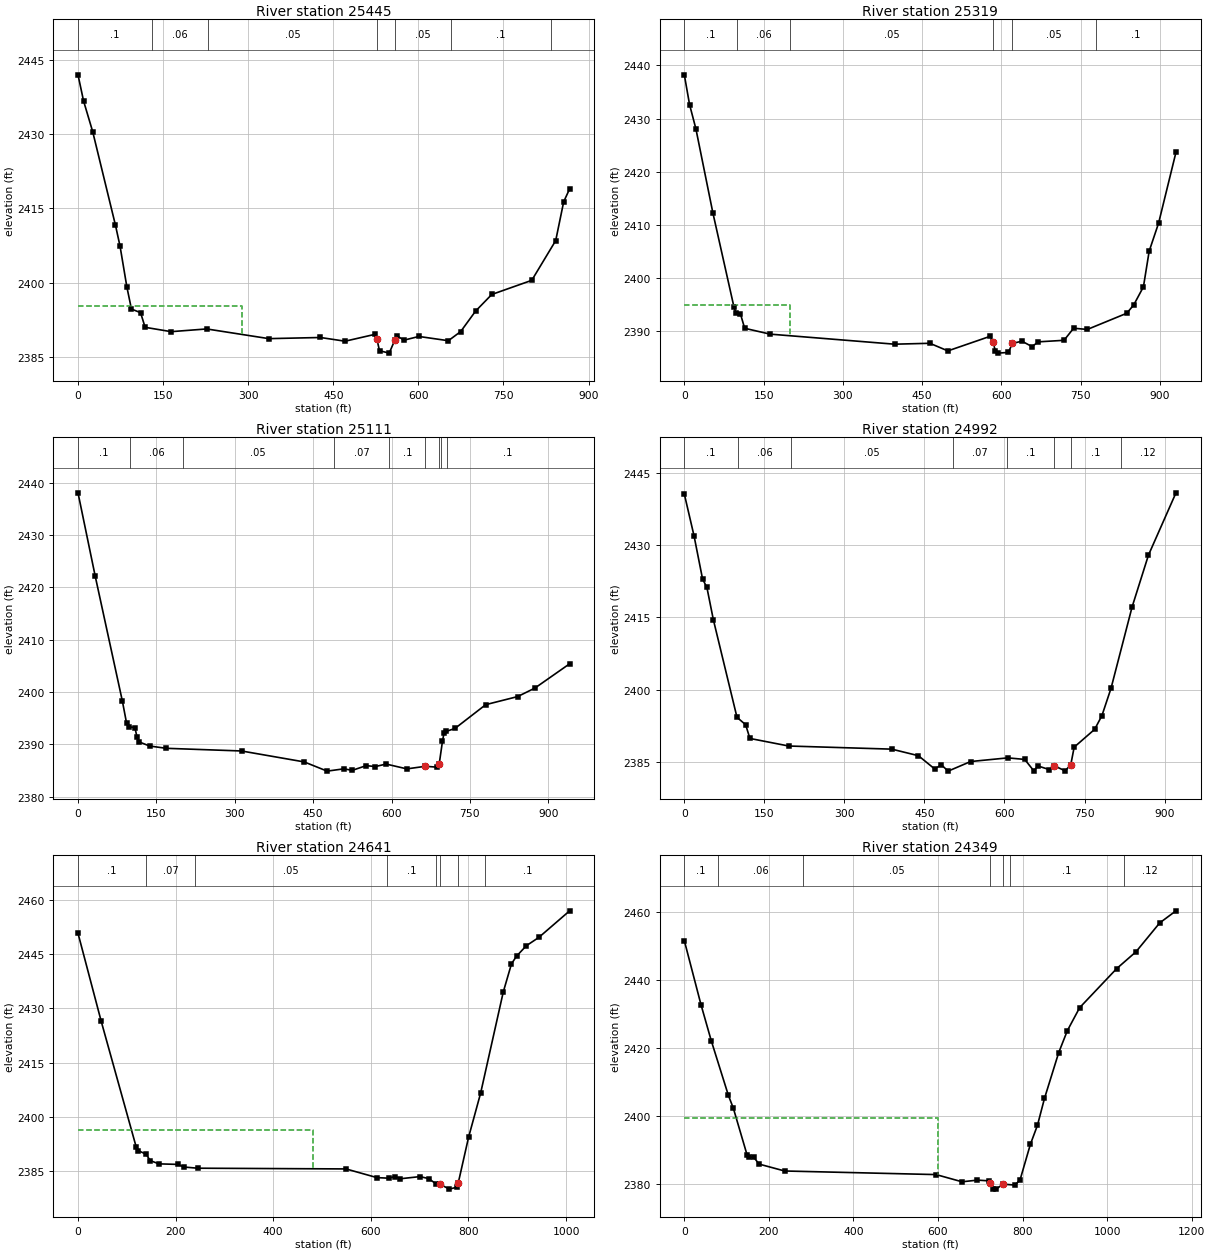
Type RM Length L Ch R = 1 ,25445   ,129.4,125.6,120.1
XS GIS Cut Line= 4
2232106.37842766413903.7511603662232372.90300654413929.477471068
2232766.00103407413764.8290825722232913.15553129413674.272468899
#Sta/Elev= 30
       0    2442     9.8 2436.72    25.9 2430.51    66.1 2411.56    74.1 2407.37
    86.2 2399.08    94.2 2394.64   110.3 2393.91   118.3 2390.95   164.2 2390.07
   226.8 2390.62   336.4 2388.66   427.4 2388.89   470.8 2388.14   522.8 2389.51
     527 2388.51   531.5 2386.22   548.6 2385.73   558.4 2388.34   561.9 2389.23
   574.9 2388.36   600.9  2389.1   652.9 2388.24   674.6 2390.09   700.9 2394.23
   729.4 2397.59   799.9 2400.45   842.1 2408.48   856.2 2416.34   866.7 2418.95
#Mann= 7 ,-1,0
       0      .1       0     130     .06       0     230     .05       0
     527    .045       0   558.4     .05       0  657.76      .1       0
  833.95     .05       0
#XS Ineff= 2 , 0
          289.62 2395.23
Permanent Ineff=
       F       F
Bank Sta=527,558.4
XS Rating Curve= 0 ,0
Exp/Cntr(USF)=0,0
Exp/Cntr=0.3,0.1

Type RM Length L Ch R = 1 ,25319   ,206.2,207.9,211.2
XS GIS Cut Line= 3
2232138.29393846 414128.845428962232436.45723349414107.258463346
2232953.73144706413744.880035293
#Sta/Elev= 30
       0 2438.23     9.9 2432.65    21.9 2428.08      54 2412.31    94.1 2394.53
    98.1 2393.41   106.2 2393.31   114.2  2390.6   162.3  2389.5   397.9 2387.61
   464.7 2387.78   498.8 2386.35   578.8 2389.09   584.6 2387.98   588.4 2386.38
   593.2 2385.93   613.3 2386.06   620.9 2387.76   639.1 2388.17   658.1 2387.15
   669.8 2388.05   718.6 2388.34   736.8 2390.61   762.7 2390.38   837.3 2393.42
   850.5 2394.98   868.9 2398.39   879.8  2405.1   897.6 2410.36   930.5 2423.68
#Mann= 6 ,-1,0
       0      .1       0     100     .06       0     200     .05       0
   584.6    .045       0   620.9     .05       0  778.94      .1       0
#XS Ineff= 2 , 0
           200.4 2394.98
Permanent Ineff=
       F       F
Bank Sta=584.6,620.9
XS Rating Curve= 0 ,0
Exp/Cntr=0.3,0.1

Type RM Length L Ch R = 1 ,25111   ,119.7,119.3,123.3
XS GIS Cut Line= 3
2232139.30810536414144.5494285412232724.83893695414135.287956688
2233044.87424209413980.930092473
#Sta/Elev= 30
       0 2438.08    32.9 2422.18    84.9  2398.3    92.9 2394.11    96.9 2393.39
   108.9 2393.22   112.9 2391.44   116.9  2390.5   136.9 2389.71   168.9 2389.27
   312.9 2388.76   432.9 2386.67   476.8 2384.91   508.9 2385.35   524.9 2385.06
   551.6 2385.96   568.9 2385.78   589.7 2386.26   629.3 2385.34   664.8 2385.83
     687 2385.67   691.2 2386.23   697.5 2390.61   700.3 2392.12   704.8  2392.5
   721.5 2393.07   780.3 2397.61   841.3 2399.15   874.3 2400.77   940.9 2405.42
#Mann= 9 ,-1,0
       0      .1       0     100     .06       0     200     .05       0
     490     .07       0   595.6      .1       0   664.8    .045       0
   691.2      .1       0   695.6     .05       0   705.6      .1       0
Bank Sta=664.8,691.2
XS Rating Curve= 0 ,0
Exp/Cntr(USF)=0,0
Exp/Cntr=0.3,0.1

Type RM Length L Ch R = 1 ,24992   ,340.3,350.3,352.5
XS GIS Cut Line= 4
2232138.27905293414262.8904577732232529.31897561414314.343079178
2232874.05153902414199.089207231 2233023.2641411414265.977615057
#Sta/Elev= 30
       0 2440.57    18.1 2431.96    34.2 2422.94    42.3 2421.21    54.4 2414.51
    98.7 2394.26   114.9 2392.73   122.9 2389.88   195.6 2388.31   388.8 2387.66
   438.7  2386.3   469.1 2383.56   481.8  2384.4   494.4  2383.1   536.5 2385.09
   606.2 2385.85   637.9 2385.53   654.7  2383.2   663.1 2384.16   684.2 2383.41
   692.7 2384.25   713.7 2383.15   724.3 2384.46   730.6 2388.07     769 2391.77
   782.6 2394.61   799.7 2400.29   839.1 2417.13   869.8  2427.9   921.4 2440.83
#Mann= 8 ,-1,0
       0      .1       0     100     .06       0     200     .05       0
  504.41     .07       0  604.41      .1       0   692.7    .045       0
   724.3      .1       0   817.9     .12       0
Bank Sta=692.7,724.3
XS Rating Curve= 0 ,0
Exp/Cntr(USF)=0,0
Exp/Cntr=0.3,0.1

Type RM Length L Ch R = 1 ,24641   ,286.4,292,296.1
XS GIS Cut Line= 4
2232098.35587469414484.2058488332232565.90327483414562.484842296
2232926.53321286414539.7055609322233087.34793647414478.609354069
#Sta/Elev= 30
       0 2450.72    47.6 2426.38   119.5 2391.56   123.5 2390.68   139.7 2389.67
   147.8 2387.94   165.7 2387.02   204.6 2386.87   216.8 2386.15   245.2 2385.82
   549.1 2385.62   612.6 2383.22   636.7 2383.06   648.7 2383.52   660.7 2382.91
   700.8  2383.5   718.7 2382.95   732.8 2381.56   741.3 2381.42   760.9 2380.04
   776.9  2380.6     779 2381.66   800.2 2394.32     825 2406.57   871.4 2434.51
   888.2 2442.28   898.8 2444.43   918.5 2447.26   944.3 2449.58  1007.4 2456.92
#Mann= 8 ,-1,0
       0      .1       0     140     .07       0     240     .05       0
  634.06      .1       0  734.06     .07       0   741.3    .045       0
     779     .07       0  834.06      .1       0
#XS Ineff= 2 , 0
          481.93 2396.48
Permanent Ineff=
       F       F
Bank Sta=741.3,779
XS Rating Curve= 0 ,0
Exp/Cntr=0.3,0.1

Type RM Length L Ch R = 1 ,24349   ,300.2,311.5,314.3
XS GIS Cut Line= 3
2232061.09421017414731.4258617592232863.51454285414838.177190784
2233203.07301479414740.452214512
#Sta/Elev= 30
       0 2451.63    39.4 2432.79    63.6 2422.21     104 2406.16   116.1 2402.22
   148.4 2388.55   152.4    2388   164.5 2387.82   176.6 2385.85   237.2 2383.81
   595.5 2382.75   656.8 2380.63   693.1 2381.12   721.4  2380.9   723.32380.223
   729.5 2378.55   737.5 2378.47   753.7 2379.93   781.9 2379.67     794 2381.18
   818.5 2391.68   835.2 2397.26   851.8 2405.18   885.4 2418.65   905.9 2425.13
     935  2431.9  1022.5 2443.39  1068.2 2448.35  1124.3 2456.85  1162.8 2460.41
#Mann= 7 ,-1,0
       0      .1       0      80     .06       0     280     .05       0
   723.3    .045       0   753.7     .05       0     770      .1       0
 1039.49     .12       0
#XS Ineff= 2 , 0
           601.1 2399.38
Permanent Ineff=
       F       F
Bank Sta=723.3,753.7
XS Rating Curve= 0 ,0
Exp/Cntr=0.3,0.1

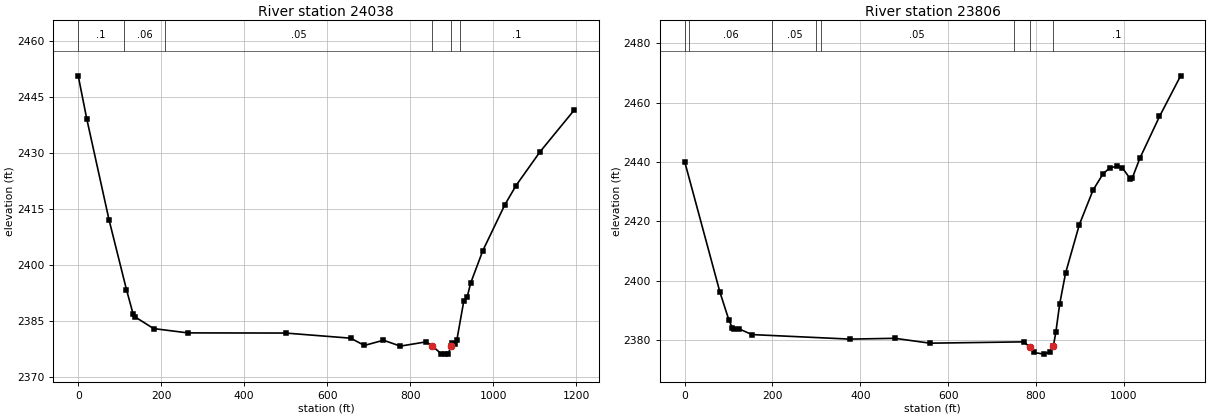
Type RM Length L Ch R = 1 ,24038   ,224.6,232.3,236.2
XS GIS Cut Line= 3
 2232036.2125215414879.8416733762232971.76279822415118.705573813
2233178.28054547415218.232198995
#Sta/Elev= 30
       0 2450.74    20.6 2439.18    74.3 2412.06   116.2 2393.37   132.1 2386.85
   136.2 2386.07   181.6 2382.88   264.1 2381.72   499.5 2381.68   656.4  2380.3
   689.4 2378.35   735.4 2379.75   776.1 2378.17     838 2379.31   852.92378.227
   875.2 2376.04   883.4 2376.02   891.7 2376.05   897.52378.153   899.9 2378.98
   908.2 2378.79   912.3 2379.86   928.8  2390.2   937.1 2391.35   945.3 2395.04
   974.9 2403.84  1027.6 2416.07  1054.8 2421.28  1112.5 2430.33  1194.8 2441.53
#Mann= 6 ,-1,0
       0      .1       0     110     .06       0     210     .05       0
   852.9    .045       0   897.5     .05       0     920      .1       0
Bank Sta=852.9,897.5
XS Rating Curve= 0 ,0
Exp/Cntr(USF)=0,0
Exp/Cntr=0.3,0.1

Type RM Length L Ch R = 1 ,23806   ,500.4,506.8,512.8
XS GIS Cut Line= 3
2232036.56373455415026.9103765732232313.44172449415065.113059833
2233074.87955317415442.990921381
#Sta/Elev= 30
       0 2440.13    80.4 2396.07   100.6  2386.8   108.6 2384.08   112.7 2383.74
   124.8 2383.71     153 2381.84   376.3 2380.31   478.6 2380.58   558.6 2378.94
     773 2379.39     786 2377.53   794.9 2375.81   818.4 2375.25   831.8 2375.99
   839.7 2377.93   845.2 2382.54   854.1 2392.19   867.5 2402.57   898.8 2418.88
     930 2430.51   953.1 2436.07     968 2437.96   983.6 2438.57     997 2437.98
  1014.9 2434.32  1019.4  2434.6  1036.6 2441.23  1081.4 2455.34  1129.5 2469.04
#Mann= 8 ,-1,0
       0      .1       0      10     .06       0     200     .05       0
   299.5      .1       0   309.5     .05       0   749.5      .1       0
     786    .045       0   839.7      .1       0
Bank Sta=786,839.7
XS Rating Curve= 0 ,0
Exp/Cntr=0.3,0.1