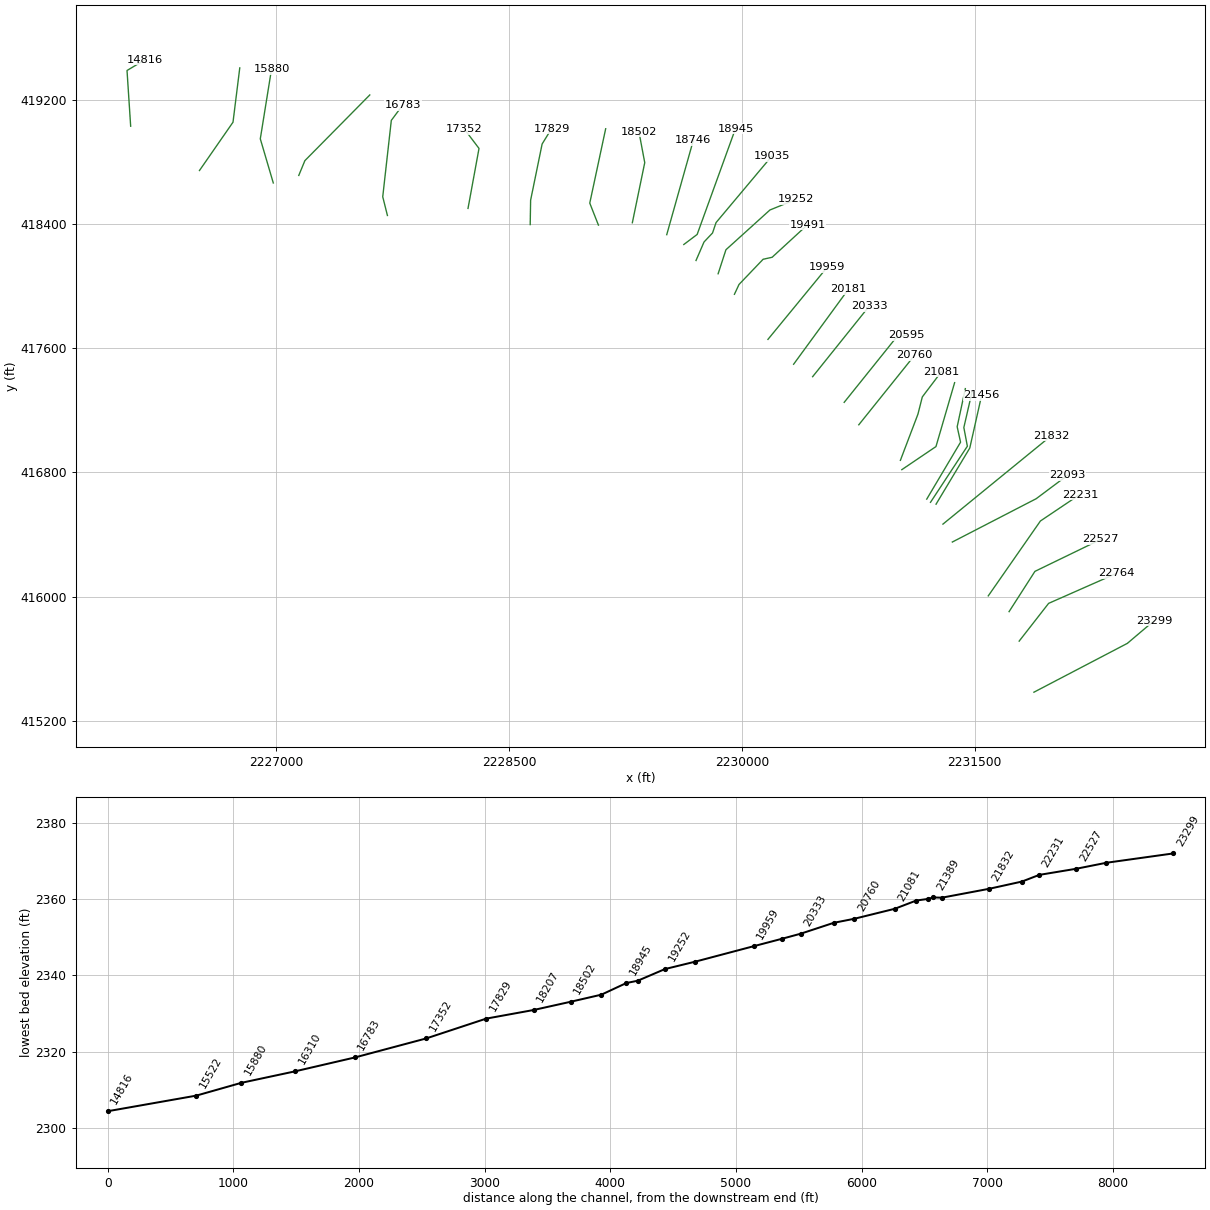
HEC-RAS study BEAVERCK.prj: BEAVERCK

--- BEAVERCK.g01 (geometry) --- (continued)

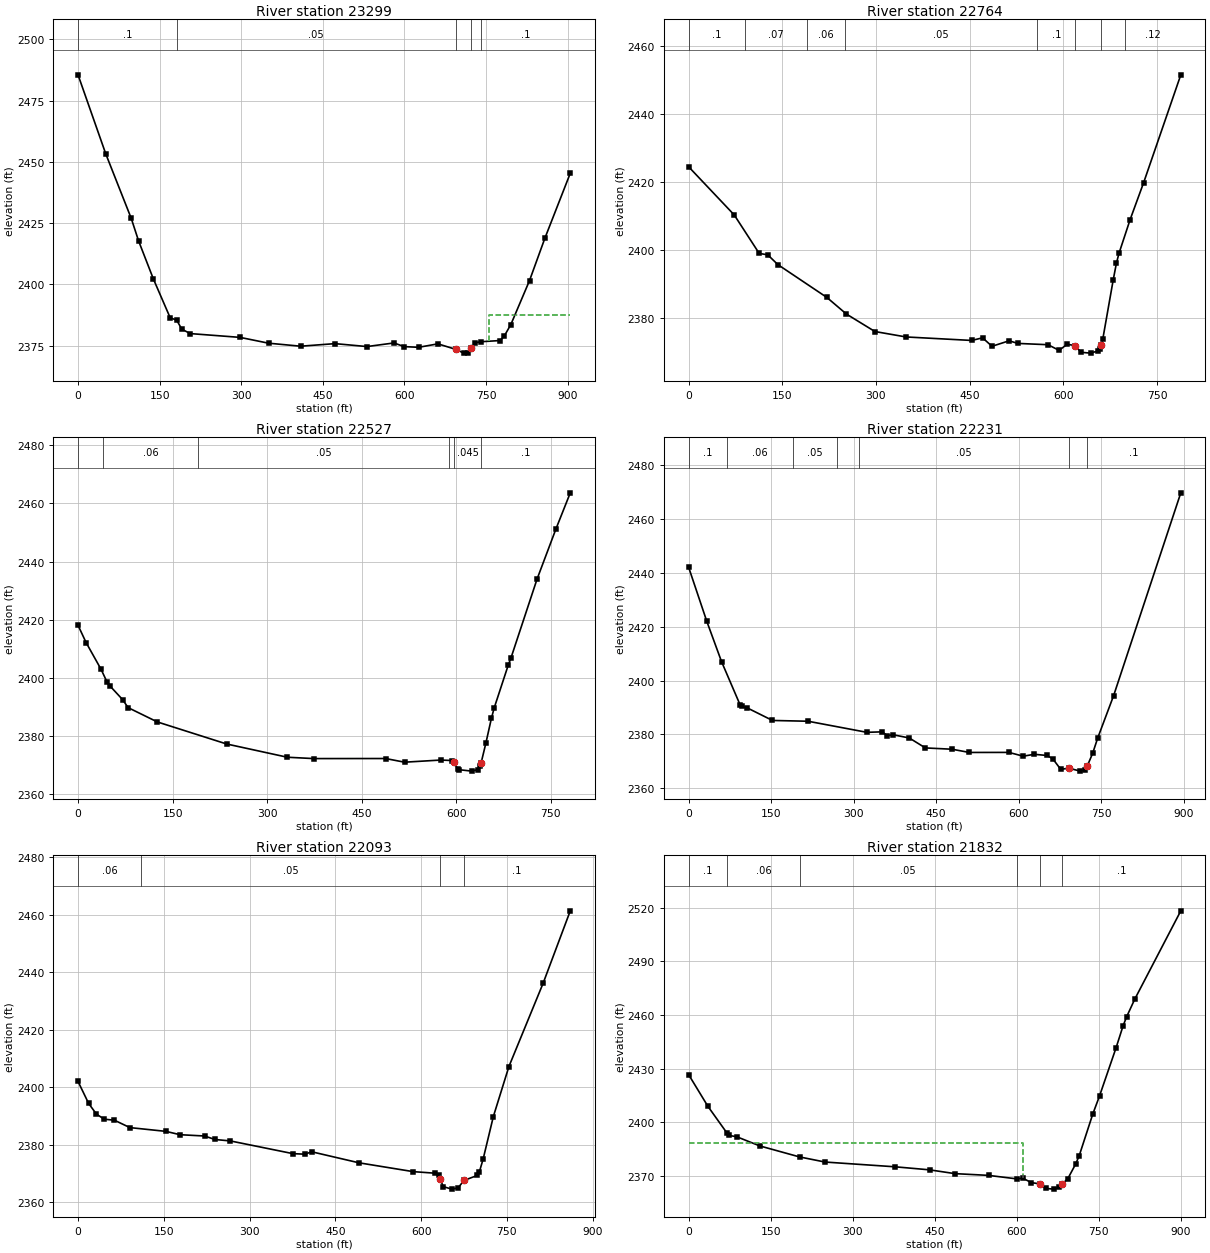
Type RM Length L Ch R = 1 ,23299   ,536.2,534.6,523.6
XS GIS Cut Line= 3
2231881.53274594415383.163261843 2232483.2282744415697.803554519
2232655.51035797415843.787148318
#Sta/Elev= 30
       0 2485.48    50.9  2453.3    97.8 2426.95   111.3 2417.77   138.4  2402.3
   169.4 2386.42   181.3 2385.46   190.7  2381.8   206.1 2379.98   297.8 2378.43
   350.2 2376.06   409.2 2374.83   472.4 2375.88   531.1 2374.69   580.8 2376.16
   599.2 2374.67   625.9 2374.38   661.5 2375.79   694.32373.551     709 2372.01
   716.9 2372.26   723.12374.295   730.3 2376.23   739.9 2376.65   775.7 2377.14
   783.2 2378.88   795.6 2383.68   829.9 2401.61     858 2418.79   904.8 2445.37
#Mann= 5 ,-1,0
       0      .1       0   181.3     .05       0   694.3    .045       0
   723.1     .05       0   739.9      .1       0
#XS Ineff= 2 , 0
       0                   755.9       0 2387.44
Permanent Ineff=
       F       F
Bank Sta=694.3,723.1
XS Rating Curve= 0 ,0
Exp/Cntr=0.3,0.1

Type RM Length L Ch R = 1 ,22764   ,235.9,237.5,237.5
XS GIS Cut Line= 3
2231786.26967592 415712.385769592231975.93724084415955.720062164
 2232414.3978619416149.432001899
#Sta/Elev= 30
       0 2424.53    73.2 2410.28   113.1 2398.95   126.7 2398.55     143 2395.65
   221.4 2385.97   252.7 2381.07   298.3 2375.92   348.1 2374.32   453.1 2373.29
   470.6 2374.06   485.7 2371.57     513 2373.18   527.4 2372.41   575.5 2372.03
     593 2370.37   606.1 2372.16   618.82371.765     628  2369.8   643.4 2369.55
   655.6  2370.2   658.6 2370.87  660.13 2371.94     663 2373.65   679.8 2391.24
   684.9 2396.12   688.9 2398.94   706.7 2408.89   728.4 2419.82   787.9 2451.62
#Mann= 8 ,-1,0
       0      .1       0      90     .07       0     190     .06       0
     250     .05       0  558.52      .1       0   618.8    .045       0
  660.13      .1       0  698.52     .12       0
Bank Sta=618.8,660.13
XS Rating Curve= 0 ,0
Exp/Cntr=0.3,0.1

Type RM Length L Ch R = 1 ,22527   ,293,295.9,299.2
XS GIS Cut Line= 3
2231721.22414846415902.3794682532231887.79230555416162.112865744
2232312.68226558416368.205670275
#Sta/Elev= 30
       0  2418.1    12.8 2412.16    36.6 2402.94    46.1 2398.57    50.8 2397.22
    70.8 2392.54    79.4 2389.81   125.8 2384.89   235.8 2377.31   332.1 2372.76
     374  2372.3   487.8 2372.32   517.9 2371.06   575.7  2371.8   593.5 2371.63
   596.3 2371.02   602.4 2368.73   604.5 2368.48   624.6 2367.99   634.5 2368.54
     638  2369.7   639.5 2370.93   646.9 2377.59   655.7 2386.15   660.2 2389.76
   682.3 2404.35   686.9 2406.99     728 2433.91     758 2451.17   780.8 2463.61
#Mann= 6 ,-1,0
       0      .1       0      40     .06       0     190     .05       0
  588.56      .1       0   596.3    .045       0   639.5      .1       0
Bank Sta=596.3,639.5
XS Rating Curve= 0 ,0
Exp/Cntr(USF)=0,0
Exp/Cntr=0.3,0.1

Type RM Length L Ch R = 1 ,22231   ,137,137.8,138.7
XS GIS Cut Line= 3
2231587.12266606416004.0142759672231923.08216934416486.779612608
2232177.16918862416657.582553349
#Sta/Elev= 30
       0 2442.22    33.2 2422.01    59.9 2407.08    93.5 2391.07    96.4 2390.39
   106.9 2389.84   152.5  2385.2   217.1 2384.91     324 2380.79     352 2380.97
   360.8 2379.55   371.8 2379.88     401 2378.69   430.3 2374.99   478.6 2374.51
   510.2 2373.31     582 2373.33     608 2371.92     628 2372.62   651.2 2372.19
   661.8 2370.93   676.2 2367.02   690.7 2367.47   711.7 2366.37   719.6  2366.7
   724.4 2368.29   734.1 2372.96   743.4 2378.71   772.3 2394.46   894.3  2469.8
#Mann= 7 ,-1,0
       0      .1       0      70     .06       0     190     .05       0
     270     .07       0     310     .05       0   690.7    .045       0
   724.4      .1       0
Bank Sta=690.7,724.4
XS Rating Curve= 0 ,0
Exp/Cntr(USF)=0,0
Exp/Cntr=0.3,0.1

Type RM Length L Ch R = 1 ,22093   ,259.5,261.2,261.6
XS GIS Cut Line= 3
2231355.62115961416351.2665356562231896.26187286416630.762256869
2232098.11989374416781.802873888
#Sta/Elev= 30
       0 2402.03    18.6 2394.38    32.1 2390.71    45.7 2388.93    63.7 2388.56
    90.7    2386   153.7 2384.69   178.4 2383.53   221.3 2383.08   239.3 2381.87
   266.3 2381.37   375.8 2376.95   396.9 2376.76   408.5  2377.6   491.4 2373.76
     586  2370.7   624.6 2370.15   630.3 2369.43   633.5 2368.01   638.5  2365.5
   653.5 2364.62   664.6 2365.05   674.62367.623   698.4  2369.4   701.7 2370.59
   708.4 2375.12   726.2 2389.85   753.4 2407.22   813.2 2436.16   860.7 2461.33
#Mann= 4 ,-1,0
       0     .06       0     110     .05       0   633.5    .045       0
   674.6      .1       0
Bank Sta=633.5,674.6
XS Rating Curve= 0 ,0
Exp/Cntr(USF)=0,0
Exp/Cntr=0.3,0.1

Type RM Length L Ch R = 1 ,21832   ,360.2,375.8,391.1
XS GIS Cut Line= 2
2231295.08668896416466.760622872 2231991.9134626417035.833679461
#Sta/Elev= 30
       0 2426.77    35.4 2408.97    70.7 2393.85    73.6 2392.73    87.8 2392.02
   130.4 2386.84   202.8 2380.72   249.3 2377.86   377.7 2375.19   440.4  2373.5
   486.9 2371.38   548.3  2370.4   600.5 2368.43   610.8 2368.88   626.3 2366.36
   641.8 2365.68   653.5 2363.08   667.6 2362.72   677.9 2363.74   683.1 2365.56
   693.3 2368.64   707.5 2376.72   714.1 2381.48   738.8 2404.65   751.2 2414.83
   781.4 2441.71   794.3 2454.05   800.6 2458.97   815.5 2468.84   899.7 2518.23
#Mann= 6 ,-1,0
       0      .1       0    70.7     .06       0   202.8     .05       0
   600.5      .1       0   641.8    .045       0   683.1      .1       0
#XS Ineff= 2 , 0
       0     611 2388.44               0
Permanent Ineff=
       F       F
Bank Sta=641.8,683.1
XS Rating Curve= 0 ,0
Exp/Cntr=0.3,0.1

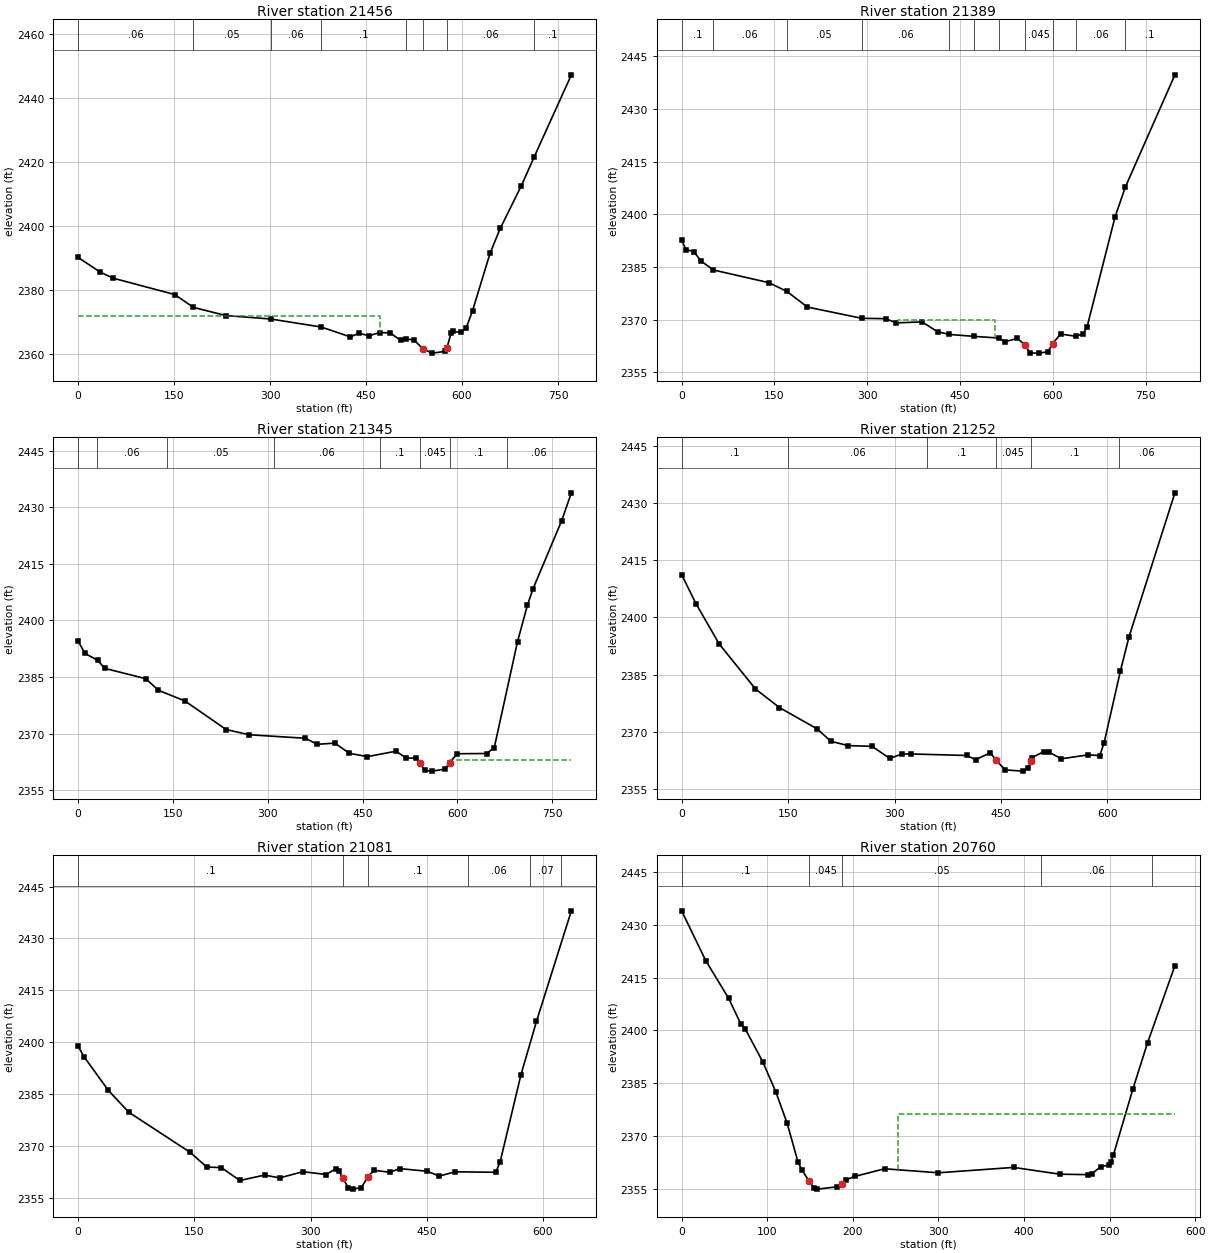
Type RM Length L Ch R = 1 ,21456   ,65,67.1,67
XS GIS Cut Line= 3
2231250.68368785416595.335401959 2231467.9610229416957.066349881
2231544.56603036 417297.52613525
#Sta/Elev= 30
       0 2390.23    34.5 2385.65    54.9 2383.75   151.1 2378.65   180.3 2374.64
   230.8 2372.11   300.8 2371.03   380.1 2368.53   425.6 2365.44   438.5 2366.58
   454.9 2365.82   471.3  2366.8   487.7 2366.71   504.1 2364.37   512.3 2364.77
   524.6 2364.56   539.4 2361.66   553.3 2360.39   572.9 2360.91   576.2 2361.91
   582.9 2366.57   586.1 2367.15   598.4 2366.83   606.6  2368.3   616.4 2373.57
     644 2391.62   659.8 2399.29   692.7 2412.56   712.8 2421.55   770.9 2447.15
#Mann= 8 ,-1,0
       0     .06       0   180.3     .05       0   300.8     .06       0
   380.1      .1       0   512.3     .06       0   539.4    .045       0
   576.2     .06       0   712.8      .1       0
#XS Ineff= 2 , 0
       0   471.3 2371.89               0
Permanent Ineff=
       F       F
Bank Sta=539.4,576.2
XS Rating Curve= 0 ,0
Exp/Cntr(USF)=0,0
Exp/Cntr=0.5,0.3

Type RM Length L Ch R = 1 ,21389   ,45.2,44,45
XS GIS Cut Line= 4
2231214.86874251416607.2737170722231452.44121326416969.004664993
2231429.75841454417089.581647634 2231483.9868599417325.321611575
#Sta/Elev= 30
       0 2392.59     7.1 2389.95    19.6 2389.39    31.5 2386.66    51.4 2384.14
     141 2380.53     170 2378.05   203.3 2373.58   291.2 2370.37   330.3 2370.26
   346.8 2369.06   388.6 2369.35   413.8 2366.54   432.9 2365.77   472.8 2365.23
   512.9 2364.74   522.5  2363.7   542.9 2364.64   555.1 2362.75   563.3 2360.48
   578.4 2360.45     592 2360.85   599.7 2363.12   612.5 2365.89   637.2 2365.25
   649.5 2366.01   655.5 2367.99   700.6 2399.22     717 2407.66   797.4 2439.75
#Mann= 11 ,-1,0
       0      .1       0    51.4     .06       0     170     .05       0
   291.2     .06       0   432.9      .1       0   472.8     .06       0
   512.9      .1       0   555.1    .045       0   599.7      .1       0
   637.2     .06       0     717      .1       0
#XS Ineff= 3 ,-1
     506     542  2362.3     607   755.9    2363     350     506    2370
Permanent Ineff=
       F       F       F
Bank Sta=555.1,599.7
XS Rating Curve= 0 ,0
Exp/Cntr(USF)=0,0
Exp/Cntr=0.5,0.3

Type RM Length L Ch R = 1 ,21345   ,94.9,92.9,91
XS GIS Cut Line= 4
2231190.63191897416627.8976038562231408.60546174416994.994039224
2231386.78048014417094.3569736792231439.34624796417340.405629542
#Sta/Elev= 30
       0 2394.53    10.9 2391.28    31.2  2389.4    42.2  2387.3   107.1 2384.56
   127.1 2381.49     169 2378.66   234.1 2371.09   270.6  2369.7   359.7 2368.77
   378.3 2367.17   406.2 2367.48   429.2 2364.78   457.8  2363.9   502.7 2365.34
   519.3 2363.52   535.3 2363.53   540.9 2362.09   549.1 2360.26   560.2 2360.06
   580.6  2360.6   587.7 2362.34   599.6 2364.67   646.1 2364.73   658.3 2366.26
   695.2 2394.42   710.8 2404.07   719.7 2408.41   764.8 2426.36   780.3 2433.83
#Mann= 8 ,-1,0
       0      .1       0      30     .06       0     140     .05       0
     310     .06       0  476.93      .1       0   540.9    .045       0
   587.7      .1       0  678.67     .06       0
#XS Ineff= 2 , 0
             539  2362.3   587.8            2363
Permanent Ineff=
       F       F
Bank Sta=540.9,587.7
XS Rating Curve= 0 ,0
Exp/Cntr=0.5,0.3

Type RM Length L Ch R = 1 ,21252   ,171.3,171.5,172.2
XS GIS Cut Line= 3
2231030.05733913416817.7818539252231250.15239138416966.725632832
2231370.26662971  417378.8131239
#Sta/Elev= 30
       0 2411.22    20.3 2403.58    52.9 2393.03     104 2381.22   137.8 2376.33
   191.2  2370.7   210.2 2367.48   234.4 2366.34   268.3 2366.15   293.3 2362.97
     310 2364.12   322.5 2364.15   401.6 2363.75   414.1 2362.65     435 2364.45
   443.2 2362.49   455.8 2359.96   480.8 2359.64   488.7 2360.57   491.72362.321
   493.3 2363.17     510 2364.73   517.8 2364.61     535 2362.88   573.2 2363.92
   589.1 2363.72   595.2 2367.02   618.3    2386   630.3 2394.86     695  2432.7
#Mann= 6 ,-1,0
       0      .1       0     150     .06       0  345.76      .1       0
   443.2    .045       0   491.7      .1       0  615.76     .06       0
Bank Sta=443.2,491.7
XS Rating Curve= 0 ,0
Exp/Cntr(USF)=0,0
Exp/Cntr=0.3,0.1

Type RM Length L Ch R = 1 ,21081   ,326.1,320.5,304.4
XS GIS Cut Line= 4
2231020.89345943416877.9659228692231133.84784386417175.219503541
2231162.07973489417286.7354731162231284.88846087417449.068846547
#Sta/Elev= 30
       0 2398.85     7.7 2395.76    39.1 2386.03    65.5 2379.71   144.6 2368.13
     166 2363.86   184.9  2363.7   208.8 2359.97   240.7 2361.54   260.2 2360.71
   290.1 2362.52     320  2361.7   332.4  2363.3   336.5 2362.81   341.3 2360.78
   348.9  2357.8   354.4 2357.47   365.4 2357.89   374.2 2361.11   381.9 2362.91
   402.5 2362.34   414.9 2363.41   450.5 2362.64   466.2 2361.23   486.2 2362.48
   539.1 2362.35   544.8 2365.45   571.5 2390.53   591.6 2406.02   636.6    2438
#Mann= 6 ,-1,0
       0      .1       0   341.3    .045       0   374.2      .1       0
  503.03     .06       0  583.03     .07       0  623.03      .1       0
Bank Sta=341.3,374.2
XS Rating Curve= 0 ,0
Exp/Cntr(USF)=0,0
Exp/Cntr=0.3,0.1

Type RM Length L Ch R = 1 ,20760   ,164.1,164.9,165.4
XS GIS Cut Line= 2
2230752.84287714417107.1805590192231113.58370698417556.799564337
#Sta/Elev= 30
       0 2434.05    28.2 2419.88      55 2409.13    69.2 2401.84    74.4 2400.41
    94.9 2391.05   110.3 2382.39   123.3  2373.6   135.9 2362.67   140.4 2360.33
   148.9 2357.22   154.6  2355.3   158.7 2354.86   182.1 2355.53   187.2 2356.44
   192.3 2357.56     203 2358.52   237.1 2360.65     300 2359.51   387.9 2361.04
     442 2359.11   474.4 2358.98   479.5 2359.27   489.8 2361.25   498.9 2361.72
   501.7 2362.69   504.6 2364.63   527.3 2383.34   544.4 2396.46   576.4 2418.44
#Mann= 5 ,-1,0
       0      .1       0   148.9    .045       0   187.2     .05       0
     420     .06       0     550      .1       0
#XS Ineff= 2 , 0
                          252.51         2376.33
Permanent Ineff=
       F       F
Bank Sta=148.9,187.2
XS Rating Curve= 0 ,0
Exp/Cntr(USF)=0,0
Exp/Cntr=0.3,0.1

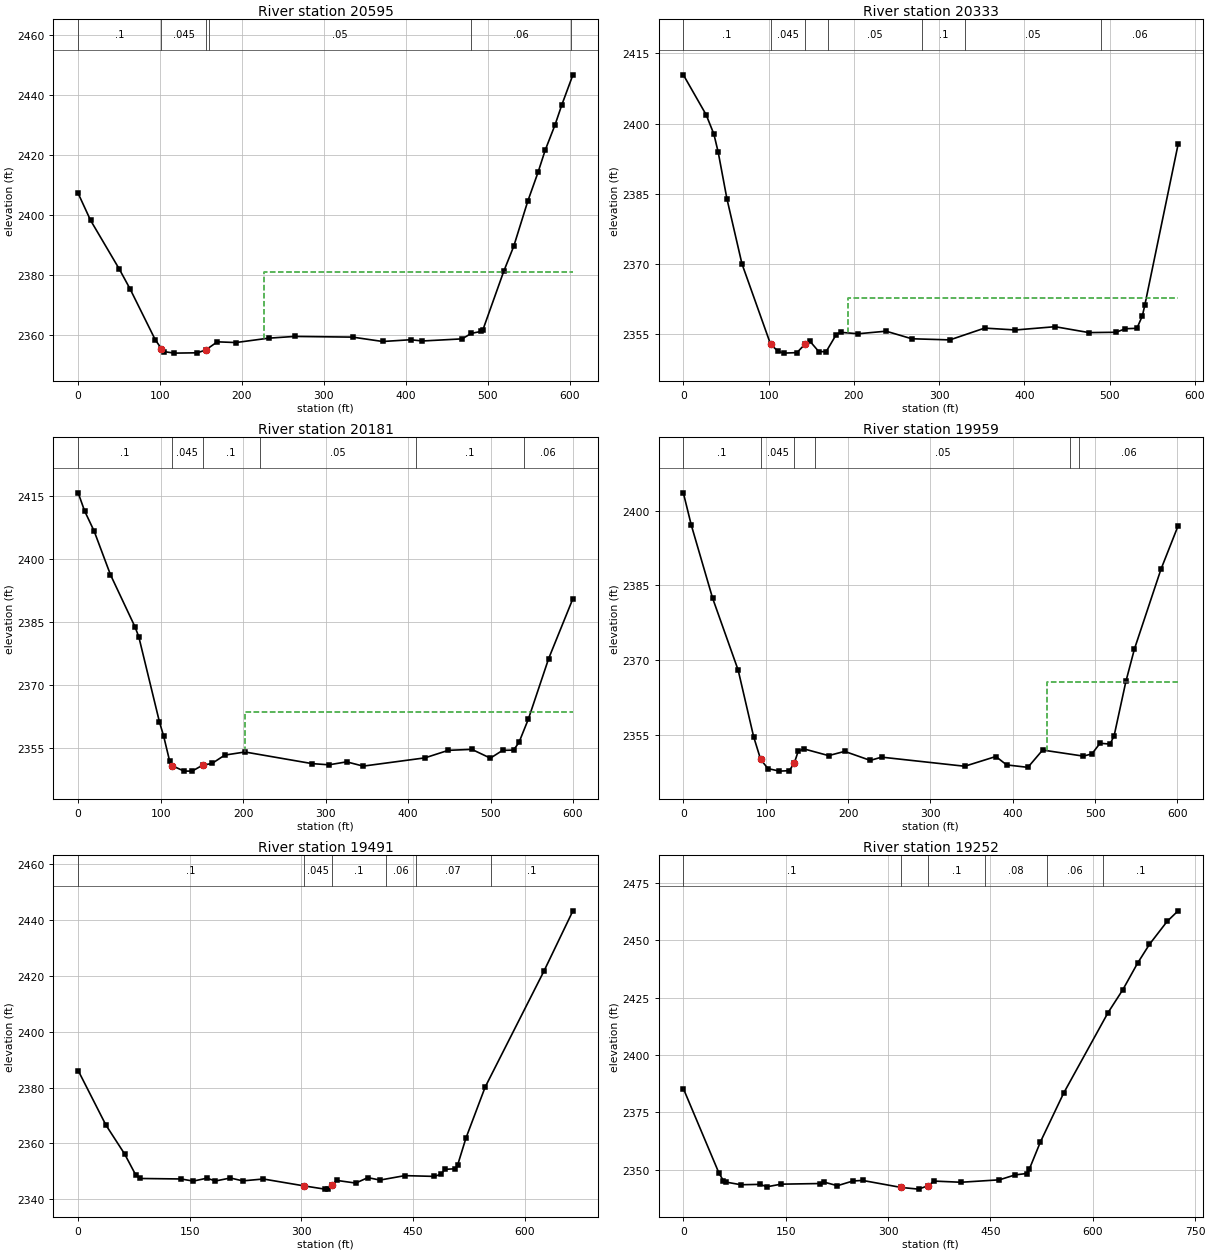
Type RM Length L Ch R = 1 ,20595   ,262.2,262.2,262.5
XS GIS Cut Line= 3
 2230658.7365737417251.8254328232230991.59405438417666.590251682
 2231061.3024273417685.760054235
#Sta/Elev= 30
       0  2407.1    15.1 2398.13    50.4 2381.75    63.3 2375.26    94.1 2358.27
   101.6  2355.3   104.6 2354.31   117.3 2353.79   145.3  2353.9   155.6 2354.81
   169.9 2357.56   192.6 2357.32   232.5 2358.78   264.3 2359.36   335.1 2359.13
   371.9 2357.67     406 2358.26   420.3 2357.84   468.8 2358.55     480 2360.37
   491.4 2361.01   494.2 2361.57   519.7 2381.14   531.8 2389.41     549 2404.51
   561.5 2414.11   570.2 2421.47   582.2 2429.91   590.5  2436.6   604.1 2446.65
#Mann= 6 ,-1,0
       0      .1       0   101.6    .045       0   155.6      .1       0
     160     .05       0     480     .06       0  601.81      .1       0
#XS Ineff= 2 , 0
                           226.9          2380.7
Permanent Ineff=
       F       F
Bank Sta=101.6,155.6
XS Rating Curve= 0 ,0
Exp/Cntr(USF)=0,0
Exp/Cntr=0.3,0.1

Type RM Length L Ch R = 1 ,20333   ,150.9,152.1,153
XS GIS Cut Line= 2
2230455.45235692 417417.27197357     2230818.381      417869.939
#Sta/Elev= 30
       0 2410.43    26.7 2401.91    35.8 2397.78    40.9 2393.88    51.1 2383.95
    68.7 2370.06   102.4 2352.79   111.4  2351.3   117.8 2350.94   133.2 2351.05
   142.7 2352.85   148.6 2353.45   158.8 2351.28   167.4 2351.23   179.3  2354.9
   184.4 2355.39     205 2355.08   237.8 2355.63   267.9 2354.01   312.6 2353.77
   353.3 2356.29   389.5 2355.89     436 2356.59   475.6 2355.33   507.4  2355.4
   518.3 2356.15   531.9 2356.25   538.3 2358.91   541.1 2361.15   580.2 2395.57
#Mann= 7 ,-1,0
       0      .1       0   102.4    .045       0   142.7      .1       0
     170     .05       0     280      .1       0     330     .05       0
     490     .06       0
#XS Ineff= 2 , 0
                          193.62         2362.67
Permanent Ineff=
       F       F
Bank Sta=102.4,142.7
XS Rating Curve= 0 ,0
Exp/Cntr=0.3,0.1

Type RM Length L Ch R = 1 ,20181   ,223.3,221.8,220.7
XS GIS Cut Line= 2
2230332.84993031417497.5474473572230686.61992286417982.020639134
#Sta/Elev= 30
       0 2415.64     7.8 2411.35    19.4 2406.54    39.2 2396.19    68.9 2383.83
    73.5 2381.48    98.6 2361.23   103.6 2357.94   110.9 2351.98   113.5 2350.91
   128.3 2349.59   138.2 2349.58     151    2351   162.4 2351.41   177.8 2353.39
   202.3 2354.12   283.7 2351.36   304.1 2351.08   325.6 2351.78   345.6 2350.77
   420.5 2352.73   448.7 2354.51   477.3 2354.75   499.8 2352.66   514.6 2354.51
   527.9 2354.57   534.5 2356.39     546    2362   570.5 2376.31   599.9 2390.53
#Mann= 6 ,-1,0
       0      .1       0   113.5    .045       0     151      .1       0
     220     .05       0     410      .1       0     540     .06       0
#XS Ineff= 2 , 0
                           202.9         2363.57
Permanent Ineff=
       F       F
Bank Sta=113.5,151
XS Rating Curve= 0 ,0
Exp/Cntr(USF)=0,0
Exp/Cntr=0.3,0.1

Type RM Length L Ch R = 1 ,19959   ,483.7,467.6,451.3
XS GIS Cut Line= 2
2230167.41976067417657.7226112242230548.55028959418122.137218694
#Sta/Elev= 30
       0 2403.62     9.6 2397.17    35.5 2382.46    66.6 2367.96    85.4 2354.56
    93.9    2350   102.8 2348.17   116.7 2347.66   128.7 2347.75   134.9 2349.36
   139.4 2351.62   146.2 2352.14   176.4 2350.78   195.9 2351.63     227 2349.82
   240.8 2350.47   341.7 2348.64   379.5  2350.6   392.6 2348.91   418.4 2348.42
   436.3  2351.9   485.7 2350.68   496.1 2351.12     506 2353.26   518.2  2353.1
   523.1 2354.77   537.4 2365.69   547.8 2372.23   579.9 2388.21   600.8 2396.99
#Mann= 6 ,-1,0
       0      .1       0    93.9    .045       0   134.9      .1       0
     160     .05       0     470      .1       0     480     .06       0
#XS Ineff= 2 , 0
                          441.26         2365.64
Permanent Ineff=
       F       F
Bank Sta=93.9,134.9
XS Rating Curve= 0 ,0
Exp/Cntr(USF)=0,0
Exp/Cntr=0.3,0.1

Type RM Length L Ch R = 1 ,19491   ,223.9,239.7,246.7
XS GIS Cut Line= 5
2229951.44579427 417948.511088852229981.08927986418012.032843671
2230136.36468053418174.3662171032230194.24005715418187.070568067
 2230422.9183745418397.398156252
#Sta/Elev= 30
       0  2386.1    37.2 2366.59    62.5 2356.15    77.2 2348.73    82.8  2347.4
   138.2 2347.22   154.7 2346.46   172.9  2347.5   184.5  2346.5   204.5 2347.57
   221.1 2346.54   248.8 2347.21   303.7 2344.73   331.4 2343.58   335.5 2343.61
   340.4 2345.16   347.8 2346.69   372.9 2345.75   389.2  2347.7   405.5 2346.83
   438.9 2348.42   478.6 2348.14   487.1  2348.9     493 2350.67   506.9 2350.89
   509.7  2352.1     521 2361.89   546.8 2380.16   625.8 2421.74   664.7 2443.34
#Mann= 6 ,-1,0
       0      .1       0   303.7    .045       0   340.4      .1       0
  413.99     .06       0  453.99     .07       0  553.99      .1       0
Bank Sta=303.7,340.4
XS Rating Curve= 0 ,0
Exp/Cntr(USF)=0,0
Exp/Cntr=0.3,0.1

Type RM Length L Ch R = 1 ,19252   ,201.4,216.3,222.6
XS GIS Cut Line= 4
2229846.41262096418080.8792575392229896.61564806418235.558854556
2230180.19490926418492.0013443472230347.08605341418559.843272863
#Sta/Elev= 30
       0 2385.43    52.4  2348.5    58.8 2345.32      62 2344.75    84.2 2343.56
   112.8 2343.72   122.3 2342.66   143.3 2343.81   199.8 2344.08   206.8 2344.66
   225.8 2343.14   248.5 2345.19   262.6 2345.44   319.2 2342.38   344.7 2341.65
     359 2343.15   367.4 2345.15     407 2344.64   463.2  2345.7   486.3 2347.85
   503.3 2348.45   507.2 2350.44   523.4 2362.25   557.3 2383.38   622.4 2418.44
   644.1 2428.43   665.8 2440.02   683.1 2448.16     709 2458.14   725.1 2462.75
#Mann= 6 ,-1,0
       0      .1       0   319.2    .045       0     359      .1       0
  442.62     .08       0  532.62     .06       0  614.96      .1       0
Bank Sta=319.2,359
XS Rating Curve= 0 ,0
Exp/Cntr(USF)=0,0
Exp/Cntr=0.3,0.1

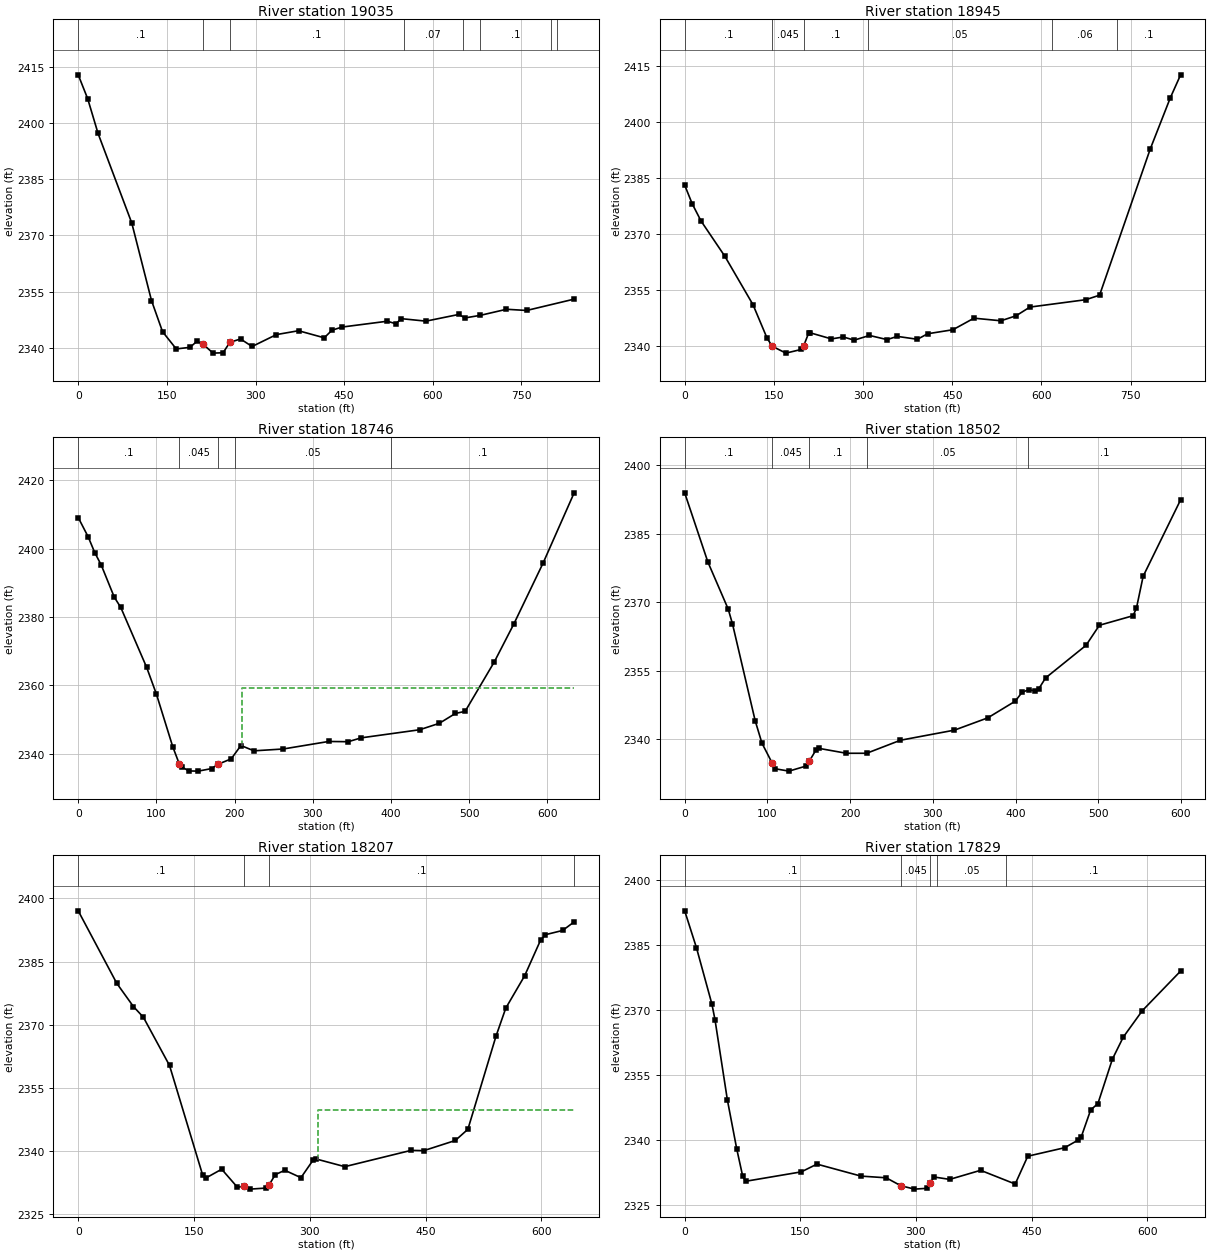
Type RM Length L Ch R = 1 ,19035   ,89.7,90.9,89.2
XS GIS Cut Line= 5
2229703.94457107418166.3600874692229755.50443675418285.761881658
2229810.28760813418343.6393233972229832.88724704418410.677053693
2230191.95417687418838.748978985
#Sta/Elev= 30
       0  2412.9    16.1 2406.49    33.6 2397.24    90.6 2373.35     124 2352.64
   142.7 2344.31   165.9 2339.71   189.2 2340.14   200.9 2341.75   211.4 2340.95
   228.2 2338.59   245.1 2338.69   256.7 2341.48   274.7 2342.37   294.2 2340.36
   335.4 2343.54   372.8 2344.57   416.3 2342.68   429.4 2344.71   446.4 2345.55
   523.1 2347.11   537.3 2346.44     547 2347.79   588.4 2347.13     644 2348.92
   654.4 2347.99   680.5 2348.68   724.7  2350.3   758.8 2349.98   839.2 2353.01
#Mann= 8 ,-1,0
       0      .1       0   211.4    .045       0   256.7      .1       0
   550.5     .07       0   650.5     .06       0   680.5      .1       0
   800.5     .12       0   810.5      .1       0
Bank Sta=211.4,256.7
XS Rating Curve= 0 ,0
Exp/Cntr(USF)=0,0
Exp/Cntr=0.3,0.1

Type RM Length L Ch R = 1 ,18945   ,194.8,198.5,198.6
XS GIS Cut Line= 3
 2229625.2748597418269.5041665282229711.20796916418334.330898221
2229958.45410864419017.272978618
#Sta/Elev= 30
       0 2383.01    12.7    2378    27.5  2373.4    67.5 2363.96   114.9 2350.96
   138.7 2341.94   147.32339.817   170.2 2337.98   195.8 2338.96     200  2339.9
   208.5 2343.36   210.6 2343.45   246.8 2341.79   266.8 2342.31   285.1 2341.46
   310.8 2342.72   340.4  2341.6   357.4 2342.47   391.4 2341.69   408.5 2343.17
   451.1 2344.25   486.5 2347.35   531.8 2346.65   557.3 2347.99   580.5 2350.32
   674.5  2352.3   697.7 2353.51   782.8 2392.65   816.8 2406.47     834 2412.58
#Mann= 6 ,-1,0
       0      .1       0   147.3    .045       0     200      .1       0
  307.64     .05       0  617.64     .06       0  727.64      .1       0
Bank Sta=147.3,200
XS Rating Curve= 0 ,0
Exp/Cntr(USF)=0,0
Exp/Cntr=0.3,0.1

Type RM Length L Ch R = 1 ,18746   ,241.8,244.3,245.9
XS GIS Cut Line= 2
2229515.22017566 418332.823299812229687.08639457418943.400656455
#Sta/Elev= 30
       0 2409.15    12.8 2403.47    21.1 2398.91    29.5 2395.22    46.1 2385.85
    54.4 2382.85    87.6 2365.26   100.1 2357.41   120.9 2342.08   129.2 2337.08
   133.3 2336.03   141.7 2334.98   153.5 2334.93   170.7 2335.68   178.4  2336.9
   195.7 2338.53   208.1 2342.43   224.8 2340.87   262.2 2341.41   320.3 2343.61
   345.3 2343.54   361.9 2344.67   436.7 2347.04   461.8 2348.92   482.4 2351.81
   494.9 2352.43   532.3 2366.95   557.2 2378.02   594.5 2395.79   634.3 2416.38
#Mann= 5 ,-1,0
       0      .1       0   129.2    .045       0   178.4      .1       0
     200     .05       0     400      .1       0
#XS Ineff= 2 , 0
                          209.45         2359.27
Permanent Ineff=
       F       F
Bank Sta=129.2,178.4
XS Rating Curve= 0 ,0
Exp/Cntr(USF)=0,0
Exp/Cntr=0.3,0.1

Type RM Length L Ch R = 1 ,18502   ,295.1,294.3,293.9
XS GIS Cut Line= 3
2229293.60320918418409.7108187952229373.50592499418797.163610543
 2229335.8159647418997.674199268
#Sta/Elev= 30
       0 2394.01      28 2378.88    52.6 2368.56    57.8 2365.31    85.2 2344.13
    93.4  2339.2   105.6  2334.9   109.7 2333.58   126.1 2333.07   146.5 2334.17
   150.6 2335.23   158.7 2337.69   162.8 2338.04   195.5 2336.98     220 2336.98
   260.8 2339.83   326.2 2342.05   366.5 2344.74   399.7 2348.39   407.8 2350.31
     416 2350.92   424.1 2350.59   428.2 2351.12   436.3 2353.47   485.2 2360.61
   501.4 2365.01   542.1  2367.1   546.2 2368.76   554.3 2375.74   599.6 2392.48
#Mann= 5 ,-1,0
       0      .1       0   105.6    .045       0   150.6      .1       0
     220     .05       0  415.61      .1       0
Bank Sta=105.6,150.6
XS Rating Curve= 0 ,0
Exp/Cntr(USF)=0,0
Exp/Cntr=0.3,0.1

Type RM Length L Ch R = 1 ,18207   ,377.9,378.4,378.4
XS GIS Cut Line= 3
2229075.00143952 418394.634834682229019.22029829418536.349085358
2229121.73699027419015.765380206
#Sta/Elev= 30
       0 2397.05      50 2379.81    71.5 2374.31    84.4 2371.77   118.3  2360.3
   161.3 2334.22   165.4 2333.55   185.9 2335.64   206.3 2331.35   214.72331.608
   222.7 2330.91   243.1 2331.16   247.2 2331.89   255.4 2334.36   267.7 2335.39
   288.6 2333.63   304.5 2337.85   308.6 2338.06   345.4 2336.25   431.3 2340.12
   447.7 2340.05   488.6 2342.47   504.9 2345.13   541.3 2367.24     554 2373.92
   578.4 2381.59     599 2390.05   605.4 2391.38   627.6 2392.38   642.6 2394.42
#Mann= 4 ,-1,0
       0      .1       0   214.7    .045       0   247.2      .1       0
   642.3     .06       0
#XS Ineff= 2 , 0
                          311.24         2349.66
Permanent Ineff=
       F       F
Bank Sta=214.7,247.2
XS Rating Curve= 0 ,0
Exp/Cntr(USF)=0,0
Exp/Cntr=0.3,0.1

Type RM Length L Ch R = 1 ,17829   ,472.5,477.3,469.8
XS GIS Cut Line= 4
2228635.38108959418397.9189275982228638.10408054418555.266991858
2228712.22725254418917.3591154292228773.09920543419016.599714934
#Sta/Elev= 30
       0 2392.96    15.3 2384.42    35.3 2371.42    39.3 2367.83    55.4 2349.25
    67.6 2337.88    75.3  2331.6    79.3 2330.46   151.3 2332.63   171.6 2334.42
   228.7 2331.65   261.4 2331.26   280.4 2329.43   298.1 2328.64   314.5 2328.83
   318.6 2329.96   323.4 2331.45   343.8 2330.89   383.9 2332.99   428.8 2329.82
   445.1 2336.25   492.9 2338.21   510.5 2339.98   514.5 2340.72   526.7 2346.94
   536.1 2348.41   554.9 2358.69     569 2363.77   593.7 2369.88   643.4 2379.04
#Mann= 5 ,-1,0
       0      .1       0   280.4    .045       0   318.6      .1       0
  327.37     .05       0  417.37      .1       0
Bank Sta=280.4,318.6
XS Rating Curve= 0 ,0
Exp/Cntr=0.3,0.1

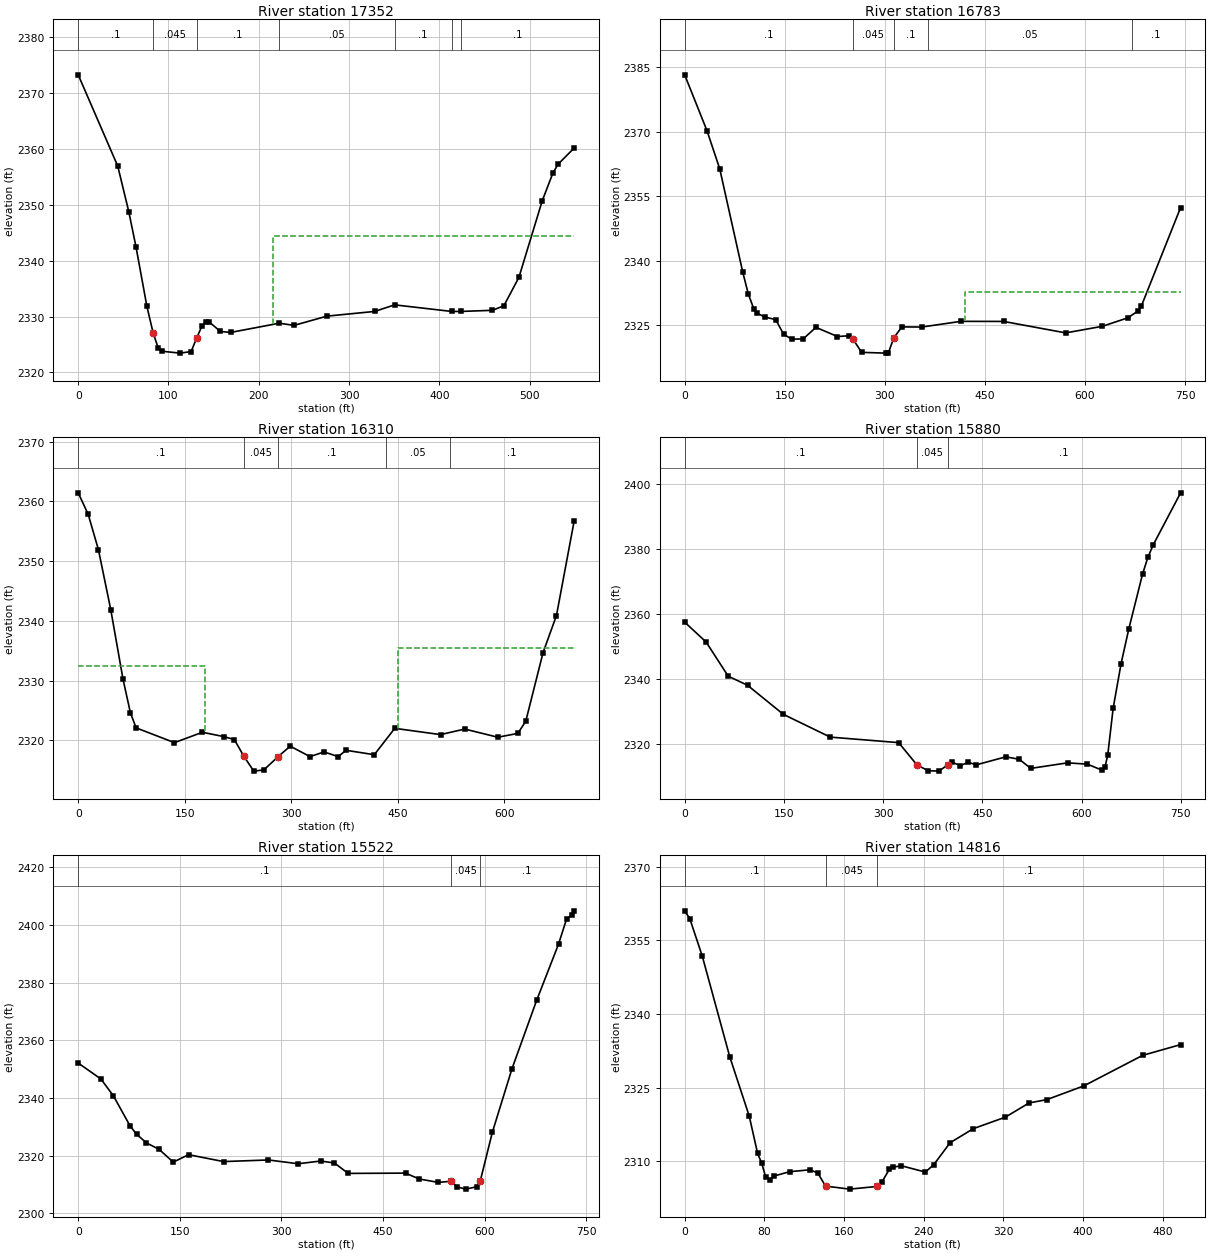
Type RM Length L Ch R = 1 ,17352   ,566.4,568.5,571.5
XS GIS Cut Line= 3
2228234.68101719418502.1142036142228305.53497285418888.838221714
 2228211.2455448419013.390438011
#Sta/Elev= 30
       0 2373.31    43.8 2356.95      56  2348.8    64.1 2342.41    76.1 2331.81
      83 2327.06    88.5 2324.43    92.6 2323.78   112.9 2323.44   125.1 2323.72
   131.1  2326.1   137.3 2328.38   141.5 2328.94   145.4 2328.97   157.6 2327.32
   168.9 2327.15   222.7  2328.8     239 2328.41   275.6 2330.07   328.4 2330.91
   350.5 2332.09   413.7 2330.91   423.7 2330.91   458.8 2331.11   471.5 2331.92
   488.2 2337.01     514 2350.72   525.7 2355.64   531.4 2357.26   549.4 2360.19
#Mann= 7 ,-1,0
       0      .1       0      83    .045       0   131.1      .1       0
   222.7     .05       0   350.5      .1       0   413.7     .05       0
   423.7      .1       0
#XS Ineff= 2 , 0
       0                     216       0 2344.37
Permanent Ineff=
       F       F
Bank Sta=83,131.1
XS Rating Curve= 0 ,0
Exp/Cntr=0.3,0.1

Type RM Length L Ch R = 1 ,16783   ,486.9,472.8,445.6
XS GIS Cut Line= 4
 2227715.3086558418456.6561887052227685.15668757418577.264061623
2227740.43529599 419069.746209372227814.14010722419168.577660788
#Sta/Elev= 30
       0 2383.24    33.5  2370.2    52.5 2361.37    87.1 2337.25    95.4 2332.18
   103.6 2328.75   107.7 2327.81   120.1 2326.84   136.3 2326.25   148.4 2322.82
   160.5 2321.69   177.6 2321.75   196.7 2324.44   228.9 2322.31   246.4 2322.48
   252.3  2321.7   265.1 2318.62   301.3 2318.44   305.4 2318.57   313.4    2322
   325.5 2324.55     355 2324.51     414 2325.84     478 2325.82     571 2323.15
   626.1 2324.69   664.1 2326.66   679.7 2328.28   684.1  2329.3   743.2 2352.34
#Mann= 5 ,-1,0
       0      .1       0   252.3    .045       0   313.4      .1       0
  364.32     .05       0  669.89      .1       0
#XS Ineff= 2 , 0
                          420.48         2332.61
Permanent Ineff=
       F       F
Bank Sta=252.3,313.4
XS Rating Curve= 0 ,0
Exp/Cntr(USF)=0,0
Exp/Cntr=0.3,0.1

Type RM Length L Ch R = 1 ,16310   ,416.7,430.8,450.7
XS GIS Cut Line= 3
 2227144.1479457418714.8286597252227183.41571493418810.078634391
2227601.66493756      419233.617
#Sta/Elev= 30
       0 2361.45    14.1 2357.83    28.5  2351.9    45.8 2341.89      63 2330.28
    73.5 2324.59    81.5 2322.07   135.5 2319.59   174.8 2321.33   204.8 2320.61
   219.8 2320.11     233 2317.36   247.2 2314.82   261.3 2315.02   281.7 2317.27
   298.5    2319   326.4 2317.25   346.2 2318.04     366 2317.25   377.2 2318.31
   416.9 2317.57   445.7 2321.99   510.2 2320.94   544.2 2321.87   590.8  2320.5
     619 2321.14   630.2 2323.19   654.5 2334.68   673.4 2340.89   698.3 2356.72
#Mann= 5 ,-1,0
       0      .1       0     233    .045       0   281.7      .1       0
  433.03     .05       0  523.03      .1       0
#XS Ineff= 2 , 0
          177.87 2332.42  450.38         2335.37
Permanent Ineff=
       F       F
Bank Sta=233,281.7
XS Rating Curve= 0 ,0
Exp/Cntr=0.3,0.1

Type RM Length L Ch R = 1 ,15880   ,331,357.6,350.1
XS GIS Cut Line= 3
2226979.93565287418666.0448569652226896.18018557418950.813445798
2226968.20988745419398.067641201
#Sta/Elev= 30
       0 2357.51    32.5 2351.39    65.8 2340.92      95 2338.14   149.2 2329.21
   220.1 2322.22   323.5 2320.53   351.2 2313.67   368.1 2311.92   384.3 2311.78
   397.4 2313.65   404.6 2314.48   416.7 2313.49   428.9 2314.46     441 2313.72
   485.6 2316.17   505.9 2315.41   523.2 2312.62   578.8 2314.32   608.8 2313.92
   631.5 2312.03   635.5 2313.03   639.6  2316.7   647.8 2331.07   659.8 2344.79
   671.5 2355.47   692.2 2372.22   700.3 2377.42   708.4 2381.25   749.8 2397.21
#Mann= 3 ,-1,0
       0      .1       0   351.2    .045       0   397.4      .1       0
Bank Sta=351.2,397.4
XS Rating Curve= 0 ,0
Exp/Cntr(USF)=0,0
Exp/Cntr=0.3,0.1

Type RM Length L Ch R = 1 ,15522   ,698.2,705.7,709.5
XS GIS Cut Line= 3
2226504.20459858418746.4501055772226720.29370423419058.020443947
2226763.84654723419408.118297278
#Sta/Elev= 30
       0 2352.14    33.6 2346.59      52 2340.74    76.3 2330.45    86.1 2327.46
   100.7 2324.46   119.3 2322.23   140.3 2317.79   162.9 2320.37   214.6 2317.98
   280.8 2318.54   324.6 2317.23   357.9 2318.17   378.1  2317.5   398.5 2313.88
   483.1 2313.98   503.3 2311.95   531.5 2310.76   549.82311.152   559.7 2309.18
   571.8 2308.43   587.9 2309.23   593.4 2311.25   611.3 2328.17   640.3  2350.2
   676.6 2373.85   708.9 2393.33   720.9 2402.15     729 2403.43     732 2404.91
#Mann= 3 ,-1,0
       0      .1       0   549.8    .045       0   593.4      .1       0
Bank Sta=549.8,593.4
XS Rating Curve= 0 ,0
Exp/Cntr(USF)=0,0
Exp/Cntr=0.3,0.1

Type RM Length L Ch R = 1 ,14816   ,489.1,467.1,447.1
XS GIS Cut Line= 3
2226060.85321267419032.0709230722226037.33290498419391.366330313
2226155.52280543419462.072122176
#Sta/Elev= 30
       0 2361.04     5.1 2359.46    17.6 2351.85    45.2 2331.33    64.8 2319.21
    73.2  2311.6    77.3 2309.64    81.3 2306.79    85.3 2306.22    89.3 2306.98
   105.3 2307.88   125.4 2308.26   133.4 2307.66   141.4 2304.95   165.5 2304.33
   193.5 2304.88   197.8 2305.74   205.5 2308.38   209.6 2308.83   217.6 2309.08
   241.6 2307.81     250 2309.31   266.4 2313.78   289.7 2316.65   321.8 2318.99
   345.8  2321.9   363.4 2322.56   400.7 2325.37   459.7 2331.59   497.8 2333.78
#Mann= 3 ,-1,0
       0      .1       0   141.4    .045       0   193.5      .1       0
Bank Sta=141.4,193.5
XS Rating Curve= 0 ,0
Exp/Cntr=0.3,0.1