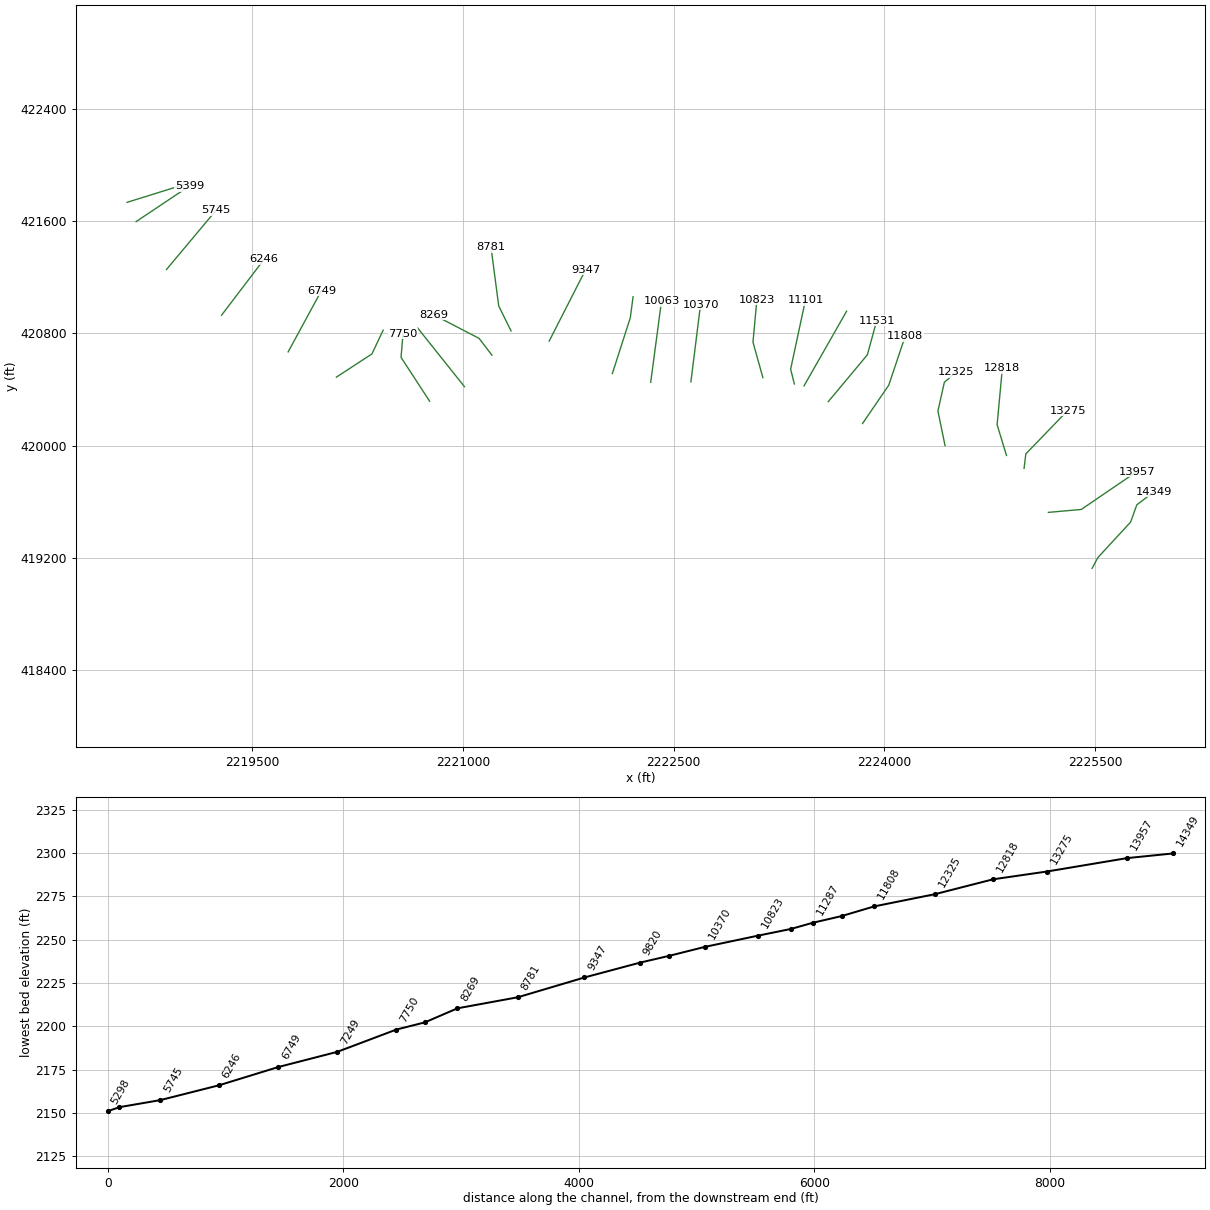
HEC-RAS study BEAVERCK.prj: BEAVERCK

--- BEAVERCK.g01 (geometry) --- (continued)

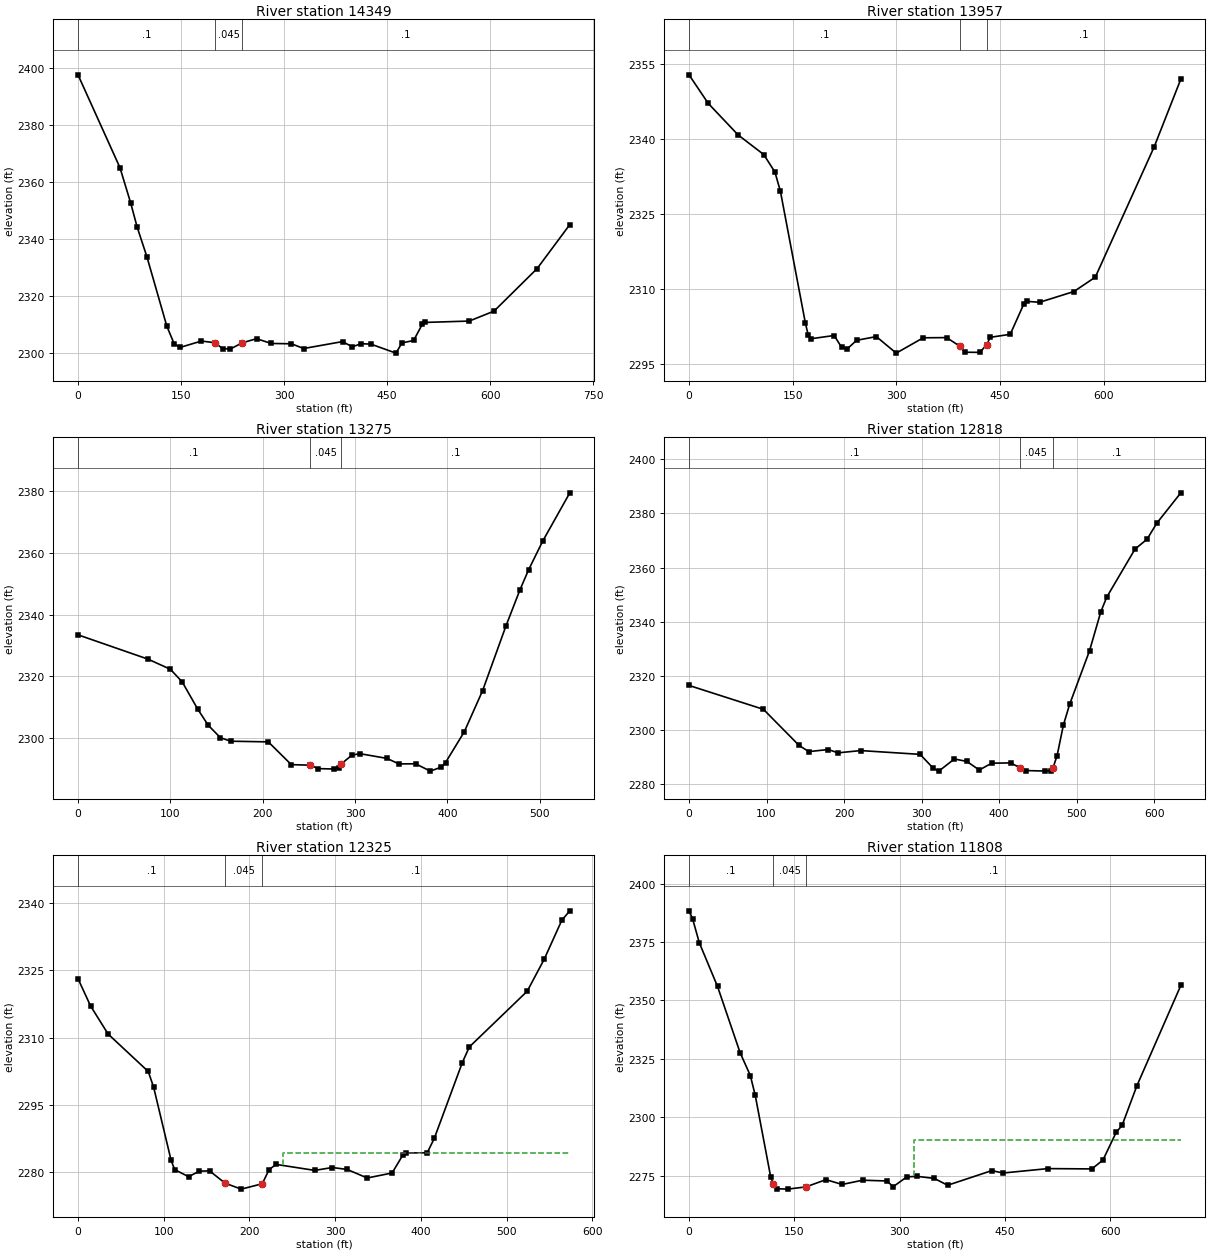
Type RM Length L Ch R = 1 ,14349   ,398.9,392.3,388
XS GIS Cut Line= 5
2225479.68991402419125.271072395  2225519.853181419201.470633486
2225753.75561154419455.0213589682225797.30845454419577.304341232
 2225920.4695996419671.586560274
#Sta/Elev= 30
       0 2397.69    61.1 2365.02    76.8 2352.52    86.1 2344.13   100.3  2333.7
   129.3 2309.29   139.9 2303.13   148.4 2301.79   179.6 2304.05   199.4 2303.46
   210.5  2301.4   221.8 2301.25     239 2303.41   259.9 2304.88   281.3  2303.2
   310.8 2303.08   328.5 2301.42   385.1 2303.86   399.3 2302.02   412.3 2303.12
   426.5 2302.96   462.9  2299.8   471.6 2303.38   488.6 2304.25   501.3 2309.99
   505.6  2310.6   569.6 2311.08   605.7 2314.58   668.4 2329.54     716 2345.01
#Mann= 3 ,-1,0
       0      .1       0   199.4    .045       0     239      .1       0
Bank Sta=199.4,239
XS Rating Curve= 0 ,0
Exp/Cntr=0.3,0.1

Type RM Length L Ch R = 1 ,13957   ,661.9,682.4,677.8
XS GIS Cut Line= 3
2225168.47939819419523.9578325772225402.14284163419544.701877831
2225796.01165611419813.269932132
#Sta/Elev= 30
       0 2352.83    27.8 2347.11    70.9 2340.81   108.1 2336.86   124.2 2333.38
   132.2  2329.5   168.4 2303.05   172.4 2300.73   176.4 2299.98   209.9 2300.63
   220.6 2298.28   228.6 2297.93   242.5 2299.67   270.9 2300.41   299.7  2297.1
   338.7 2300.17   372.6 2300.21   391.6 2298.49   398.7 2297.28   420.6 2297.25
   430.7 2298.81   435.5 2300.26   464.6 2300.87   483.9 2306.84   488.8 2307.47
     507 2307.28   556.6 2309.43   587.6 2312.31   672.8 2338.42   711.3 2351.97
#Mann= 3 ,-1,0
       0      .1       0   391.6    .045       0   430.7      .1       0
Bank Sta=391.6,430.7
XS Rating Curve= 0 ,0
Exp/Cntr=0.3,0.1

Type RM Length L Ch R = 1 ,13275   ,427.1,456.3,464.6
XS GIS Cut Line= 3
2224994.99193665419837.855802712 2225007.7589447419940.694150638
2225305.64418824420249.371456111
#Sta/Elev= 30
       0 2333.47    75.9 2325.59   100.1 2322.31   112.8 2318.24   129.7 2309.39
     141  2304.2   154.3 2300.14   165.4 2299.03   206.1 2298.81     231 2291.44
   251.4 2291.27   259.9 2290.15     277 2290.03   282.2 2290.42   285.3 2291.73
   296.6  2294.5   305.1    2295   334.6 2293.46   347.5 2291.67   365.6 2291.72
   381.5 2289.34   393.4 2290.64     398 2292.11   418.3 2302.07   438.1 2315.37
   463.5  2336.4   478.6 2348.04   487.9 2354.49   503.1 2363.74   532.6 2379.45
#Mann= 3 ,-1,0
       0      .1       0   251.4    .045       0   285.3      .1       0
Bank Sta=251.4,285.3
XS Rating Curve= 0 ,0
Exp/Cntr=0.3,0.1

Type RM Length L Ch R = 1 ,12818   ,475.2,493.1,490.1
XS GIS Cut Line= 3
 2224869.9364009419929.3436063322224803.14100905420148.784822629
2224840.65632127420552.051233489
#Sta/Elev= 30
       0 2316.49      96 2307.67     142 2294.33   154.5 2292.06   179.6 2292.82
   192.2  2291.6   221.4 2292.44   298.1 2291.04   315.2 2285.87   322.2 2284.85
   342.3 2289.33   358.3 2288.44   374.4 2285.27   390.5 2287.79   414.7 2287.88
   426.6 2286.17   434.7 2285.06   458.6 2284.88   466.8 2284.99   469.6 2286.13
   474.8 2290.57   482.9 2301.84   490.9 2309.46   516.6 2329.27   531.1  2343.6
   538.7 2349.03   575.3 2366.84   590.9  2370.5   603.4 2376.41   634.4 2387.62
#Mann= 3 ,-1,0
       0      .1       0   426.6    .045       0   469.6      .1       0
Bank Sta=426.6,469.6
XS Rating Curve= 0 ,0
Exp/Cntr=0.3,0.1

Type RM Length L Ch R = 1 ,12325   ,532,517.1,488.8
XS GIS Cut Line= 4
2224432.70727692419998.842355651 2224381.8410571420245.672970317
2224427.75948996420451.0880824052224512.23793549420523.174891689
#Sta/Elev= 30
       0 2323.11    14.6 2317.06    35.1 2310.79    81.9 2302.46    88.2 2298.97
   108.6 2282.67   112.7 2280.63     129 2279.04   141.4 2280.28   153.5 2280.34
   171.42277.618   190.3 2276.28   214.9 2277.47   222.9 2280.64   231.1 2281.78
   276.1 2280.45   296.6 2281.09   313.9 2280.66   337.3 2278.76   366.3 2279.87
   378.6 2283.78   382.7 2284.33   407.3 2284.37   415.5 2287.56   448.2 2304.43
   456.4 2307.92   523.9 2320.32   543.7 2327.43   564.3 2336.13   573.6 2338.21
#Mann= 3 ,-1,0
       0      .1       0   171.4    .045       0   214.9      .1       0
#XS Ineff= 2 , 0
                          238.71         2284.31
Permanent Ineff=
       F       F
Bank Sta=171.4,214.9
XS Rating Curve= 0 ,0
Exp/Cntr=0.3,0.1

Type RM Length L Ch R = 1 ,11808   ,278.7,277.1,273.8
XS GIS Cut Line= 3
2223845.24331843420157.0788353812224031.74320377420429.934998386
 2224149.3764094420780.417586235
#Sta/Elev= 30
       0 2388.36       5 2385.05    14.7 2374.65    40.6 2355.97    72.8 2327.56
    87.3 2317.85    94.3 2309.32   116.4 2274.24   119.92271.565   125.9 2269.36
   140.3  2269.2   166.32270.141     195 2273.26     218  2271.2   247.2 2273.02
   281.6 2272.69   290.8 2270.26     310 2274.43   324.5 2274.68   349.2 2273.79
   368.2 2270.86     431 2277.12   447.1  2276.1   511.1 2277.99   573.5 2277.85
   589.3 2281.63   608.2 2293.54   616.6 2296.51   637.7  2313.5   700.2 2356.42
#Mann= 3 ,-1,0
       0      .1       0   119.9    .045       0   166.3      .1       0
#XS Ineff= 2 , 0
                          320.91         2290.25
Permanent Ineff=
       F       F
Bank Sta=119.9,166.3
XS Rating Curve= 0 ,0
Exp/Cntr=0.3,0.1

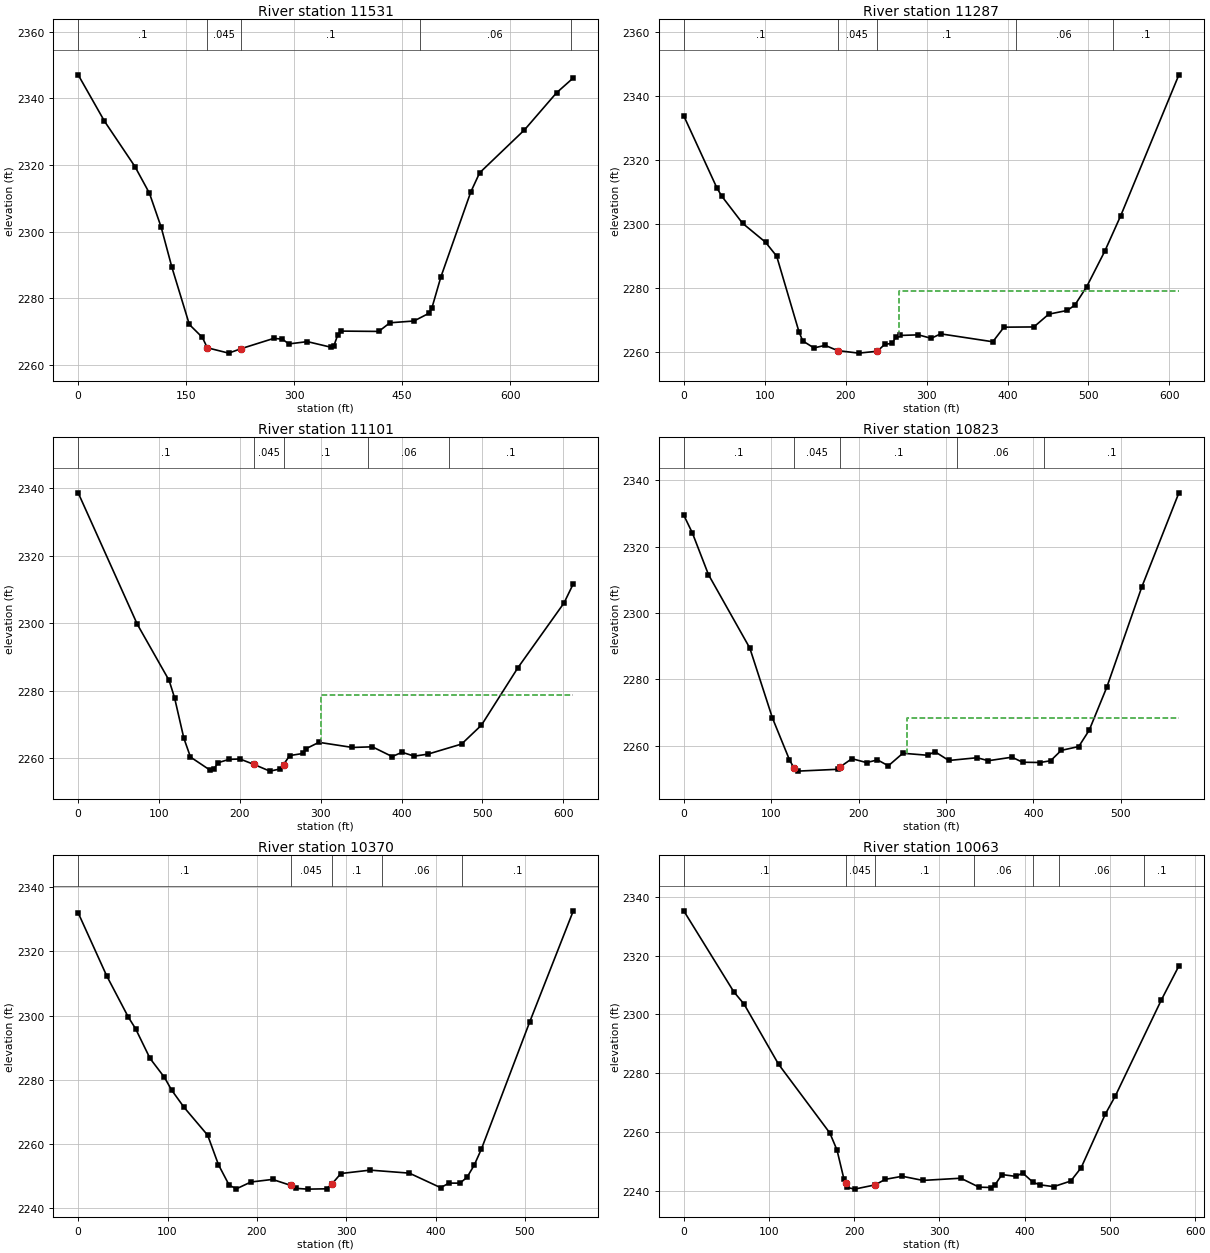
Type RM Length L Ch R = 1 ,11531   ,238.6,243.4,248.6
XS GIS Cut Line= 3
2223601.24010183420312.6773441612223879.30825328 420646.02410403
2223946.31262712420890.590068558
#Sta/Elev= 30
       0 2347.09    36.5 2333.19    78.8 2319.59      99 2311.56   115.3 2301.36
   130.2 2289.34   154.4  2272.2   172.5 2268.33   179.32265.217     209 2263.61
   226.72264.976   271.5 2268.02   283.6 2267.83   292.4 2266.37   318.4 2267.06
   351.8 2265.34   354.9 2265.66   360.5 2269.05   365.3 2270.22   417.4 2270.12
     433 2272.71   466.4 2273.25   487.1 2275.55   491.3 2277.16   503.7 2286.41
   545.2  2311.9   557.6  2317.7   619.9 2330.58   664.4  2341.7   687.7 2346.17
#Mann= 5 ,-1,0
       0      .1       0   179.3    .045       0   226.7      .1       0
   474.1     .06       0   684.1      .1       0
Bank Sta=179.3,226.7
XS Rating Curve= 0 ,0
Exp/Cntr(USF)=0,0
Exp/Cntr=0.3,0.1

Type RM Length L Ch R = 1 ,11287   ,177.8,186.7,194.4
XS GIS Cut Line= 2
2223428.81123167420425.4496325742223731.73314299  420956.8850181
#Sta/Elev= 30
       0  2333.9    41.1 2311.28    47.2 2308.71    72.6 2300.34     101 2294.41
   114.8 2290.04   142.4 2266.38     147 2263.58   160.8 2261.38   174.6 2262.19
     190 2260.56   216.1 2259.76   239.1 2260.35   248.3  2262.5   257.4 2262.81
   262.1  2264.8   266.7 2265.28   289.8 2265.47   305.7 2264.39   317.4 2265.78
   381.8 2263.31   395.6 2267.87   432.5 2267.94   450.9 2271.93   473.9  2273.1
   483.2 2274.78   497.9 2280.56     520 2291.53   539.9 2302.73   611.7  2346.7
#Mann= 5 ,-1,0
       0      .1       0     190    .045       0   239.1      .1       0
     410     .06       0     530      .1       0
#XS Ineff= 2 , 0
                          265.65          2279.1
Permanent Ineff=
       F       F
Bank Sta=190,239.1
XS Rating Curve= 0 ,0
Exp/Cntr=0.3,0.1

Type RM Length L Ch R = 1 ,11101   ,262.4,278,286.2
XS GIS Cut Line= 3
2223360.02435599420438.3105451162223333.22260645420543.842433919
2223438.75449526421036.324581667
#Sta/Elev= 30
       0  2338.7    73.1 2299.74   112.5 2283.07   119.2 2277.97   130.7 2265.96
   138.9 2260.36   163.4 2256.43   167.5 2256.68   173.1 2258.68   186.6 2259.66
   200.1 2259.78   217.2 2258.19   237.1 2256.18   249.3 2256.79     254  2258.1
   261.6 2260.79     278 2261.41   282.1 2262.85   297.8 2264.72   339.3  2263.2
   363.9 2263.39   388.4  2260.5   400.7 2261.77   415.7 2260.62   432.5 2261.21
   474.3 2264.21   498.9 2269.82   544.1 2286.89     601 2306.04   612.5 2311.74
#Mann= 5 ,-1,0
       0      .1       0   217.2    .045       0     254      .1       0
  358.88     .06       0  458.88      .1       0
#XS Ineff= 2 , 0
                           299.9         2278.61
Permanent Ineff=
       F       F
Bank Sta=217.2,254
XS Rating Curve= 0 ,0
Exp/Cntr(USF)=0,0
Exp/Cntr=0.3,0.1

Type RM Length L Ch R = 1 ,10823   ,466.2,452.5,441.1
XS GIS Cut Line= 3
2223135.77989321420483.6866144742223065.20511108420736.480008718
 2223093.1715607421039.288201219
#Sta/Elev= 30
       0 2329.51     9.9 2324.11    28.3 2311.56    75.6 2289.42   101.5 2268.33
     121 2255.72   126.4 2253.15   130.3 2252.33     176 2252.88   179.32253.669
   192.4 2256.08   209.2  2254.9   221.7 2255.72   234.1 2253.93   250.7 2257.72
   279.2 2257.11   287.3 2258.21   303.3 2255.54   335.7 2256.37   348.5 2255.47
   375.6 2256.53   387.7 2255.01   407.8 2254.93   419.8 2255.46   431.9 2258.58
     452 2259.74     464 2264.69   484.1 2277.63   524.3 2307.96   566.6 2336.24
#Mann= 5 ,-1,0
       0      .1       0   126.4    .045       0   179.3      .1       0
  312.46     .06       0  412.46      .1       0
#XS Ineff= 2 , 0
                          255.44         2268.35
Permanent Ineff=
       F       F
Bank Sta=126.4,179.3
XS Rating Curve= 0 ,0
Exp/Cntr=0.3,0.1

Type RM Length L Ch R = 1 ,10370   ,308,307.4,307.2
XS GIS Cut Line= 2
 2222623.3115267420453.3968470552222691.88738371421003.276866972
#Sta/Elev= 30
       0 2332.05      32 2312.35    56.2 2299.47    64.3 2295.86    80.4 2286.63
    96.5 2280.72   104.6 2276.73   118.5 2271.35   144.9 2262.66     157 2253.45
     169 2247.05   177.1 2245.93   193.3 2248.05   217.5 2248.86   238.2 2246.97
   244.3 2246.06   256.7 2245.83   277.9 2245.93   283.7 2247.35     294  2250.7
   326.7 2251.76   370.6 2250.82   405.6 2246.29     415 2247.71   427.2  2247.7
   435.1  2249.5   443.2 2253.31   451.3 2258.37   505.3 2298.01   554.1 2332.68
#Mann= 5 ,-1,0
       0      .1       0   238.2    .045       0   283.7      .1       0
     340     .06       0     430      .1       0
Bank Sta=238.2,283.7
XS Rating Curve= 0 ,0
Exp/Cntr=0.3,0.1

Type RM Length L Ch R = 1 ,10063   ,248.3,243.2,238.4
XS GIS Cut Line= 2
 2222337.3292185420450.9751897852222413.72953847421026.916063442
#Sta/Elev= 30
       0  2335.2    58.7 2307.68    70.8 2303.47   111.2 2283.06   171.4 2259.67
   179.8  2253.9   187.8  2244.2     190 2242.56   191.9 2241.16   200.4 2240.59
   224.5 2242.03   236.5 2243.92   256.4 2244.96   280.6 2243.55   325.1  2244.3
   346.5 2241.26   360.7 2241.14   365.4 2242.12   373.4 2245.54   389.6 2244.92
   397.7 2246.08   409.8 2242.92   417.8 2242.06     434 2241.43   454.1 2243.34
   466.3 2247.86   494.5    2266   506.6 2272.37   560.2 2304.78     581 2316.47
#Mann= 7 ,-1,0
       0      .1       0     190    .045       0   224.5      .1       0
     340     .06       0     410      .1       0     440     .06       0
     540      .1       0
Bank Sta=190,224.5
XS Rating Curve= 0 ,0
Exp/Cntr(USF)=0,0
Exp/Cntr=0.3,0.1

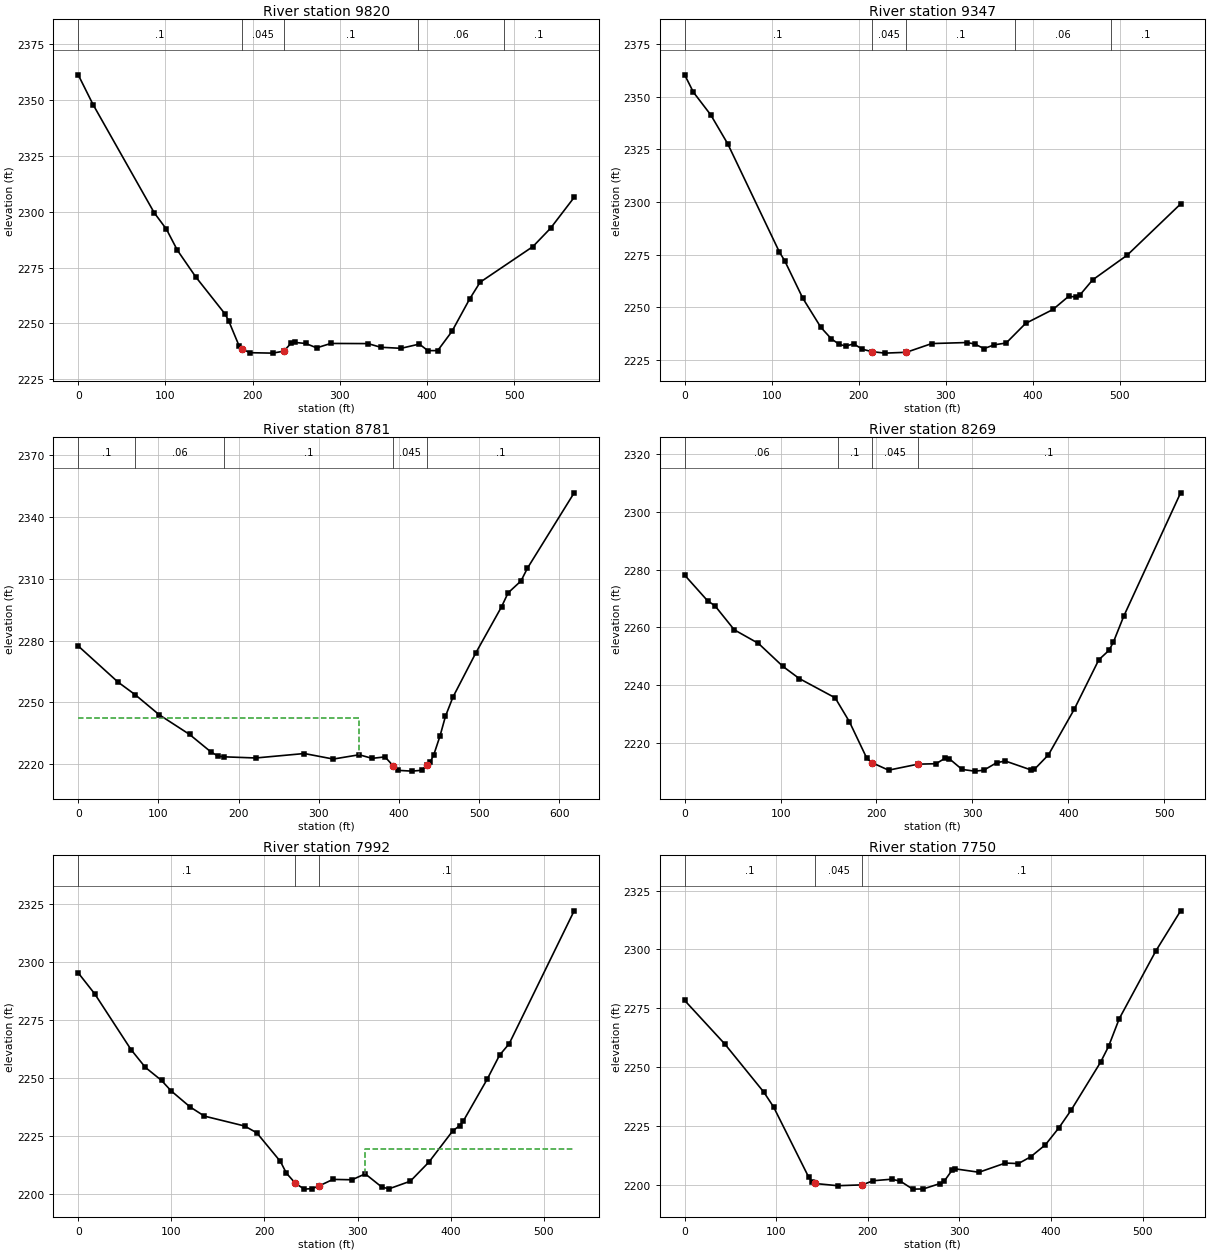
Type RM Length L Ch R = 1 ,9820    ,478.4,472.5,468.8
XS GIS Cut Line= 3
2222064.25357146420512.9650901112222192.09732905420910.754603435
2222211.74694498421060.053958554
#Sta/Elev= 30
       0 2361.16      17 2347.88    87.1  2299.5   101.1 2292.14   113.7 2282.71
   134.7 2270.82   168.3 2254.23   172.5 2251.14   184.5 2239.87   187.7 2238.47
   197.2 2236.93   222.7 2236.74   235.7 2237.61   243.9 2241.19   248.1 2241.53
   260.7 2241.06   273.3  2239.1   289.5 2241.07   332.1    2241   346.7 2239.36
     370 2238.89     391 2240.79   400.7 2237.85     412 2237.87   428.3 2246.44
   448.5 2260.86   460.6 2268.43   521.1 2284.37   541.3 2292.55   568.4 2306.37
#Mann= 5 ,-1,0
       0      .1       0   187.7    .045       0   235.7      .1       0
     390     .06       0  487.83      .1       0
Bank Sta=187.7,235.7
XS Rating Curve= 0 ,0
Exp/Cntr=0.3,0.1

Type RM Length L Ch R = 1 ,9347    ,547.3,565.9,577.5
XS GIS Cut Line= 2
2221614.52503569420744.2589401662221873.47695576421251.838086981
#Sta/Elev= 30
       0  2360.5      10 2352.25      30 2341.43    49.5 2327.66   108.8 2276.26
   114.9  2272.1   135.7 2254.28   156.5  2240.4   168.4    2235   177.3 2232.39
   185.1  2231.5   194.1 2232.58   204.1 2230.03   214.9 2228.87     230 2228.16
   254.7 2228.56   283.9 2232.71   324.3  2233.2   333.3 2232.49   343.9 2230.31
   355.8 2232.13   369.3 2232.95   391.7 2242.29   423.1 2248.91   441.1 2255.16
   450.1 2254.87   453.9 2255.71   468.7 2262.98   508.5 2274.77   569.8  2299.1
#Mann= 5 ,-1,0
       0      .1       0   214.9    .045       0   254.7      .1       0
     380     .06       0     490      .1       0
Bank Sta=214.9,254.7
XS Rating Curve= 0 ,0
Exp/Cntr=0.3,0.1

Type RM Length L Ch R = 1 ,8781    ,479.3,512.6,528.2
XS GIS Cut Line= 3
2221343.02084163420816.6886948162221255.24833656420994.495670606
2221200.52727326421410.946997546
#Sta/Elev= 30
       0 2277.38    49.6 2259.89    71.2 2253.71     101 2244.04   138.8 2234.52
   165.6 2225.99   174.5 2223.99   181.7 2223.67   221.3  2223.1   281.9 2225.26
     318 2222.58   350.3 2224.66   366.4 2222.92   382.5 2223.63   392.9 2219.18
   398.7  2217.1   416.1 2216.73   428.1 2217.13   434.7 2219.48   438.8 2221.19
   443.1 2224.43   451.1 2233.82   457.9 2243.36   467.2 2252.61   495.8 2274.09
   527.8 2296.38   535.9  2303.1     552 2308.88   560.1 2315.11   618.3  2351.6
#Mann= 5 ,-1,0
       0      .1       0    71.2     .06       0   181.7      .1       0
   392.9    .045       0   434.7      .1       0
#XS Ineff= 2 , 0
       0   349.6 2242.51               0
Permanent Ineff=
       F       F
Bank Sta=392.9,434.7
XS Rating Curve= 0 ,0
Exp/Cntr=0.3,0.1

Type RM Length L Ch R = 1 ,8269    ,286.9,277.2,263.5
XS GIS Cut Line= 3
2221206.58488231 420644.041371732221115.49957733420763.539279153
2220789.84126343420932.480705821
#Sta/Elev= 30
       0 2278.05    23.8 2269.23    31.6 2267.46    51.7 2259.17    76.9 2254.47
   102.4 2246.53   119.5 2242.33   156.9 2235.67   171.7 2227.45     190 2214.73
   195.12213.301   212.6 2210.68   243.1 2212.75   262.1 2212.91   271.2 2214.75
   275.7 2214.69   289.2 2210.93   302.3 2210.35   311.7 2210.64   325.2 2213.24
   334.2 2213.86   361.3 2210.74   364.6 2210.95   379.3 2215.99   406.1 2231.66
   431.8 2248.82   442.4 2252.07   446.9 2254.84   457.8 2263.87   517.1 2306.49
#Mann= 4 ,-1,0
       0     .06       0  160.25      .1       0   195.1    .045       0
   243.1      .1       0
Bank Sta=195.1,243.1
XS Rating Curve= 0 ,0
Exp/Cntr=0.3,0.1

Type RM Length L Ch R = 1 ,7992    ,247,241.9,240
XS GIS Cut Line= 2
2221011.54273868420419.2308645342220679.50988654 420835.75953209
#Sta/Elev= 30
       0 2295.37    17.8 2286.29    56.7 2262.33    72.1 2254.67    89.5 2249.02
    99.7 2244.58   120.1 2237.64   135.5 2233.67   178.7 2229.41   191.8 2226.47
   217.2 2214.12   223.6 2209.11  233.28 2204.72   242.8 2202.22   251.4 2202.45
   259.1 2203.67   273.6 2206.41   294.1 2206.25   308.3  2208.8   326.3 2203.04
     334 2202.38   356.7 2205.63   376.7 2213.87   402.3 2227.31   409.7 2229.53
   413.7  2231.6   439.3 2249.57   452.6 2259.93   462.9 2264.84   532.7 2322.09
#Mann= 3 ,0,0
       0      .1       0  233.28    .045       0   259.1      .1       0
#XS Ineff= 2 , 0
                          308.43          2219.7
Permanent Ineff=
       F       F
Bank Sta=233.28,259.1
XS Rating Curve= 0 ,0
Exp/Cntr(USF)=0,0
Exp/Cntr=0.3,0.1

Type RM Length L Ch R = 1 ,7750    ,554.7,500.6,461.2
XS GIS Cut Line= 3
  2220763.293581420315.869114928 2220559.8760362420628.373597282
2220574.22864253420796.243323083
#Sta/Elev= 30
       0 2278.32    43.7 2259.84    86.4 2239.32      97 2233.06   135.2  2203.3
   139.1 2201.17     142 2200.48     167 2199.53     194 2199.88   205.6 2201.64
   225.8 2202.28   235.4 2201.47   248.9 2198.07   260.5 2198.15   278.4  2200.4
   283.2 2201.37   292.3 2206.35   295.2  2206.7   321.3 2205.25     350 2209.16
   364.3 2208.94   377.7 2211.81   393.8 2216.93   408.6 2224.18   421.9 2231.69
     454 2252.04   462.7 2258.74   474.4 2270.55   514.4 2299.41   541.4 2316.44
#Mann= 3 ,-1,0
       0      .1       0     142    .045       0     194      .1       0
Bank Sta=142,194
XS Rating Curve= 0 ,0
Exp/Cntr=0.3,0.1

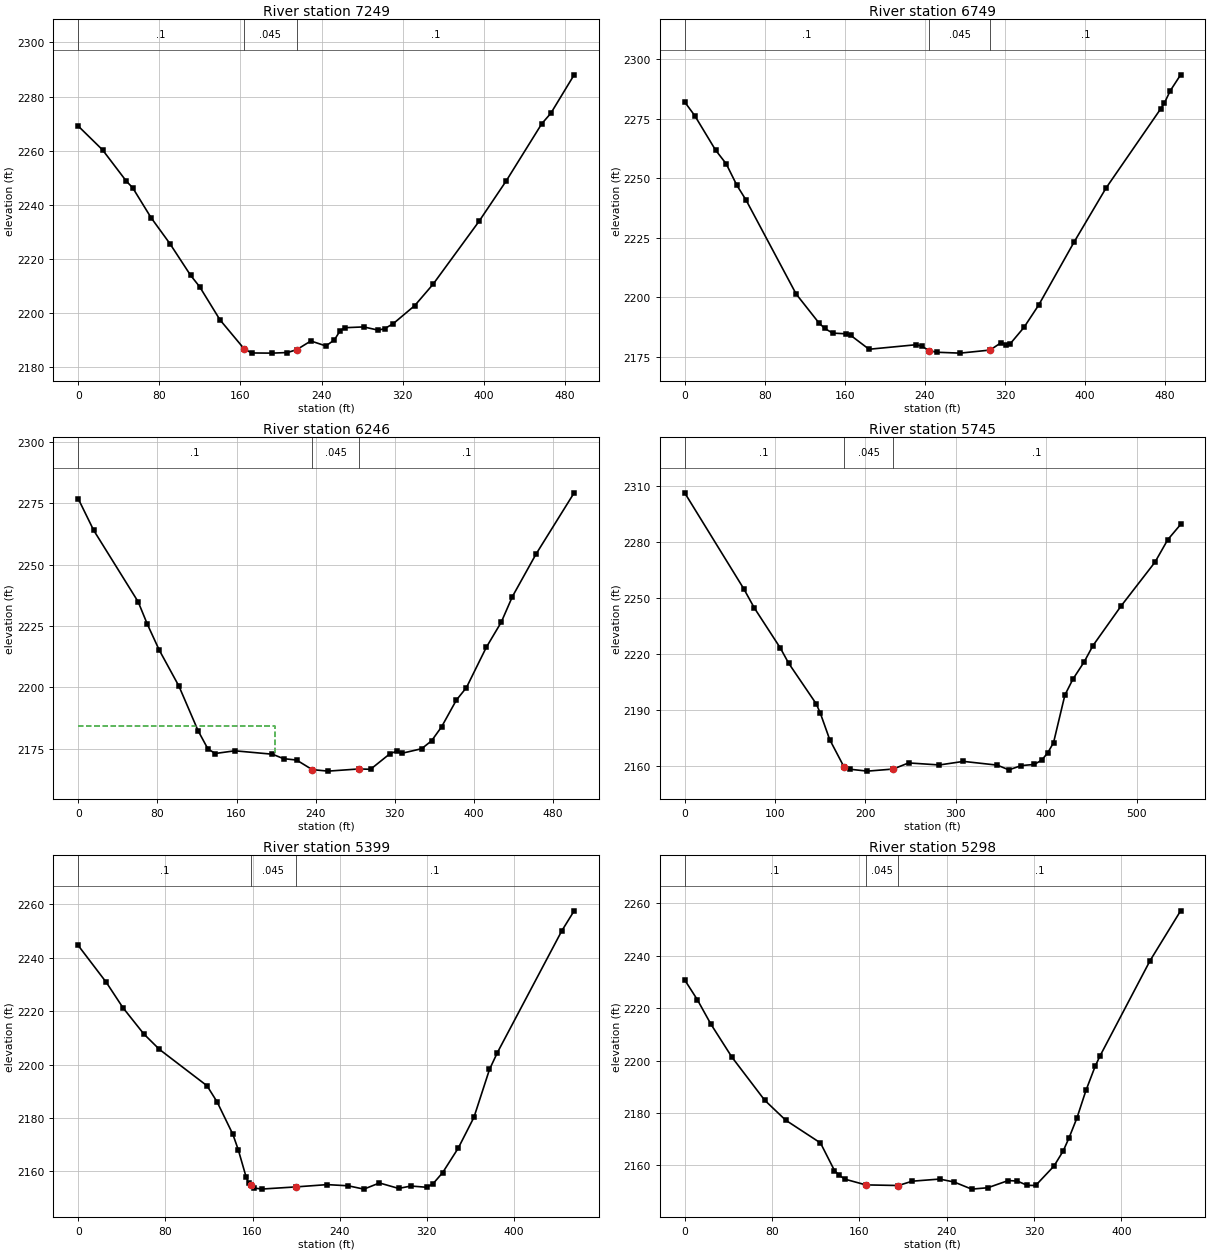
Type RM Length L Ch R = 1 ,7249    ,485.9,500.6,517.2
XS GIS Cut Line= 3
2220100.03824886420487.8007402682220352.58516018420652.485240723
2220432.77885701420822.024921273
#Sta/Elev= 30
       0  2269.1      24  2260.3    47.3 2248.82    53.8 2246.25    71.8 2235.27
    90.4 2225.67   110.9 2213.92   119.7 2209.77   139.8 2197.51   163.6 2186.82
     171 2185.29   191.2 2185.23   206.3 2185.45   215.4  2186.5   229.4 2189.72
   244.2 2187.88   252.6 2190.12   258.3 2193.52   262.8 2194.62   281.5 2194.91
   295.9 2193.71   302.3  2194.3   310.7 2196.14   331.8 2202.78   349.8 2210.63
   395.2 2233.91   422.2 2248.95   457.1 2269.97     466 2273.82     489 2288.02
#Mann= 3 ,-1,0
       0      .1       0   163.6    .045       0   215.4      .1       0
Bank Sta=163.6,215.4
XS Rating Curve= 0 ,0
Exp/Cntr=0.3,0.1

Type RM Length L Ch R = 1 ,6749    ,506.5,502.8,498.7
XS GIS Cut Line= 2
2219756.38668688420667.254740268 2219992.7180543421102.786277832
#Sta/Elev= 30
       0 2282.14    10.1 2276.35    30.8 2261.92    41.5  2256.1    52.2 2247.03
    61.4  2240.8   111.4 2201.31     134 2189.24   139.9 2186.86   147.8 2184.89
   161.5 2184.58     166  2183.9   184.2 2178.09   231.4    2180   237.3 2179.32
   244.1 2177.49     252 2176.83   275.2 2176.46   305.1 2177.75   316.2 2180.87
   320.8 2180.08   325.3 2180.42     339 2187.29   353.6 2196.62     389 2223.15
   420.9 2245.86   475.5 2279.19   479.2 2281.61   485.1 2286.81   495.5 2293.55
#Mann= 3 ,-1,0
       0      .1       0   244.1    .045       0   305.1      .1       0
Bank Sta=244.1,305.1
XS Rating Curve= 0 ,0
Exp/Cntr=0.3,0.1

Type RM Length L Ch R = 1 ,6246    ,503,500.3,499.6
XS GIS Cut Line= 2
2219282.57774932420928.9038027122219585.95338462421327.883268782
#Sta/Elev= 30
       0 2276.79    15.6 2263.95    60.6 2234.82    69.8 2225.77    81.9 2215.18
   101.8  2200.5   121.2 2182.33     131 2175.03   138.4 2173.11   158.3 2174.21
   196.3 2172.82   207.5 2171.01   220.7 2170.45   236.5 2166.55   252.5 2165.94
   283.9 2166.83   295.4 2166.68   315.3 2173.11   321.9 2174.02     327 2173.19
   347.1 2175.06   357.1 2178.28   367.2 2183.94   382.2 2194.87   392.3  2199.9
   412.4 2216.29   427.5 2226.52   438.8 2236.97   462.6 2254.19   501.2 2279.17
#Mann= 3 ,-1,0
       0      .1       0   236.5    .045       0   283.9      .1       0
#XS Ineff= 2 , 0
          199.16  2184.2
Permanent Ineff=
       F       F
Bank Sta=236.5,283.9
XS Rating Curve= 0 ,0
Exp/Cntr=0.3,0.1

Type RM Length L Ch R = 1 ,5745    ,357.9,346.8,340.3
XS GIS Cut Line= 2
2218890.22065067421254.0924723952219242.40430407421674.997696834
#Sta/Elev= 30
       0 2306.27    65.4 2254.91      77 2244.72   105.8 2223.25   115.2 2214.98
   145.6 2193.33   150.1 2188.35   160.5  2174.2   176.1 2159.78   182.5 2158.37
   202.2 2157.34   230.7 2158.45   247.8 2161.73   281.9 2160.64   308.5 2162.55
   345.9 2160.55   358.7 2158.03   372.7 2160.32   386.9 2160.92   395.2 2163.27
     402  2167.3   408.2 2172.63   420.7    2198   429.5 2206.46   442.1 2215.83
   451.8 2224.51     483 2245.76   520.4 2269.14   534.6 2281.22   548.8 2289.34
#Mann= 3 ,-1,0
       0      .1       0   176.1    .045       0   230.7      .1       0
Bank Sta=176.1,230.7
XS Rating Curve= 0 ,0
Exp/Cntr=0.3,0.1

Type RM Length L Ch R = 1 ,5399    ,106.3,100.4,93.7
XS GIS Cut Line= 2
2218674.10710374421595.5249759682219052.66506486 421848.30400162
#Sta/Elev= 30
       0 2244.63    25.8 2230.79      41 2221.33    60.2 2211.46    74.6 2205.65
   118.2 2192.04   127.5 2185.97     142 2173.78   146.9 2168.04   154.2 2157.71
   156.4 2155.54   158.4 2154.71   161.4 2153.68   168.6 2153.31   199.7 2154.11
   228.5 2154.97   247.8 2154.53   262.2 2153.28   276.5 2155.59     294 2153.55
   305.5 2154.44   319.9 2153.97   325.7 2155.31   334.4 2159.41   348.8 2168.65
   363.2 2180.18   377.5 2198.16   384.7 2204.44   443.9 2250.15   455.2 2257.62
#Mann= 3 ,-1,0
       0      .1       0   158.4    .045       0   199.7      .1       0
Bank Sta=158.4,199.7
XS Rating Curve= 0 ,0
Exp/Cntr(USF)=0,0
Exp/Cntr=0.3,0.1

Type RM Length L Ch R = 1 ,5298    ,302.4,312.9,325.4
XS GIS Cut Line= 2
2218609.24255203421732.2607321272219042.88047421421867.645357467
#Sta/Elev= 30
       0 2230.81    11.5 2223.31      24 2213.92    43.3 2201.29    73.3 2184.86
    92.5 2177.25   124.4 2168.55   137.2 2158.03   141.4 2156.26   146.8 2154.72
   165.9 2152.54   195.8  2152.3   208.4 2153.95   233.5 2154.76   246.8 2153.64
   262.9 2150.92   277.7 2151.45   296.4  2154.2   304.8 2153.99   313.8 2152.36
   321.5 2152.31   338.3 2159.73   346.7 2165.46   352.1 2170.51   359.3 2178.06
   367.6 2188.62     376 2197.79   380.2 2201.56   426.3 2238.14   454.3 2257.17
#Mann= 3 ,-1,0
       0      .1       0   165.9    .045       0   195.8      .1       0
Bank Sta=165.9,195.8
XS Rating Curve= 0 ,0
Exp/Cntr=0.3,0.1