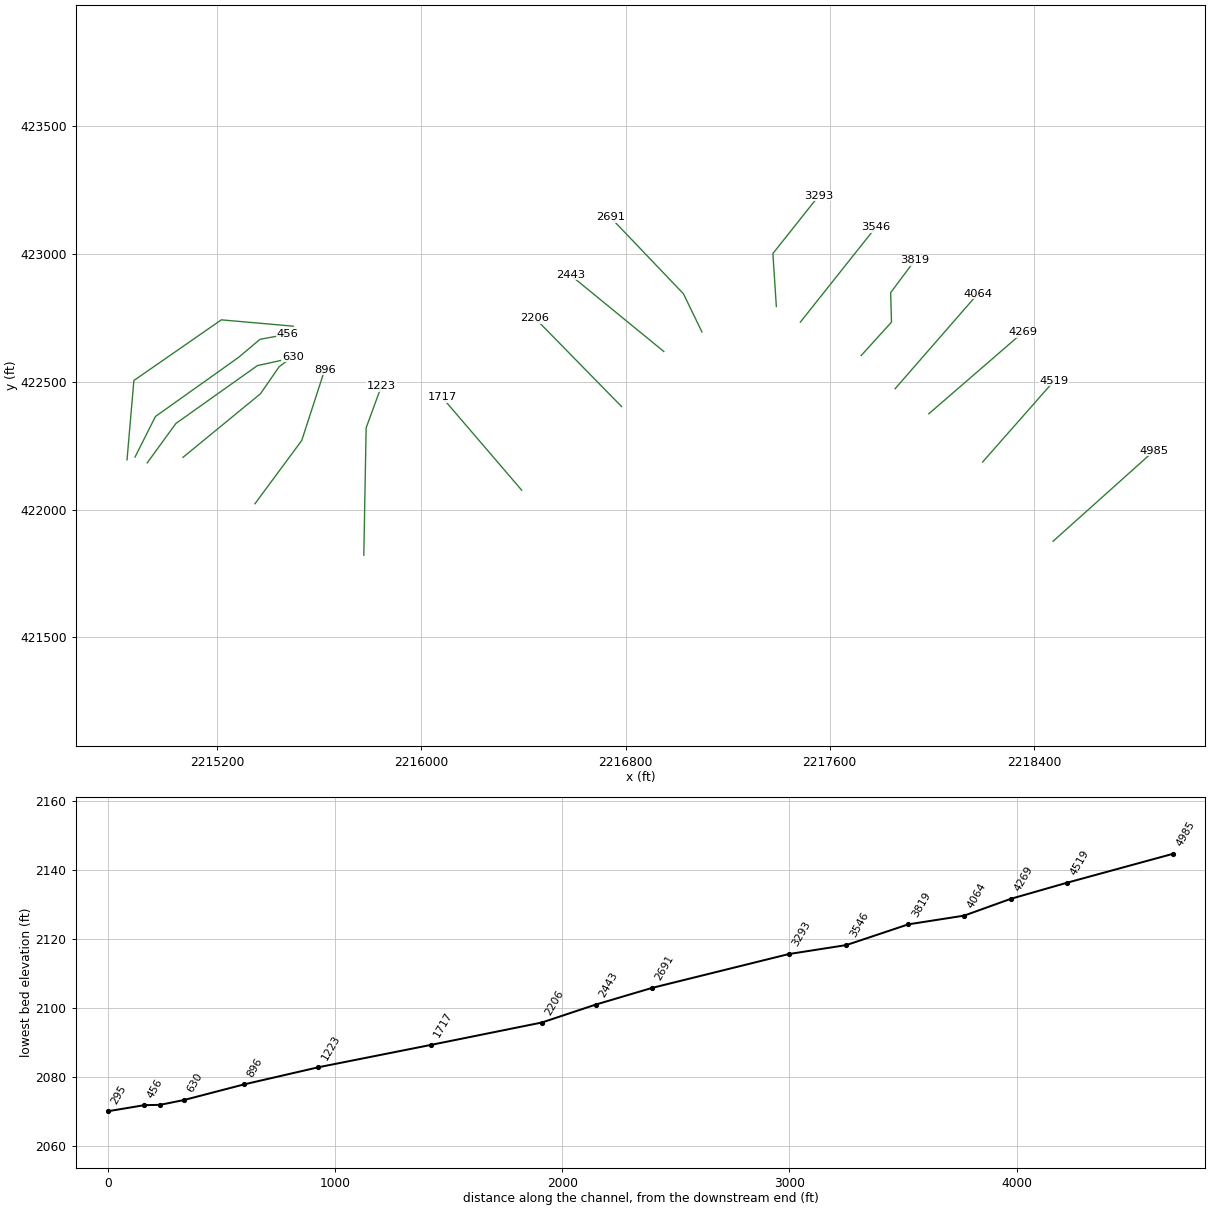
HEC-RAS study BEAVERCK.prj: BEAVERCK

--- BEAVERCK.g01 (geometry) --- (continued)

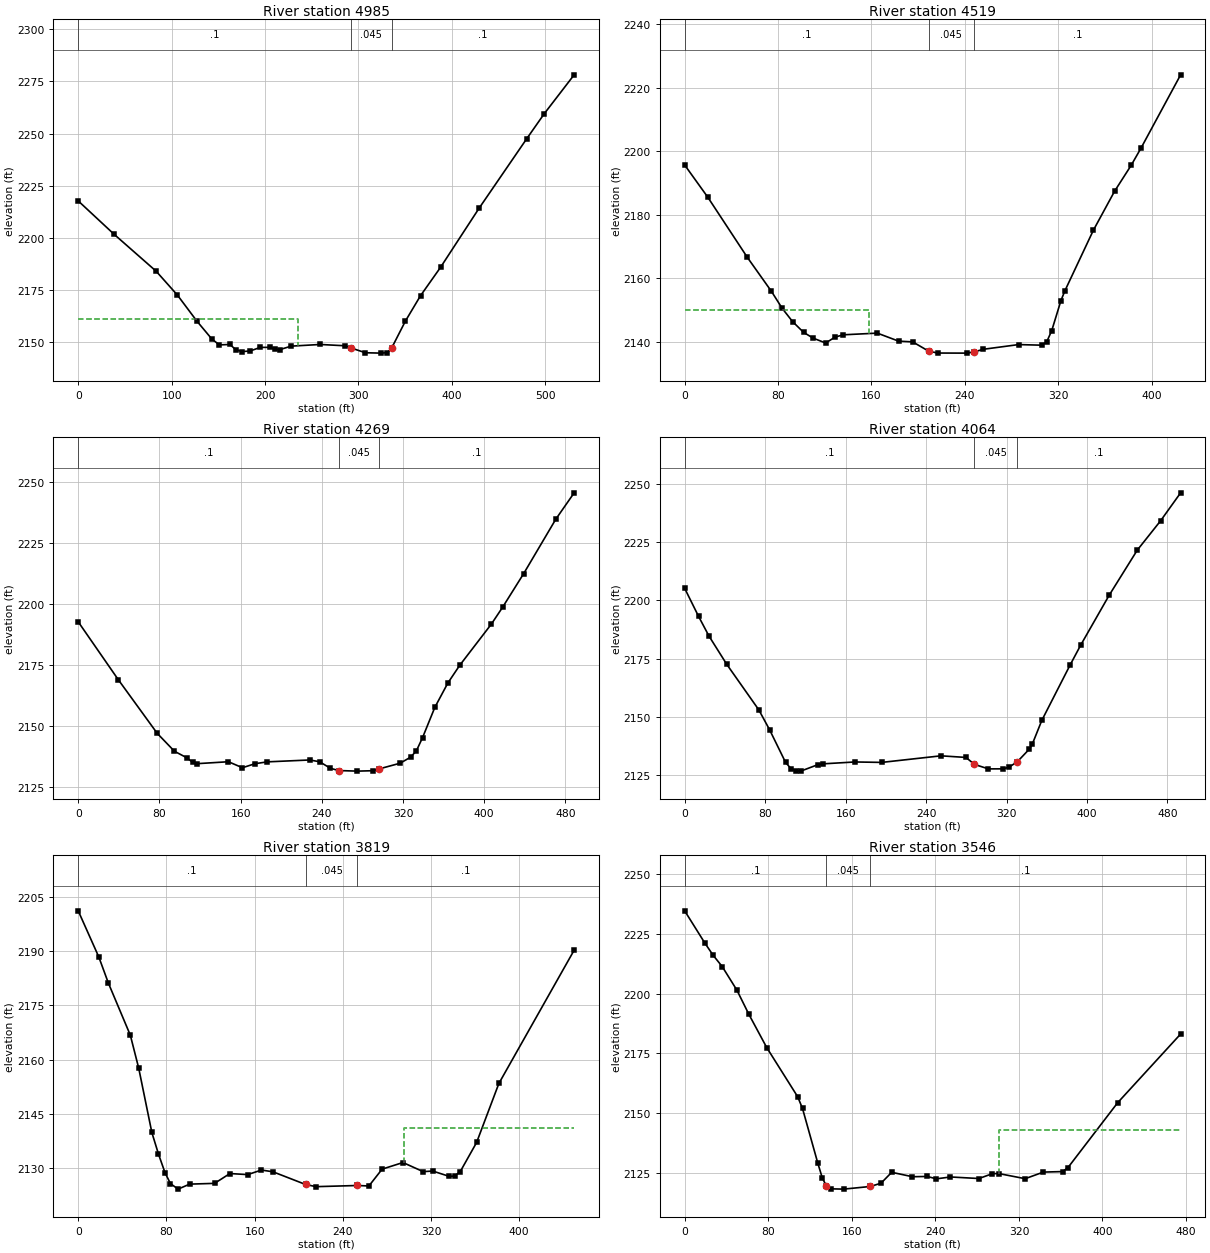
Type RM Length L Ch R = 1 ,4985    ,462.7,466.4,469.7
XS GIS Cut Line= 2
2218475.05888548421876.3905600262218870.71301258 422230.52542688
#Sta/Elev= 30
       0 2217.74    38.2 2201.82    83.5    2184   106.2 2172.58   127.1 2160.08
     143 2151.56   151.1  2148.7   162.5  2148.9   168.5 2146.47   175.1 2145.49
     184 2145.76   194.8 2147.49   205.1 2147.53   211.1 2146.52   216.2 2146.48
     228  2148.1   259.1  2148.9     286 2148.27   292.22147.215   307.5 2144.93
   324.3 2144.75   331.1 2145.01   335.6 2147.19   350.4 2160.18   366.5 2172.28
     388 2185.92   429.1 2214.15   480.1 2247.48     499 2259.56     531 2278.19
#Mann= 3 ,-1,0
       0      .1       0   292.2    .045       0   335.6      .1       0
#XS Ineff= 2 , 0
          234.98 2161.01
Permanent Ineff=
       F       F
Bank Sta=292.2,335.6
XS Rating Curve= 0 ,0
Exp/Cntr(USF)=0,0
Exp/Cntr=0.3,0.1

Type RM Length L Ch R = 1 ,4519    ,253.2,249.8,246.9
XS GIS Cut Line= 2
2218199.07792027422186.5638572022218479.94350433422505.285237371
#Sta/Elev= 30
       0 2195.61    19.8 2185.47    53.6 2166.56    74.3 2155.83    83.5 2150.48
    92.4 2146.31   101.8 2142.92   110.1 2141.08   120.8 2139.55   128.7  2141.4
   135.8 2142.14     165 2142.67   183.2 2140.15   195.3 2139.91   208.9 2137.01
   216.7  2136.4   241.5 2136.37   247.92136.742   255.8 2137.58     286 2139.06
   305.9 2138.87   310.2 2140.01   314.4 2143.45   322.3 2152.93   325.7 2156.02
     350 2175.02   368.2 2187.33   382.4 2195.49   390.9 2200.95   424.8 2224.01
#Mann= 3 ,-1,0
       0      .1       0   208.9    .045       0   247.9      .1       0
#XS Ineff= 2 , 0
          158.29 2149.87
Permanent Ineff=
       F       F
Bank Sta=208.9,247.9
XS Rating Curve= 0 ,0
Exp/Cntr(USF)=0,0
Exp/Cntr=0.3,0.1

Type RM Length L Ch R = 1 ,4269    ,200.8,205,207.8
XS GIS Cut Line= 2
2217988.25560633422375.3251601792218357.81920634422694.864536655
#Sta/Elev= 30
       0 2192.72    39.5 2169.04    77.8 2147.13    94.8 2139.78   106.8 2137.17
   112.9 2135.23   117.5 2134.72     148  2135.5   161.8 2133.05   174.2  2134.7
   186.3 2135.45   228.1 2136.22   237.8  2135.5   248.4 2132.84   256.5  2131.9
   274.9 2131.66   290.3 2131.83   296.2 2132.54   317.2  2134.9   327.4 2137.36
   333.1 2139.91   339.2 2145.31   351.4 2157.78   364.2 2167.71   375.9 2174.95
   407.1 2191.82   418.1 2198.67   438.8 2212.38   470.5 2234.66   488.6 2245.46
#Mann= 3 ,-1,0
       0      .1       0   256.5    .045       0   296.2      .1       0
Bank Sta=256.5,296.2
XS Rating Curve= 0 ,0
Exp/Cntr=0.3,0.1

Type RM Length L Ch R = 1 ,4064    ,219.7,245.2,259.4
XS GIS Cut Line= 2
2217856.26180077 422473.616625142218180.47837715422845.091888924
#Sta/Elev= 30
       0 2205.17    13.8 2193.16    24.2 2184.68    41.9 2172.55    73.7 2153.07
    84.4 2144.56   100.3 2130.56   105.6  2127.9   110.9 2126.96   115.4  2126.8
   132.1 2129.52   137.5 2129.92   169.3 2130.73   195.9 2130.54   254.8 2133.36
   279.7 2132.67   288.12129.685     302 2127.76   316.2 2127.78   322.3 2128.44
   330.82130.858   342.7 2136.25   345.5 2138.24   355.1 2148.56   383.1  2172.2
   393.7 2180.79     422 2202.17     450 2221.55   473.1 2234.08   493.1 2246.12
#Mann= 3 ,-1,0
       0      .1       0   288.1    .045       0   330.8      .1       0
Bank Sta=288.1,330.8
XS Rating Curve= 0 ,0
Exp/Cntr(USF)=0,0
Exp/Cntr=0.3,0.1

Type RM Length L Ch R = 1 ,3819    ,289.8,272.5,253.5
XS GIS Cut Line= 4
2217723.27805249422603.3032556922217841.97429063422734.088925485
 2217838.6771729422849.4880458912217933.19454771422975.877558717
#Sta/Elev= 30
       0 2201.09    18.7 2188.34    27.4 2181.12    47.3 2166.74    54.9 2157.64
    66.8 2139.91    72.8 2133.97    78.7 2128.85    83.6 2125.83    90.6 2124.28
   101.1 2125.66   123.7 2125.87   137.6 2128.58   153.8 2128.29   166.2 2129.55
   176.6 2129.07   206.22125.569   215.7 2124.96   253.32125.282   263.7 2125.15
   275.7  2129.8   294.6 2131.62   312.9 2129.11   321.6 2129.27   336.6  2127.8
   341.5 2127.88   346.6 2129.14   361.4 2137.15   381.6 2153.44   449.9 2190.23
#Mann= 3 ,-1,0
       0      .1       0   206.2    .045       0   253.3      .1       0
#XS Ineff= 2 , 0
       0                   295.8       0 2141.11
Permanent Ineff=
       F       F
Bank Sta=206.2,253.3
XS Rating Curve= 0 ,0
Exp/Cntr(USF)=0,0
Exp/Cntr=0.3,0.1

Type RM Length L Ch R = 1 ,3546    ,254,253.6,253.5
XS GIS Cut Line= 2
2217484.78653699422734.0889254852217780.42809308423105.564189269
#Sta/Elev= 30
       0 2234.56    19.3  2221.1    27.4  2215.9    35.9 2211.29      50 2201.41
    61.5 2191.28    78.6 2177.39   108.2 2156.87   112.8 2151.98   127.5 2129.06
   131.8  2122.9   135.6 2119.68   140.3  2118.4   152.2 2118.28   177.8 2119.39
     188 2120.77   198.2 2125.31   218.1 2123.46   232.3 2123.57   240.9 2122.57
   254.4 2123.36   281.7 2122.71   294.5 2124.72   300.5  2124.8     326 2122.64
   343.4  2125.4   361.8 2125.61   366.9 2127.25   414.5 2154.37   474.8 2183.08
#Mann= 3 ,-1,0
       0      .1       0   135.6    .045       0   177.8      .1       0
#XS Ineff= 2 , 0
       0                   300.5       0 2142.91
Permanent Ineff=
       F       F
Bank Sta=135.6,177.8
XS Rating Curve= 0 ,0
Exp/Cntr(USF)=0,0
Exp/Cntr=0.3,0.1

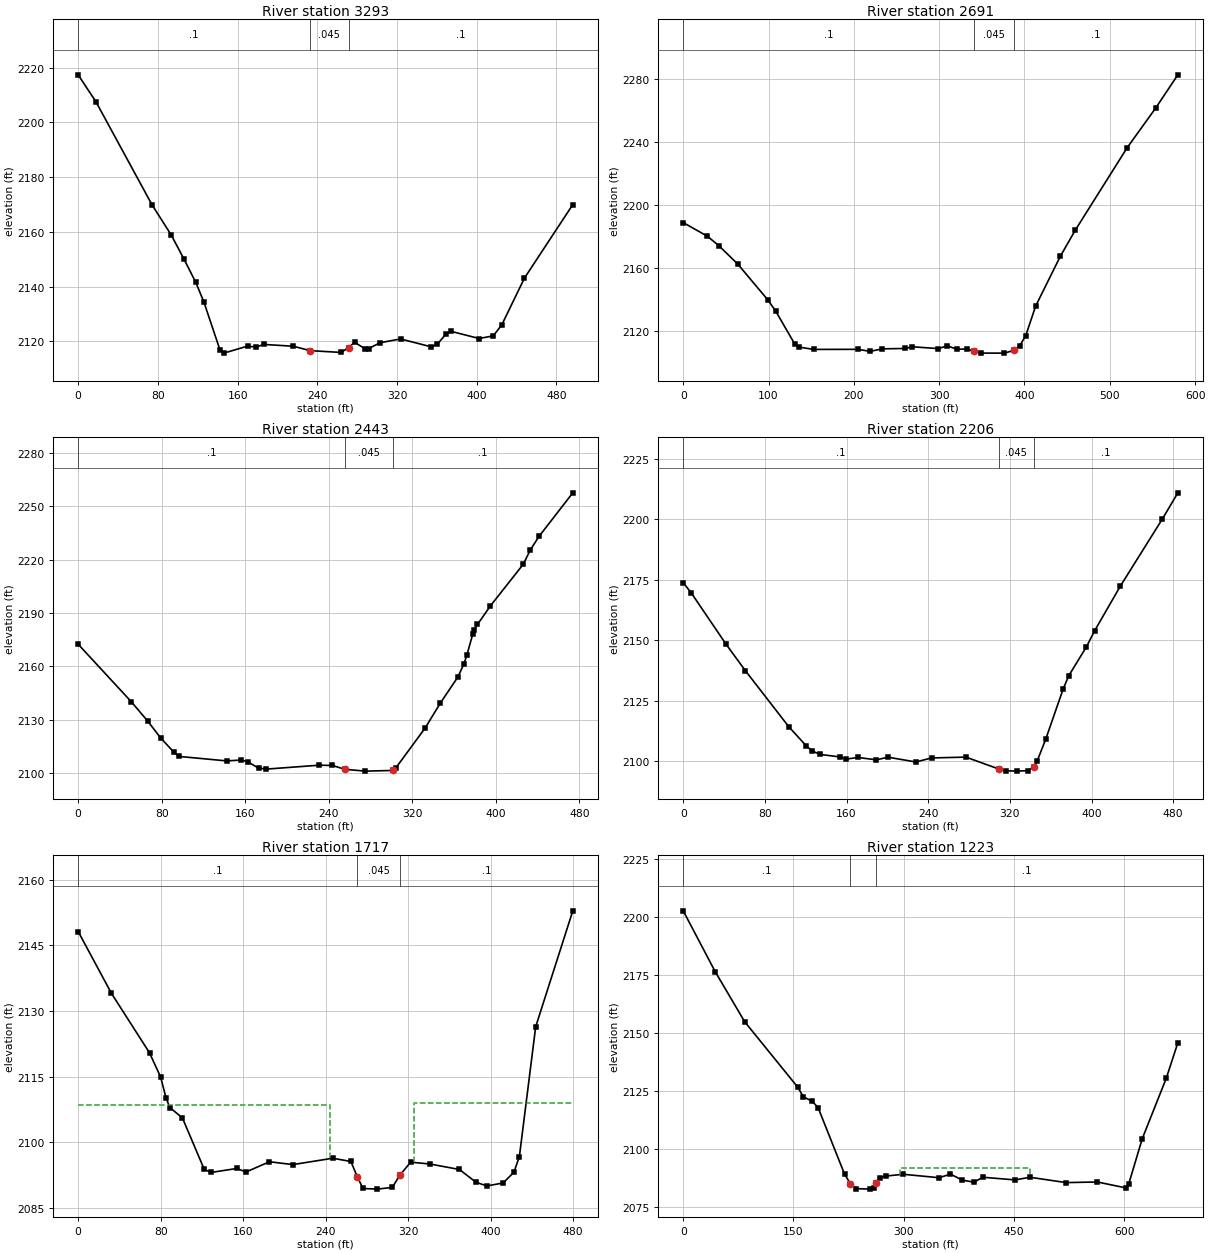
Type RM Length L Ch R = 1 ,3293    ,576.5,601.9,648.2
XS GIS Cut Line= 3
 2217390.8064688422795.2974820872217377.25053915423002.610062632
2217556.95914299423228.520090502
#Sta/Elev= 30
       0 2217.34    17.9 2207.47      74 2169.94    93.6  2158.7   106.1 2150.09
   118.1 2141.48   126.2 2134.33   142.2 2116.96   146.2 2115.67   170.2 2118.25
   178.3 2117.84   186.3 2118.85   216.1 2118.18   232.72116.581   263.9 2115.92
   271.4 2117.72   277.5 2119.64   287.7 2117.27   291.4 2117.33     303 2119.46
   323.5 2120.85   354.2 2117.98   360.2 2118.85   369.5 2122.78   374.6 2123.59
   402.4 2121.01   416.6 2121.98   425.2 2126.05   447.9  2143.1   496.4 2169.94
#Mann= 3 ,-1,0
       0      .1       0   232.7    .045       0   271.4      .1       0
Bank Sta=232.7,271.4
XS Rating Curve= 0 ,0
Exp/Cntr=0.3,0.1

Type RM Length L Ch R = 1 ,2691    ,244.5,247.7,251.5
XS GIS Cut Line= 3
2217099.31553575422695.6032669652217026.79701719422845.103393668
2216740.95980271423144.154465162
#Sta/Elev= 30
       0 2188.86    28.4 2180.15    41.8 2174.16      64 2162.44    99.3 2139.63
   108.3  2132.7   130.7 2111.67   135.2 2109.76   152.9 2108.22     205 2108.27
     219 2106.97   233.6 2108.59   260.3 2108.82   268.4  2109.9   299.1 2108.74
   309.5 2110.52   320.5 2108.35   332.2 2108.46   340.6 2107.21   349.1 2105.88
   376.5 2105.86   387.6 2107.62   394.4 2110.54   401.5 2116.98   413.1 2135.76
     442 2167.39   459.5 2183.98   520.4 2236.48   553.6  2261.5   579.8 2282.79
#Mann= 3 ,-1,0
       0      .1       0   340.6    .045       0   387.6      .1       0
Bank Sta=340.6,387.6
XS Rating Curve= 0 ,0
Exp/Cntr=0.3,0.1

Type RM Length L Ch R = 1 ,2443    ,242.2,237,235.4
XS GIS Cut Line= 2
2216949.96482794422619.1033895772216583.11588115422918.947962525
#Sta/Elev= 30
       0 2172.44    51.1 2139.95    66.5 2129.27    79.1 2119.66    91.8  2111.6
    96.6  2109.3   142.3 2106.78   156.3 2107.27   162.5 2106.25   172.8 2102.73
   180.3 2102.17   230.8 2104.36   243.5 2104.23   255.5 2102.05   275.1 2101.03
   301.9 2101.41   304.1 2102.68   332.5 2125.39   346.7 2139.13   363.8 2154.06
   369.5 2161.36   372.3 2166.27     378 2178.18   379.4 2180.46   382.5 2183.56
   394.9 2194.03   426.3 2217.39   433.1 2225.47   441.4 2233.08   473.8 2257.62
#Mann= 3 ,-1,0
       0      .1       0   255.5    .045       0   301.9      .1       0
Bank Sta=255.5,301.9
XS Rating Curve= 0 ,0
Exp/Cntr(USF)=0,0
Exp/Cntr=0.3,0.1

Type RM Length L Ch R = 1 ,2206    ,491,489.1,487.7
XS GIS Cut Line= 2
2216784.66836652422403.4185619892216445.42711493422749.415956566
#Sta/Elev= 30
       0 2173.75     8.1 2169.38    41.7 2148.46      61  2137.3   103.5 2114.16
   120.7 2106.22   126.4 2104.15   134.5 2102.72   153.7  2101.7   159.3 2100.79
   171.3 2101.49   189.2  2100.5   200.7  2101.6   227.9 2099.62   243.3 2101.29
     277 2101.63   309.2 2096.71   316.2 2095.99   327.4 2095.84   337.8 2096.05
   343.5  2097.6   346.7 2099.96   355.2 2109.07   372.1 2129.65   377.8 2135.34
   394.8 2147.04   403.2 2153.96   428.2 2172.27   469.2  2199.9   484.6 2210.87
#Mann= 3 ,-1,0
       0      .1       0   309.2    .045       0   343.5      .1       0
Bank Sta=309.2,343.5
XS Rating Curve= 0 ,0
Exp/Cntr=0.3,0.1

Type RM Length L Ch R = 1 ,1717    ,510.3,493.8,477.1
XS GIS Cut Line= 2
2216392.94517014422076.4322850652216080.55646334422440.526492312
#Sta/Elev= 30
       0 2148.14    32.3 2134.02    69.2 2120.45      80 2114.91    85.3 2110.08
      89 2107.95   101.1  2105.6   122.2 2093.89   128.7 2093.14   153.8 2094.05
   162.8 2093.25   185.5 2095.59   208.2 2094.94   246.9 2096.39   264.5 2095.65
   270.6 2092.22   276.2 2089.49   289.9 2089.34   304.6 2089.73   311.9 2092.49
   322.5  2095.5   341.5 2095.06   369.8 2093.82   385.7 2090.92   396.3 2090.07
   412.1 2090.74   422.6  2093.2   427.9 2096.78   443.7  2126.4   479.7 2152.86
#Mann= 3 ,-1,0
       0      .1       0   270.6    .045       0   311.9      .1       0
#XS Ineff= 2 , 0
          243.96 2108.52   325.6         2109.07
Permanent Ineff=
       F       F
Bank Sta=270.6,311.9
XS Rating Curve= 0 ,0
Exp/Cntr=0.3,0.1

Type RM Length L Ch R = 1 ,1223    ,340.2,326.9,311
XS GIS Cut Line= 3
2215774.49120261421821.5848345872215783.62279871422320.084628303
2215843.60802301 422484.01735658
#Sta/Elev= 30
       0 2202.74    43.6 2176.51    83.6    2155   155.6 2126.88   163.6 2122.63
   175.6 2120.71   183.6 2117.96   219.6 2089.29   227.6  2085.2   235.6 2083.09
   254.6 2082.88   259.6 2083.26   262.8 2085.31   267.6  2087.8   275.6 2088.51
   299.6 2089.27   348.3 2087.79   363.7 2089.35   379.7 2086.77   395.7 2085.87
   407.7    2088   451.7 2086.85   471.7    2088     521 2085.69   563.6 2085.96
     602 2083.43   606.2 2085.06   624.6 2104.55   657.3 2130.61   673.1 2145.93
#Mann= 3 ,-1,0
       0      .1       0   227.6    .045       0   262.8      .1       0
#XS Ineff= 1 ,-1
     295     472    2092
Permanent Ineff=
       F
Bank Sta=227.6,262.8
XS Rating Curve= 0 ,0
Exp/Cntr=0.3,0.1

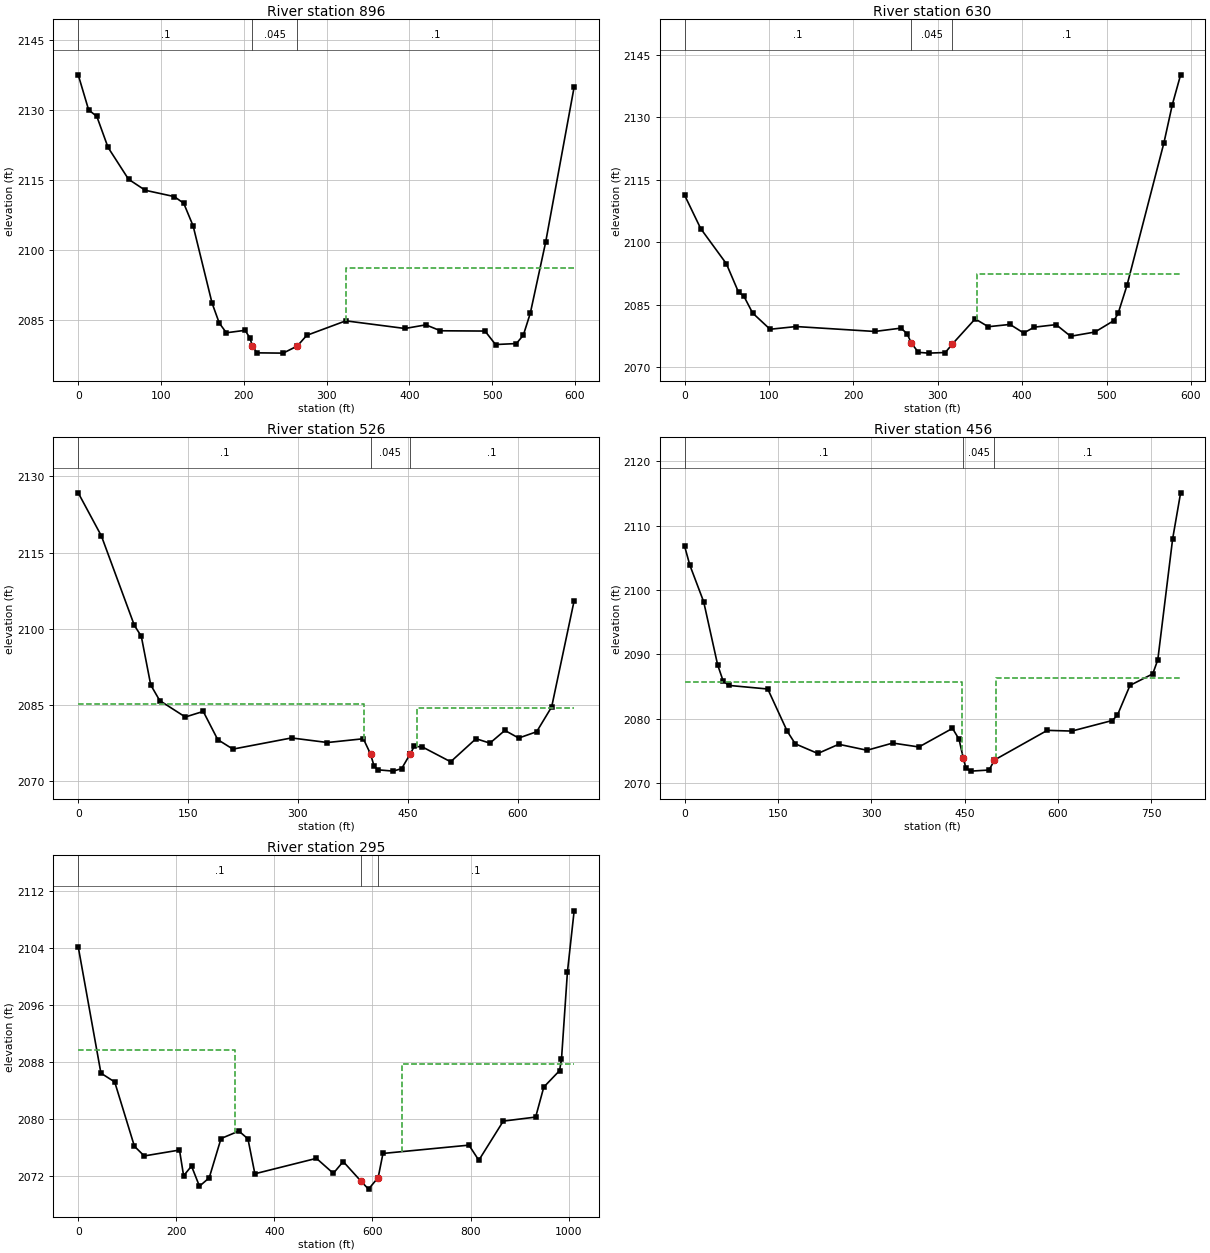
Type RM Length L Ch R = 1 ,896     ,271.9,266.2,257.5
XS GIS Cut Line= 3
2215347.99397005422023.0625827192215531.37883187422270.992919063
 2215621.3028116422547.536627542
#Sta/Elev= 30
       0 2137.56    12.6 2130.04    22.5 2128.64      36 2122.02    60.8 2115.18
      81 2112.82     116 2111.47   127.5 2110.03   138.9 2105.15   161.7 2088.65
   170.4 2084.37     179 2082.28   201.6 2082.81   207.6 2081.13   210.4  2079.4
   216.1 2077.98   247.6 2077.92   264.72079.441   276.1 2081.73   323.3 2084.84
   394.8  2083.2     420 2083.98   437.7 2082.71   491.5 2082.65   504.2 2079.76
   529.4 2079.97   537.8 2081.77   546.2 2086.46   564.7 2101.64   599.2 2134.96
#Mann= 3 ,-1,0
       0      .1       0   210.4    .045       0   264.7      .1       0
#XS Ineff= 2 , 0
                          324.06         2096.09
Permanent Ineff=
       F       F
Bank Sta=210.4,264.7
XS Rating Curve= 0 ,0
Exp/Cntr(USF)=0,0
Exp/Cntr=0.3,0.1

Type RM Length L Ch R = 1 ,630     ,105.8,104.2,101.8
XS GIS Cut Line= 4
2215065.94507353422204.7245890982215369.59512962422453.644044727
2215442.79114313422559.4815237282215496.01497792422599.319147064
#Sta/Elev= 30
       0 2111.23      19 2103.25    49.4 2094.82    63.8 2087.99    70.1 2087.06
    80.5 2082.99   101.2 2079.09   132.2 2079.74   225.3 2078.56   256.3 2079.36
   263.4 2078.07   268.82075.731     277 2073.55     289 2073.36   308.9 2073.51
   317.1  2075.5   344.3 2081.58   359.8  2079.7   385.6 2080.25   401.8 2078.19
   414.3 2079.59   440.2  2080.2   457.4 2077.41   486.2 2078.42   508.8 2081.18
   513.7 2082.88   524.2  2089.6     568 2123.83     578 2133.03   587.8 2140.16
#Mann= 3 ,-1,0
       0      .1       0   268.8    .045       0   317.1      .1       0
#XS Ineff= 2 , 0
                          346.67         2092.41
Permanent Ineff=
       F       F
Bank Sta=268.8,317.1
XS Rating Curve= 0 ,0
Exp/Cntr(USF)=0,0
Exp/Cntr=0.5,0.3

Type RM Length L Ch R = 1 ,526     ,69.9,69.3,69.4
XS GIS Cut Line= 4
2214925.87282231 422183.199806952215038.26333492422337.408768099
2215357.76781961422563.9990911062215450.13658402422584.259881147
#Sta/Elev= 30
       0 2126.75    31.7 2118.25    76.7 2100.65    86.1 2098.54      99 2088.95
   111.3 2085.87   146.2 2082.64   170.7 2083.74   190.5 2078.19   211.2 2076.32
   291.2 2078.52   340.3 2077.62   389.3 2078.36   399.1 2075.35     404 2072.96
   408.9 2072.25   430.2 2071.99   441.6 2072.49   453.1 2075.33   453.1 2075.35
   458.8 2076.84   469.7 2076.76   508.5 2073.83   543.1 2078.37   562.1  2077.5
   582.5    2080   601.4  2078.5   625.9 2079.74   646.4 2084.63   677.1 2105.53
#Mann= 3 ,-1,0
       0      .1       0   399.1    .045       0   453.1      .1       0
#XS Ineff= 2 , 0
          390.24  2085.2  461.93          2084.4
Permanent Ineff=
       F       F
Bank Sta=399.1,453.1
XS Rating Curve= 0 ,0
Exp/Cntr(USF)=0,0
Exp/Cntr=0.5,0.3

Type RM Length L Ch R = 1 ,456     ,161.4,161.2,160.8
XS GIS Cut Line= 5
2214878.11956186422205.8826056642214958.10627312422364.662196665
 2215284.0222757422596.2655098552215367.59048149 422666.70156902
2215476.22914902422686.996704712
#Sta/Elev= 30
       0 2106.77     8.2  2103.9    30.6 2098.17      53 2088.39    61.9 2085.87
    70.9  2085.2   133.6 2084.64   164.9 2078.08   177.8 2076.13   214.1 2074.63
   247.7 2076.06   293.2 2075.13   334.5 2076.25   376.6 2075.64   430.6 2078.53
   441.1 2076.85     448 2073.89   452.2 2072.36     460 2071.89   489.5 2072.06
   498.1 2073.62     583 2078.22   622.5 2078.11   687.5 2079.75   695.6 2080.54
     716  2085.2   752.6 2086.99   760.7 2089.18   784.6 2107.97   797.4  2115.1
#Mann= 3 ,-1,0
       0      .1       0     448    .045       0   498.1      .1       0
#XS Ineff= 2 , 0
          446.54  2085.8  501.32          2086.3
Permanent Ineff=
       F       F
Bank Sta=448,498.1
XS Rating Curve= 0 ,0
Exp/Cntr(USF)=0,0
Exp/Cntr=0.5,0.3

Type RM Length L Ch R = 1 ,295     ,,,
XS GIS Cut Line= 4
2214846.75760806422195.0545538572214873.61881706422505.570129942
2215216.36784395422743.0232175372215497.87331432422718.310905253
#Sta/Elev= 30
       0 2104.23    46.3 2086.44    74.4  2085.2   114.6 2076.15   134.6 2074.79
   206.5 2075.62   214.9    2072     231 2073.37   247.2 2070.53   267.1 2071.71
   291.2 2077.24   327.6 2078.29   346.1 2077.19   360.2 2072.28   485.7 2074.45
   520.2 2072.34   540.3    2074   576.8 2071.22   591.9 2070.12   611.6 2071.75
   621.4 2075.14   796.7 2076.31   816.8 2074.18   866.7 2079.69   932.7 2080.26
   949.3 2084.48   981.4 2086.79   985.4 2088.41   997.5 2100.69  1011.2 2109.28
#Mann= 3 ,-1,0
       0      .1       0   576.8    .045       0   611.6      .1       0
#XS Ineff= 2 , 0
          320.38 2089.63  660.35         2087.71
Permanent Ineff=
       F       F
Bank Sta=576.8,611.6
XS Rating Curve= 0 ,0
Exp/Cntr(USF)=0,0
Exp/Cntr=0.3,0.1
LCMann Table=0

Chan Stop Cuts=-1
Use User Specified Reach Order=0
Composite Channel Slope=5